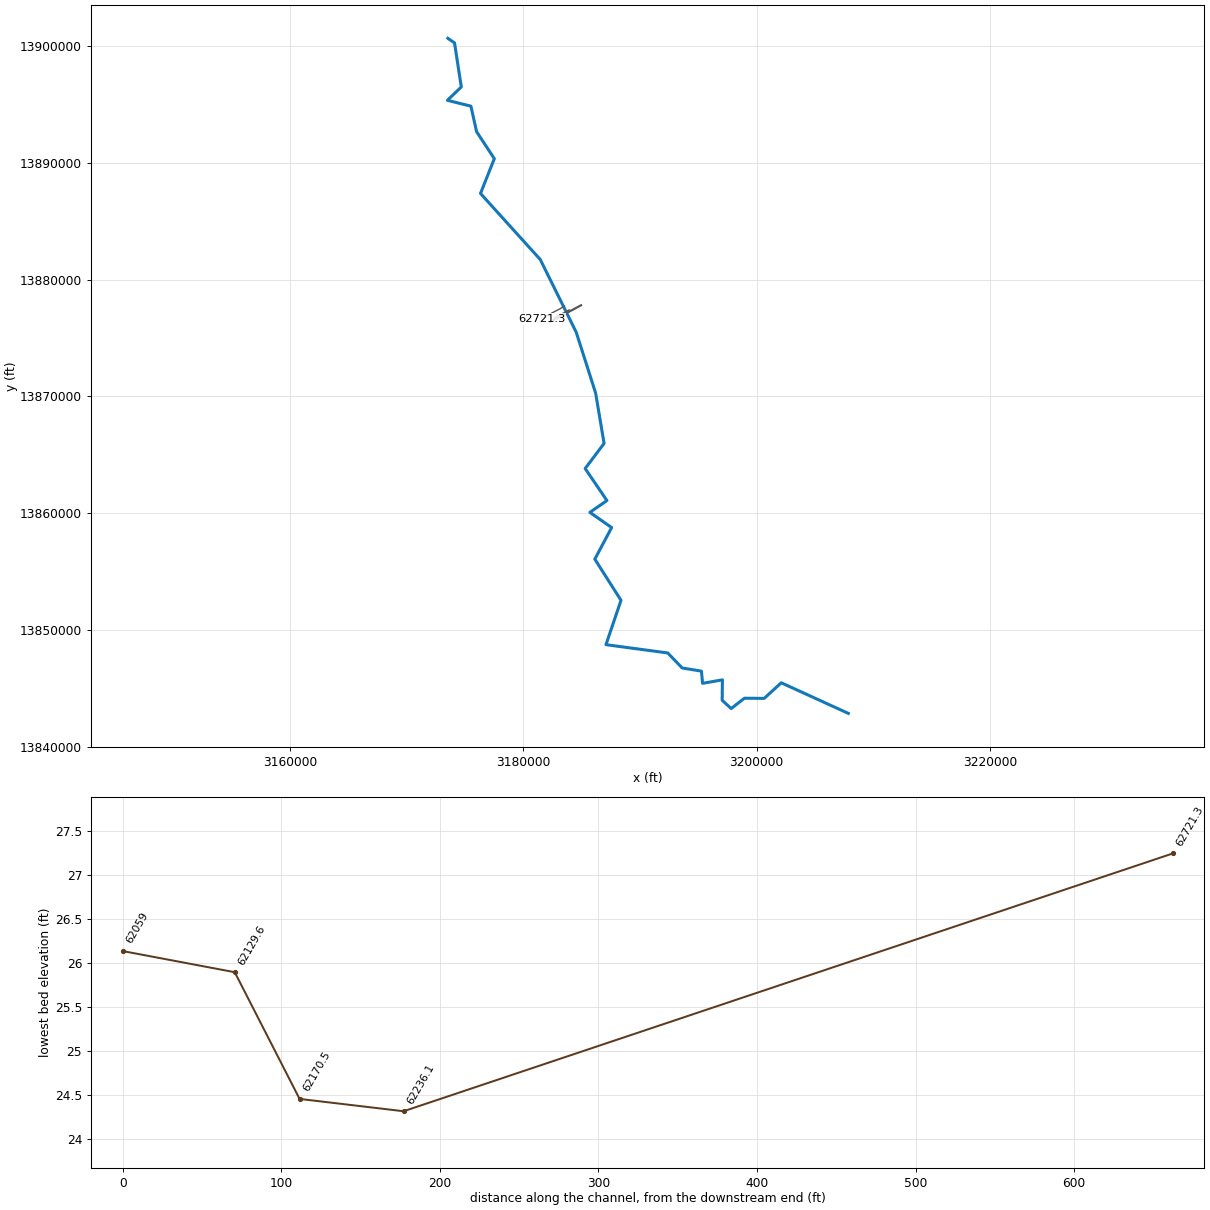
--- N100-00-00.prj (project) ---

Proj Title=N100-00-00
Current Plan=p02
Default Exp/Contr=.3,.1
English Units
Geom File=g01
Flow File=f01
Flow File=f02
Plan File=p01
Plan File=p02
Y Axis Title=Elevation
X Axis Title(PF)=Main Channel Distance
X Axis Title(XS)=Station
BEGIN DESCRIPTION:
HCFCD Watershed Unit ID: N
M3 Study Identifier: 2007_Effective_N
Engineer: HCFCD
Project Name: EffectiveFEMA Study for watershed Carpenters Bayou (N)
Study Completion Date: 6/18/2007
FEMA Case Number: [No Data]
FEMA Approval Date: [No Date in Database]
Vertical Datum: NAVD 1988
Datum Note: 2001 ADJ
HYDRAULICS
HCFCD Unit No.:  N100-00-00
Hydraulic Program Name: HEC-RAS
Hydraulic Program Version: 3.0.1
Steady Hydraulic Model: Yes
Unsteady Hydraulic Model: No
Update1:
The effective FEMA hydraulic model for unit number N100-00-00 has been updated by FEMA LOMR 09-06-0950P with an effective date of 3/30/2009.
Update2:
The effective FEMA hydraulic model for unit number N100-00-00 has been updated by FEMA LOMR 13-06-43ppP with an effective date of 06/26/2014.
END DESCRIPTION:
DSS Export Rating Curves= 0
DSS Export Rating Curve Sorted= 1
DSS Export Volume Flow Curves= 10
N100-00-00      ,N100-00-00_0017 ,62537.2 ,N100-00-00_0017 ,55096.0
N100-00-00      ,N100-00-00_0017 ,55096.0 ,N100-00-00_0017 ,54149.0
N100-00-00      ,N100-00-00_0017 ,54149.0 ,N100-00-00_0017 ,53166.0
N100-00-00      ,N100-00-00_0017 ,53166.0 ,N100-00-00_0017 ,52095.0
N100-00-00      ,N100-00-00_0017 ,52095.0 ,N100-00-00_0017 ,42982.0
N100-00-00      ,N100-00-00_0017 ,42982.0 ,N100-00-00_0017 ,36898.0
N100-00-00      ,N100-00-00_0017 ,36898.0 ,N100-00-00_0017 ,34417.0
N100-00-00      ,N100-00-00_0017 ,32787.0 ,N100-00-00_0017 ,27780.5
N100-00-00      ,N100-00-00_0017 ,27780.5 ,N100-00-00_0017 ,18117.0
N100-00-00      ,N100-00-00_0017 ,18117.0 ,N100-00-00_0017 ,1727.0
DXF OffsetX= 0
DXF OffsetY= 0
DXF ScaleX= 1
DXF ScaleY= 10

--- N100-00-00.p02 (plan) ---

Plan Title=Effective Floodway 2014
Version=Version 3.0.1  May 2012
Short Identifier=Eff+LOMR FW
Geom File=g01
Flow File=f02
Subcritical Flow
K Sum by GR= 0
Std Step Tol= 0.01
Critical Tol= 0.01
Num of Std Step Trials= 20
Max Error Tol= 0.3
Flow Tol Ratio= 0.001
Split Flow NTrial= 30
Split Flow Tol= 0.02
Split Flow Ratio= 0.02
Log Output Level= 0
Friction Slope Method= 1
Unsteady Friction Slope Method= 2
Parabolic Critical Depth
Global Vel Dist= 0 , 0 , 0
Global Log Level= 0
CheckData=True
Encroach Param= 0 ,0,0, 2
Encroach River=N100-00-00
Encroach Reach=Reach - 1
Encroach Node=63088.0
       1  4955.7  5045.7
Encroach Node=62602.8
       1  4963.1    5036
Encroach Node=62570.0
       1  4963.1    5036
Encroach Node=62537.2
       1  4963.1    5036
Encroach Node=62496.3
       1  4975.5  5030.7
Encroach Node=62461.0
       1  4975.5  5030.7
Encroach Node=62425.7
       1  4975.5  5030.7
Encroach Node=61988.2
       1  4966.4  5047.2
Encroach Node=61445.0
       1  4966.4  5047.2
Encroach Node=60312.0
       1  4963.4  5046.4
Encroach Node=59383.0
       1    4956  5048.4
Encroach Node=58411.0
       1  4943.7  5037.5
Encroach Node=57932.7
       1    4960  5072.8
Encroach Node=57739.5
       1  4897.2  5091.5
Encroach Node=57526.0
       1  4897.2  5091.5
Encroach Node=57312.5
       1  4897.2  5091.5
Encroach Node=56867.4
       1  4952.3  5050.3
Encroach Node=56336.0
       1  4952.3  5050.3
Encroach Node=55096.0
       1    4953    6050
Encroach Node=54149.0
       1  4947.1    6380
Encroach Node=53166.0
       1    4961    6710
Encroach Node=52095.0
       1    4600    6590
Encroach Node=51254.0
       1    4500  5057.3
Encroach Node=50254.0
       1    4500  5075.6
Encroach Node=49707.5
       1    4915    5045
Encroach Node=49697.0
       1    4915 5041.79
Encroach Node=49696.0
       1    4915 5041.24
Encroach Node=49685.0
       1    4915    5041
Encroach Node=49674.0
       1    4915 5040.75
Encroach Node=49375.9
       1    4945    5050
Encroach Node=49286.0
       1    4958    5042
Encroach Node=49270.0
       1    4958    5042
Encroach Node=49254.0
       1    4958    5042
Encroach Node=48967.5
       1    4958    5050
Encroach Node=48957.0
       1    4958    5050
Encroach Node=48955.5
       1    4958    5050
Encroach Node=48943.0
       1    4958    5050
Encroach Node=48930.5
       1    4958    5050
Encroach Node=48308.0
       1    4943  5057.6
Encroach Node=47238.0
       1  4921.5  5055.5
Encroach Node=46226.0
       1  4912.9  5058.4
Encroach Node=45425.6
       1  4929.5  5077.9
Encroach Node=45272.3
       1  4929.5  5061.8
Encroach Node=45231.0
       1  4929.5  5061.8
Encroach Node=45189.7
       1  4929.5  5061.8
Encroach Node=44594.8
       1    4915    5055
Encroach Node=44027.0
       1    4905  5072.1
Encroach Node=42982.0
       1  4934.6  5054.8
Encroach Node=42012.0
       1  4922.6  5050.6
Encroach Node=41004.0
       1  4927.7    5064
Encroach Node=39962.0
       1    4935    5085
Encroach Node=39413.0
       1  4932.5  5067.5
Encroach Node=39112.4
       1  4933.7  5083.5
Encroach Node=39003.2
       1    4941    5073
Encroach Node=38969.0
       1    4941    5073
Encroach Node=38934.8
       1    4941    5073
Encroach Node=38512.3
       1  4928.3  5059.6
Encroach Node=38057.0
       1  4928.3  5059.6
Encroach Node=36898.0
       1  4922.4  5057.6
Encroach Node=35826.0
       1    4880  5046.7
Encroach Node=35246.0
       1    4900    5079
Encroach Node=35010.9
       1    4950    5070
Encroach Node=34905.4
       1    4935    5072
Encroach Node=34841.0
       1    4935    5072
Encroach Node=34776.6
       1    4935    5072
Encroach Node=34417.0
       1    4922    5100
Encroach Node=33867.0
       1  4943.8    5135
Encroach Node=32787.0
       1  4936.5    5100
Encroach Node=31729.0
       1  4954.9    5071
Encroach Node=31199.0
       1  4943.1    5180
Encroach Node=30834.4
       1  4961.6  5064.2
Encroach Node=30741.5
       1 4896.36 5120.55
Encroach Node=30712.0
       1 4896.36 5120.55
Encroach Node=30682.5
       1 4896.36 5120.55
Encroach Node=30217.0
       1  4927.2    5130
Encroach Node=29239.0
       1  4944.1 5246.64
Encroach Node=28433.0
       1  4944.6 5141.35
Encroach Node=28255.5
       1    4880    5140
Encroach Node=28244.0
       1    4880    5140
Encroach Node=28232.5
       1    4880    5140
Encroach Node=27803.5
       1    4880    5140
Encroach Node=27792.0
       1    4880    5140
Encroach Node=27780.5
       1    4880    5140
Encroach Node=27198.4
       1    4940    5185
Encroach Node=26989.1
       1    4880    5093
Encroach Node=26974.0
       1    4880    5093
Encroach Node=26958.9
       1    4880    5093
Encroach Node=26748.3
       1    4908    5310
Encroach Node=26717.0
       1    4928    5310
Encroach Node=26685.7
       1    4908    5310
Encroach Node=26390.5
       1    4850    5130
Encroach Node=26379.0
       1    4850    5130
Encroach Node=26367.5
       1    4850    5130
Encroach Node=25919.5
       1    4860    5140
Encroach Node=25908.0
       1    4860    5140
Encroach Node=25896.5
       1    4860    5140
Encroach Node=24592.0
       1    4930    5225
Encroach Node=24343.7
       1    4940    5185
Encroach Node=24159.3
       1    4900    5120
Encroach Node=24126.0
       1    4900    5120
Encroach Node=24092.7
       1    4900    5120
Encroach Node=23934.0
       1    4886    5145
Encroach Node=23835.0
       1    4886    5130
Encroach Node=23736.0
       1    4830    5155
Encroach Node=23728.3
       1    4800    5150
Encroach Node=23691.0
       1    4800    5150
Encroach Node=23653.7
       1    4800    5150
Encroach Node=23117.0
       1    4900    5170
Encroach Node=22741.0
       1    4920    5150
Encroach Node=22003.2
       1    4830    5050
Encroach Node=21894.0
       1    4900    5050
Encroach Node=21866.0
       1    4900    5050
Encroach Node=21838.0
       1    4900    5050
Encroach Node=21368.6
       1    4800    5055
Encroach Node=21128.0
       1    4800    5055
Encroach Node=20968.0
       1    4940    5055
Encroach Node=20948.0
       1    4940    5055
Encroach Node=20928.0
       1    4940    5055
Encroach Node=20345.4
       1    4700    5039
Encroach Node=20014.0
       1    4800    5081
Encroach Node=18968.0
       1    4500    5105
Encroach Node=18117.0
       1    4680    5245
Encroach Node=17108.0
       1    4845    5400
Encroach Node=16002.0
       1    4875    5275
Encroach Node=14723.0
       1    4700    5200
Encroach Node=13984.0
       1    4750    5300
Encroach Node=12968.0
       1    4475    5230
Encroach Node=11816.0
       1  4937.5  5444.3
Encroach Node=11600.8
       1    4890    5110
Encroach Node=11570.0
       1    4890    5110
Encroach Node=11539.2
       1    4890    5110
Encroach Node=10683.7
       1  4839.2  5119.2
Encroach Node=10189.0
       1  4812.7  5175.4
Encroach Node=9283.0
       1  4812.9  5175.6
Encroach Node=7760.7
       1  4813.1  5251.3
Encroach Node=5945.8
       1  4771.3  5201.3
Encroach Node=4636.0
       1  4819.6  5197.7
Encroach Node=2934.1
       1  4847.9  5147.9
Encroach Node=1727.0
       1  4801.2  5195.1
Encroach Reach=N100-00-00_0017
Encroach Node=62721.3
       1  4955.7  5045.7
Encroach Node=62236.1
       1  4963.1    5036
Encroach Node=62203
       1  4963.1    5036
Encroach Node=62170.5
       1  4963.1    5036
Encroach Node=62129.6
       1  4975.5  5030.7
Encroach Node=62094
       1  4975.5  5030.7
Encroach Node=62059
       1  4975.5  5030.7
Encroach Node=61621.5
       1  4966.4  5047.2
Encroach Node=61078.3
       1  4966.4  5047.2
Encroach Node=59945.3
       1  4963.4  5046.4
Encroach Node=59016.3
       1    4956  5048.4
Encroach Node=58044.3
       1  4943.7  5037.5
Encroach Node=57566
       1    4960  5072.8
Encroach Node=57372.8
       1  4897.2  5091.5
Encroach Node=57159
       1  4897.2  5091.5
Encroach Node=56945.8
       1  4897.2  5091.5
Encroach Node=56500.7
       1  4952.3  5050.3
Encroach Node=55969.3
       1  4952.3  5050.3
Encroach Node=54729.3
       1    4953    6050
Encroach Node=53782.3
       1  4947.1    6380
Encroach Node=52799.3
       1    4961    6710
Encroach Node=51728.3
       1    4600    6590
Encroach Node=50887.3
       1    4500  5057.3
Encroach Node=49887.3
       1    4500  5075.6
Encroach Node=49340.8
       1    4915    5045
Encroach Node=49330
       1    4915 5041.79
Encroach Node=49329.3
       1    4915 5041.24
Encroach Node=49318
       1    4915    5041
Encroach Node=49307.3
       1    4915 5040.75
Encroach Node=49009.2
       1  4969.3    5050
Encroach Node=48919.3
       1  4969.3    5042
Encroach Node=48903
       1  4969.3    5042
Encroach Node=48887.3
       1  4969.3    5042
Encroach Node=48600.8
       1 4966.62    5050
Encroach Node=48590
       1 4966.62    5050
Encroach Node=48588.8
       1 4966.62    5050
Encroach Node=48576
       1 4966.62    5050
Encroach Node=48563.8
       1 4959.78    5050
Encroach Node=47941.3
       1    4943  5057.6
Encroach Node=47014.3
       1 4909.76  5083.3
Encroach Node=46572.3
       1 4892.55 5087.31
Encroach Node=46172.3
       1 4912.48 5097.81
Encroach Node=45772.3
       1 4912.91 5092.22
Encroach Node=45502.3
       1 4906.84 5098.34
Encroach Node=45462.3
       1 4912.22 5092.95
Encroach Node=45272.3
       1  4929.5  5061.8
Encroach Node=45231.0
       1  4929.5  5061.8
Encroach Node=45189.7
       1  4929.5  5061.8
Encroach Node=44594.8
       1    4915    5055
Encroach Node=44027.0
       1    4905  5072.1
Encroach Node=42982.0
       1  4934.6  5054.8
Encroach Node=42012.0
       1  4922.6  5050.6
Encroach Node=41004.0
       1  4927.7    5064
Encroach Node=39962.0
       1    4935    5085
Encroach Node=39413.0
       1  4932.5  5067.5
Encroach Node=39112.4
       1  4933.7  5083.5
Encroach Node=39003.2
       1    4941    5073
Encroach Node=38969.0
       1    4941    5073
Encroach Node=38934.8
       1    4941    5073
Encroach Node=38512.3
       1  4928.3  5059.6
Encroach Node=38057.0
       1  4928.3  5059.6
Encroach Node=36898.0
       1  4922.4  5057.6
Encroach Node=35826.0
       1    4880  5046.7
Encroach Node=35246.0
       1    4900    5079
Encroach Node=35010.9
       1    4950    5070
Encroach Node=34905.4
       1    4935    5072
Encroach Node=34841.0
       1    4935    5072
Encroach Node=34776.6
       1    4935    5072
Encroach Node=34417.0
       1    4922    5100
Encroach Node=33867.0
       1  4943.8    5135
Encroach Node=32787.0
       1  4936.5    5100
Encroach Node=31729.0
       1  4954.9    5071
Encroach Node=31199.0
       1  4943.1    5180
Encroach Node=30834.4
       1  4961.6  5064.2
Encroach Node=30741.5
       1 4896.36 5120.55
Encroach Node=30712.0
       1 4896.36 5120.55
Encroach Node=30682.5
       1 4896.36 5120.55
Encroach Node=30217.0
       1  4927.2    5130
Encroach Node=29239.0
       1  4944.1 5246.64
Encroach Node=28433.0
       1  4944.6 5141.35
Encroach Node=28255.5
       1    4880    5140
Encroach Node=28244.0
       1    4880    5140
Encroach Node=28232.5
       1    4880    5140
Encroach Node=27803.5
       1    4880    5140
Encroach Node=27792.0
       1    4880    5140
Encroach Node=27780.5
       1    4880    5140
Encroach Node=27198.4
       1    4940    5185
Encroach Node=26989.1
       1    4880    5093
Encroach Node=26974.0
       1    4880    5093
Encroach Node=26958.9
       1    4880    5093
Encroach Node=26748.3
       1    4908    5310
Encroach Node=26717.0
       1    4928    5310
Encroach Node=26685.7
       1    4908    5310
Encroach Node=26390.5
       1    4850    5130
Encroach Node=26379.0
       1    4850    5130
Encroach Node=26367.5
       1    4850    5130
Encroach Node=25919.5
       1    4860    5140
Encroach Node=25908.0
       1    4860    5140
Encroach Node=25896.5
       1    4860    5140
Encroach Node=24592.0
       1    4930    5225
Encroach Node=24343.7
       1    4940    5185
Encroach Node=24159.3
       1    4900    5120
Encroach Node=24126.0
       1    4900    5120
Encroach Node=24092.7
       1    4900    5120
Encroach Node=23934.0
       1    4886    5145
Encroach Node=23835.0
       1    4886    5130
Encroach Node=23736.0
       1    4830    5155
Encroach Node=23728.3
       1    4800    5150
Encroach Node=23691.0
       1    4800    5150
Encroach Node=23653.7
       1    4800    5150
Encroach Node=23117.0
       1    4900    5170
Encroach Node=22741.0
       1    4920    5150
Encroach Node=22003.2
       1    4830    5050
Encroach Node=21894.0
       1    4900    5050
Encroach Node=21866.0
       1    4900    5050
Encroach Node=21838.0
       1    4900    5050
Encroach Node=21368.6
       1    4800    5055
Encroach Node=21128.0
       1    4800    5055
Encroach Node=20968.0
       1    4940    5055
Encroach Node=20948.0
       1    4940    5055
Encroach Node=20928.0
       1    4940    5055
Encroach Node=20345.4
       1    4700    5039
Encroach Node=20014.0
       1    4800    5081
Encroach Node=18968.0
       1    4500    5105
Encroach Node=18117.0
       1    4680    5245
Encroach Node=17108.0
       1    4845    5400
Encroach Node=16002.0
       1    4875    5275
Encroach Node=14723.0
       1    4700    5200
Encroach Node=13984.0
       1    4750    5300
Encroach Node=12968.0
       1    4475    5230
Encroach Node=11816.0
       1  4937.5  5444.3
Encroach Node=11600.8
       1    4890    5110
Encroach Node=11570.0
       1    4890    5110
Encroach Node=11539.2
       1    4890    5110
Encroach Node=10683.7
       1  4839.2  5119.2
Encroach Node=10189.0
       1  4812.7  5175.4
Encroach Node=9283.0
       1  4812.9  5175.6
Encroach Node=7760.7
       1  4813.1  5251.3
Encroach Node=5945.8
       1  4771.3  5201.3
Encroach Node=4636.0
       1  4819.6  5197.7
Encroach Node=2934.1
       1  4847.9  5147.9
Encroach Node=1727.0
       1  4801.2  5195.1
BEGIN DESCRIPTION:
FEMA Effective Floodway June 2007 + LOMR 13-06-4399P
END DESCRIPTION:
Computation Interval=1HOUR
Output Interval=1HOUR
Run HTab= 0
Run UNet= 0
Run PostProcess= 0
UNET Theta= 1
UNET ZTol= 0.02
UNET ZSATol= 0.1
UNET MxIter= 20
UNET MaxInSteps= 20
UNET DtIC= 0
UNET DtMin= 0
UNET MaxCRTS= 20
UNET WFStab= 2
UNET SFStab= 1
UNET WFX= 1
UNET SFX= 1
UNET Convert EG Bridges=-1
UNET Use Existing IB Tables=-1
Instantaneous Interval=1HOUR
Write IC File= 0
IC Time=0
Write Velocity= 0
Write Detailed= 0

--- N100-00-00.p01 (plan) ---

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Plan Title=Effective Multi-Profile 2014
Short Identifier=Eff+LOMR MP
Geom File=g01
Flow File=f01
Encroach Param=-1 ,0,0, 0
FEMA Effective Multi-Profile June 2007 + LOMR 13-06-4399P

--- N100-00-00.f02 (steady flow) ---

Flow Title=Effective Floodway 2014
Version=Version 3.0.1  Mar 2001
Number of Profiles= 2
Profile Names=1PCT_100yr, 1PCTFloodway_100yr
River Rch & RM=N100-00-00,N100-00-00_0017 ,62721.3
    1906    1906
River Rch & RM=N100-00-00,N100-00-00_0017 ,62129.6
    1915    1915
River Rch & RM=N100-00-00,N100-00-00_0017 ,61078.3
    2001    2001
River Rch & RM=N100-00-00,N100-00-00_0017 ,59945.3
    2101    2101
River Rch & RM=N100-00-00,N100-00-00_0017 ,59016.3
    2808    2808
River Rch & RM=N100-00-00,N100-00-00_0017 ,58044.3
    2893    2893
River Rch & RM=N100-00-00,N100-00-00_0017 ,57372.8
    2990    2990
River Rch & RM=N100-00-00,N100-00-00_0017 ,55969.3
    3075    3075
River Rch & RM=N100-00-00,N100-00-00_0017 ,54729.3
    3184    3184
River Rch & RM=N100-00-00,N100-00-00_0017 ,53782.3
    3078    3078
River Rch & RM=N100-00-00,N100-00-00_0017 ,52799.3
    2950    2950
River Rch & RM=N100-00-00,N100-00-00_0017 ,51728.3
    3344    3344
River Rch & RM=N100-00-00,N100-00-00_0017 ,50887.3
    3389    3389
River Rch & RM=N100-00-00,N100-00-00_0017 ,49887.3
    3443    3443
River Rch & RM=N100-00-00,N100-00-00_0017 ,48919.3
    3496    3496
River Rch & RM=N100-00-00,N100-00-00_0017 ,47941.3
    3551    3551
River Rch & RM=N100-00-00,N100-00-00_0017 ,47014.3
    3604    3604
River Rch & RM=N100-00-00,N100-00-00_0017 ,46172.3
    3652    3652
River Rch & RM=N100-00-00,N100-00-00_0017 ,45272.3
    3705    3705
River Rch & RM=N100-00-00,N100-00-00_0017 ,44027
    3779    3779
River Rch & RM=N100-00-00,N100-00-00_0017 ,42982
    3842    3842
River Rch & RM=N100-00-00,N100-00-00_0017 ,42012
    3956    3956
River Rch & RM=N100-00-00,N100-00-00_0017 ,41004
    4078    4078
River Rch & RM=N100-00-00,N100-00-00_0017 ,39962
    4208    4208
River Rch & RM=N100-00-00,N100-00-00_0017 ,39413
    4278    4278
River Rch & RM=N100-00-00,N100-00-00_0017 ,39003.2
    4331    4331
River Rch & RM=N100-00-00,N100-00-00_0017 ,38057
    4456    4456
River Rch & RM=N100-00-00,N100-00-00_0017 ,35826
    5577    5577
River Rch & RM=N100-00-00,N100-00-00_0017 ,35246
    5911    5911
River Rch & RM=N100-00-00,N100-00-00_0017 ,34905.4
    6117    6117
River Rch & RM=N100-00-00,N100-00-00_0017 ,31729
    6985    6985
River Rch & RM=N100-00-00,N100-00-00_0017 ,31199
    7085    7085
River Rch & RM=N100-00-00,N100-00-00_0017 ,30741.5
    7174    7174
River Rch & RM=N100-00-00,N100-00-00_0017 ,30217
    7276    7276
River Rch & RM=N100-00-00,N100-00-00_0017 ,29239
    7472    7472
River Rch & RM=N100-00-00,N100-00-00_0017 ,28255.5
    7674    7674
River Rch & RM=N100-00-00,N100-00-00_0017 ,25919.5
    8125    8125
River Rch & RM=N100-00-00,N100-00-00_0017 ,24159.3
    8483    8483
River Rch & RM=N100-00-00,N100-00-00_0017 ,23728.3
    8573    8573
River Rch & RM=N100-00-00,N100-00-00_0017 ,22741
    8783    8783
River Rch & RM=N100-00-00,N100-00-00_0017 ,21894
    8967    8967
River Rch & RM=N100-00-00,N100-00-00_0017 ,20968
    9173    9173
River Rch & RM=N100-00-00,N100-00-00_0017 ,20014
    9390    9390
River Rch & RM=N100-00-00,N100-00-00_0017 ,18968
    9633    9633
River Rch & RM=N100-00-00,N100-00-00_0017 ,17108
   10082   10082
River Rch & RM=N100-00-00,N100-00-00_0017 ,16002
   10175   10175
River Rch & RM=N100-00-00,N100-00-00_0017 ,14723
   10283   10283
River Rch & RM=N100-00-00,N100-00-00_0017 ,13984
   10346   10346
River Rch & RM=N100-00-00,N100-00-00_0017 ,12968
   10433   10433
River Rch & RM=N100-00-00,N100-00-00_0017 ,11600.8
   10551   10551
River Rch & RM=N100-00-00,N100-00-00_0017 ,10189
   10675   10675
River Rch & RM=N100-00-00,N100-00-00_0017 ,9283
   10755   10755
River Rch & RM=N100-00-00,N100-00-00_0017 ,4636
   11176   11176
River Rch & RM=N100-00-00,N100-00-00_0017 ,1727.0
   11448   11448
Boundary for River Rch & Prof#=N100-00-00,N100-00-00_0017 , 1
Up Type= 0
Dn Type= 3
Dn Slope=.00006
Boundary for River Rch & Prof#=N100-00-00,N100-00-00_0017 , 2
Up Type= 0
Dn Type= 1
Dn Known WS=7.67
DSS Import GetInterval= 0
DSS Import GetPeak= 0
DSS Import FillOption= 0

--- N100-00-00.f01 (steady flow) ---

Flow Title=Effective Multi-Profile 2014
Version=Version 3.0.1  Mar 2001
Number of Profiles= 4
Profile Names=10PCT_10yr, 2PCT_50yr, 1PCT_100yr, 0.2PCT_500yr
River Rch & RM=N100-00-00,N100-00-00_0017 ,62721.3
    1110    1622    1906    2753
River Rch & RM=N100-00-00,N100-00-00_0017 ,62129.6
    1116    1631    1915    2767
River Rch & RM=N100-00-00,N100-00-00_0017 ,61078.3
    1164    1704    2001    2895
River Rch & RM=N100-00-00,N100-00-00_0017 ,59945.3
    1219    1788    2101    3042
River Rch & RM=N100-00-00,N100-00-00_0017 ,59016.3
    1620    2390    2808    3912
River Rch & RM=N100-00-00,N100-00-00_0017 ,58044.3
    1668    2463    2893    4039
River Rch & RM=N100-00-00,N100-00-00_0017 ,57372.8
    1721    2545    2990    4182
River Rch & RM=N100-00-00,N100-00-00_0017 ,55969.3
    1769    2617    3075    4309
River Rch & RM=N100-00-00,N100-00-00_0017 ,54729.3
    1829    2710    3184    4470
River Rch & RM=N100-00-00,N100-00-00_0017 ,53782.3
    1759    2616    3078    4386
River Rch & RM=N100-00-00,N100-00-00_0017 ,52799.3
    1695    2510    2950    4254
River Rch & RM=N100-00-00,N100-00-00_0017 ,51728.3
    1918    2872    3344    4724
River Rch & RM=N100-00-00,N100-00-00_0017 ,50887.3
    1949    2914    3389    4741
River Rch & RM=N100-00-00,N100-00-00_0017 ,49887.3
    1986    2964    3443    4761
River Rch & RM=N100-00-00,N100-00-00_0017 ,48919.3
    2023    3014    3496    4781
River Rch & RM=N100-00-00,N100-00-00_0017 ,47941.3
    2062    3066    3551    4801
River Rch & RM=N100-00-00,N100-00-00_0017 ,47014.3
    2098    3115    3604    4820
River Rch & RM=N100-00-00,N100-00-00_0017 ,46172.3
    2132    3161    3652    4837
River Rch & RM=N100-00-00,N100-00-00_0017 ,45272.3
    2169    3210    3705    4856
River Rch & RM=N100-00-00,N100-00-00_0017 ,44027
    2222    3280    3779    4881
River Rch & RM=N100-00-00,N100-00-00_0017 ,42982
    2267    3340    3842    4903
River Rch & RM=N100-00-00,N100-00-00_0017 ,42012
    2331    3456    3956    5087
River Rch & RM=N100-00-00,N100-00-00_0017 ,41004
    2399    3581    4078    5286
River Rch & RM=N100-00-00,N100-00-00_0017 ,39962
    2472    3714    4208    5500
River Rch & RM=N100-00-00,N100-00-00_0017 ,39413
    2512    3787    4278    5617
River Rch & RM=N100-00-00,N100-00-00_0017 ,39003.2
    2541    3842    4331    5705
River Rch & RM=N100-00-00,N100-00-00_0017 ,38057
    2611    3972    4456    5914
River Rch & RM=N100-00-00,N100-00-00_0017 ,35826
    3135    4769    5577    7925
River Rch & RM=N100-00-00,N100-00-00_0017 ,35246
    3287    5001    5911    8552
River Rch & RM=N100-00-00,N100-00-00_0017 ,34905.4
    3380    5143    6117    8942
River Rch & RM=N100-00-00,N100-00-00_0017 ,31729
    4035    5972    6985   10192
River Rch & RM=N100-00-00,N100-00-00_0017 ,31199
    4096    6063    7085   10333
River Rch & RM=N100-00-00,N100-00-00_0017 ,30741.5
    4150    6143    7174   10456
River Rch & RM=N100-00-00,N100-00-00_0017 ,30217
    4212    6235    7276   10599
River Rch & RM=N100-00-00,N100-00-00_0017 ,29239
    4331    6411    7472   10871
River Rch & RM=N100-00-00,N100-00-00_0017 ,28255.5
    4453    6594    7674   11151
River Rch & RM=N100-00-00,N100-00-00_0017 ,25919.5
    4691    6981    8125   11757
River Rch & RM=N100-00-00,N100-00-00_0017 ,24159.3
    4878    7287    8483   12236
River Rch & RM=N100-00-00,N100-00-00_0017 ,23728.3
    4925    7365    8573   12356
River Rch & RM=N100-00-00,N100-00-00_0017 ,22741
    5034    7544    8783   12635
River Rch & RM=N100-00-00,N100-00-00_0017 ,21894
    5130    7702    8967   12880
River Rch & RM=N100-00-00,N100-00-00_0017 ,20968
    5237    7878    9173   13153
River Rch & RM=N100-00-00,N100-00-00_0017 ,20014
    5349    8064    9390   13441
River Rch & RM=N100-00-00,N100-00-00_0017 ,18968
    5475    8272    9633   13763
River Rch & RM=N100-00-00,N100-00-00_0017 ,17108
    5707    8657   10082   14356
River Rch & RM=N100-00-00,N100-00-00_0017 ,16002
    5750    8732   10175   14472
River Rch & RM=N100-00-00,N100-00-00_0017 ,14723
    5801    8819   10283   14609
River Rch & RM=N100-00-00,N100-00-00_0017 ,13984
    5831    8870   10346   14688
River Rch & RM=N100-00-00,N100-00-00_0017 ,12968
    5872    8940   10433   14797
River Rch & RM=N100-00-00,N100-00-00_0017 ,11600.8
    5927    9036   10551   14946
River Rch & RM=N100-00-00,N100-00-00_0017 ,10189
    5985    9136   10675   15102
River Rch & RM=N100-00-00,N100-00-00_0017 ,9283
    6022    9201   10755   15202
River Rch & RM=N100-00-00,N100-00-00_0017 ,4636
    6218    9540   11176   15728
River Rch & RM=N100-00-00,N100-00-00_0017 ,1727.0
    6343    9758   11448   16067
Boundary for River Rch & Prof#=N100-00-00,N100-00-00_0017 , 1
Up Type= 0
Dn Type= 3
Dn Slope=.00006
Boundary for River Rch & Prof#=N100-00-00,N100-00-00_0017 , 2
Up Type= 0
Dn Type= 3
Dn Slope=.00006
Boundary for River Rch & Prof#=N100-00-00,N100-00-00_0017 , 3
Up Type= 0
Dn Type= 3
Dn Slope=.00006
Boundary for River Rch & Prof#=N100-00-00,N100-00-00_0017 , 4
Up Type= 0
Dn Type= 3
Dn Slope=.00006
DSS Import GetInterval= 0
DSS Import GetPeak= 0
DSS Import FillOption= 0

--- N100-00-00.g01 (geometry) ---

Geom Title=N100-00-00 2011
Version=Version 3.0.1  Mar 2001

River Reach=N100-00-00      ,N100-00-00_0017
Reach XY= 30
      3173526.39   13900678.8967   3174096.68928    13900289.032
   3174678.99296   13896514.8242   3173485.82573   13895369.5969
   3175500.65563   13894870.5924   3175987.30663   13892687.0101
   3177509.25015   13890371.0004   3176325.50087   13887390.0006
   3181449.99919   13881730.9993   3184532.50121   13875502.9996
   3186197.74888   13870285.0004   3186920.74961   13865978.9992
   3185297.74874   13863826.9995   3187166.75091    13861084.999
   3185703.50018   13860072.9992    3187570.5005   13858771.0008
   3186126.25077    13856066.001        3188371.   13852539.9999
   3187084.24994   13848741.0015   3192381.50109   13848029.0002
   3193616.24996   13846745.0013   3195268.49992   13846472.9994
   3195366.50039   13845427.9989   3197067.75094   13845725.9988
   3197047.24909    13843973.999   3197819.25292   13843267.0002
   3198955.50105   13844153.9997    3200650.5018   13844139.0003
   3202113.50101   13845475.0008     3207862.001   13842854.9999

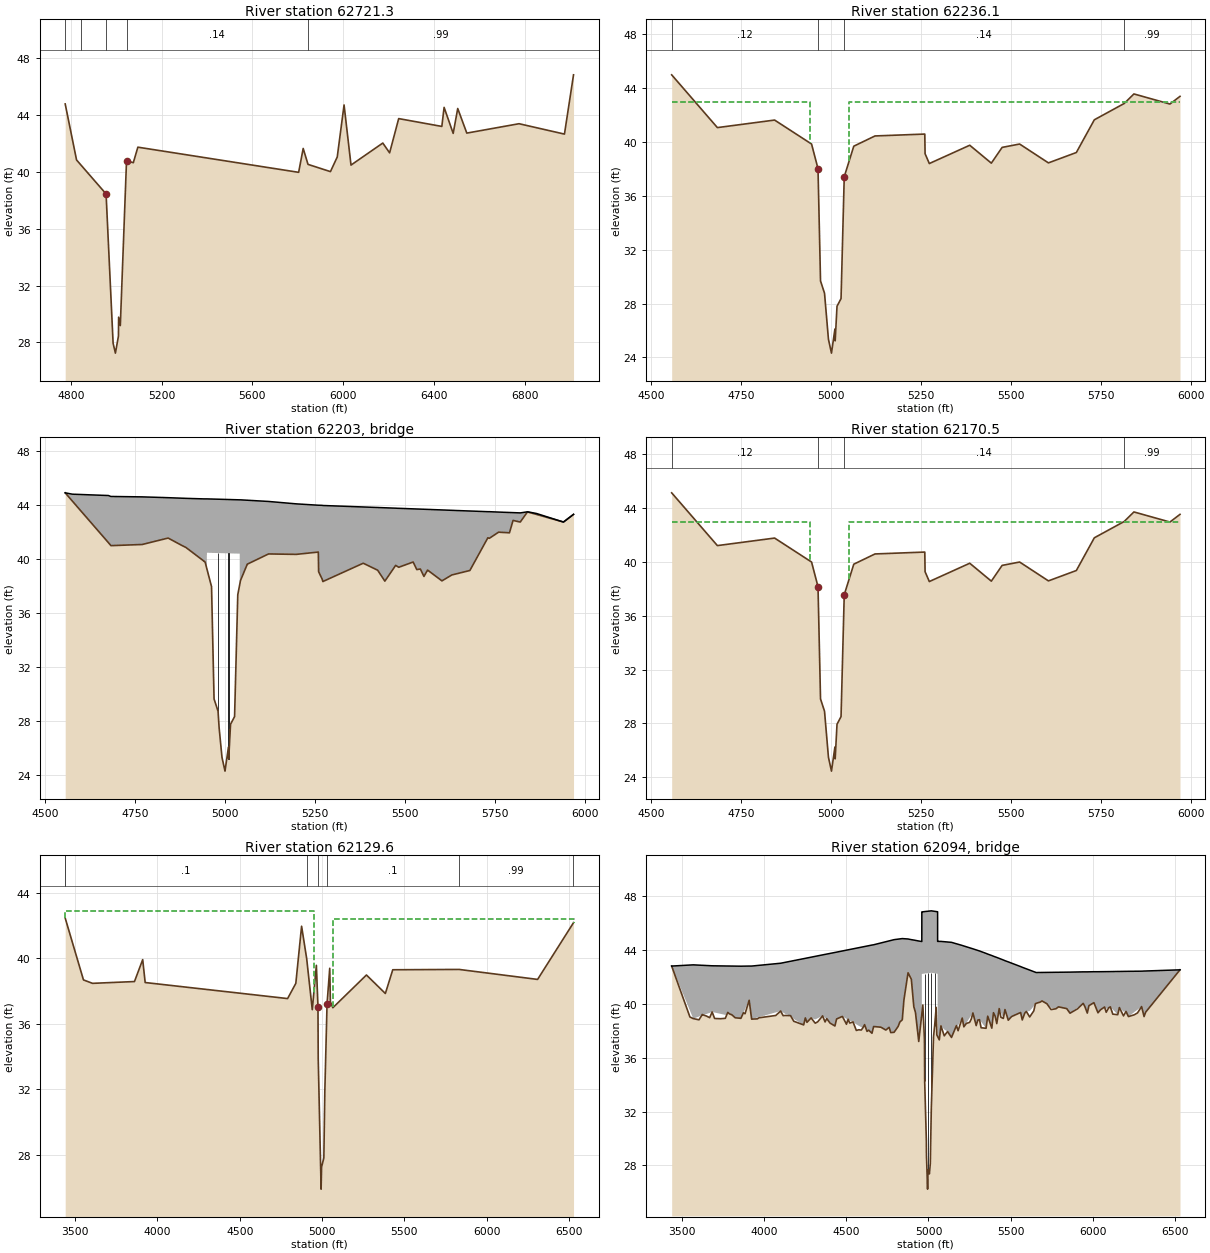
Type RM Length L Ch R = 1 ,62721.3 ,429.2,485.2,425
BEGIN DESCRIPTION:
Previously 63088 Cross Section 63088 - Interpolated
END DESCRIPTION:
XS GIS Cut Line= 4
      3183523.49     13877751.28      3183151.32     13877517.98
      3182448.72     13877155.34      3181581.98     13876639.19
#Sta/Elev= 30
  4775.7   44.78  4825.7   40.84  4843.6   40.51  4955.7   38.45  4986.7   27.94
  4996.8   27.25  5010.2   28.45    5011   29.78  5018.4   29.19  5045.7   40.77
  5075.7   40.65  5095.7   41.74  5803.8   39.97  5823.8   41.65    5845   40.53
  5943.8   40.02  5973.8   41.05  6003.8   44.71  6034.4   40.48  6174.4   42.03
  6204.4   41.34  6244.4   43.75  6434.4    43.2  6444.4   44.54  6484.4   42.71
  6504.4   44.46  6544.4   42.73  6774.4   43.39  6974.4   42.66  7014.4   46.83
#Mann= 5 ,-1 , 0
  4775.7     .07       0  4843.6     .14       0  4955.7     .04       0
  5045.7     .14       0    5845     .99       0
Bank Sta=4955.7,5045.7
XS Rating Curve= 0
Exp/Cntr=.5,.3

Type RM Length L Ch R = 1 ,62236.1 ,65.6,65.6,65.6
BEGIN DESCRIPTION:
Upstream Section of Bridge/Culvert/Weir. Previously 62602.8
END DESCRIPTION:
XS GIS Cut Line= 5
      3183906.55     13877404.93       3183620.5     13877250.63
      3183354.85     13877104.02      3182863.15      13876841.7
      3182662.33     13876736.57
#Sta/Elev= 30
  4556.5   44.99  4683.5   41.07  4842.5   41.63  4945.2   39.85  4963.1   38.02
  4970.1   29.68  4981.2   28.77  4992.1   25.35  5000.5   24.32  5010.1   26.11
  5010.8   25.23  5015.9    27.8  5027.1   28.37    5036   37.42  5062.5   39.69
  5121.5   40.45  5259.8   40.59  5260.6   39.13  5272.4    38.4  5384.7   39.76
  5444.7   38.43  5474.7    39.6  5523.3   39.85  5603.3   38.45  5680.9   39.22
  5730.9   41.65  5813.8   42.86  5840.9   43.57  5940.9   42.82  5968.9   43.39
#Mann= 4 ,-1 , 0
  4556.5     .12       0  4963.1     .04       0    5036     .14       0
  5813.8     .99       0
#XS Ineff= 2 , 0
       0    4940      43    5050       0      43
Permanent Ineff=
       F       F
Bank Sta=4963.1,5036
XS Rating Curve= 0
Exp/Cntr=.5,.3

Type RM Length L Ch R = 3 ,62203   ,,,
BEGIN DESCRIPTION:
SOUTHERN PACIFIC RAILROAD (Previously 62570.0)
Structure ID: N00-38
END DESCRIPTION:
Bridge Culvert--1,0,-1,-1, 0
Deck Dist Width WeirC Skew NumUp NumDn MinLoCord MaxHiCord MaxSubmerge Is_Ogee
10,45.6,2.6,0, 44, 44, , , .95, 0, 1,1,,
  4556.5  4576.5  4676.5  4683.5  4770.1  4842.5    4892  4942.4  4945.2 4950.11
  4950.2 5041.39  5041.5  5043.6  5062.5  5121.5  5199.1  5259.8  5260.6  5270.6
  5272.4  5384.7  5424.7  5444.7  5474.7  5483.3  5523.3  5533.3  5543.3  5553.3
  5563.3  5603.3  5630.9  5680.9  5730.9    5735  5760.9  5790.9  5800.9  5820.9
  5840.9  5865.5  5940.9  5968.9
   44.93   44.83   44.73   44.66   44.63   44.57   44.52   44.48   44.48   44.48
   44.48   44.41   44.41   44.41   44.38   44.29   44.11   44.01   44.01      44
   43.99   43.88   43.84   43.82   43.79   43.78   43.74   43.73   43.72   43.71
    43.7   43.66   43.63   43.58   43.53   43.53    43.5   43.47   43.46   43.44
   43.52    43.4   42.76   43.33
   44.93   44.31   41.23   41.01   41.09   41.57   40.87   39.85   39.79   39.29
   40.48   40.41   38.13   38.42   39.63   40.39   40.36   40.53   39.07   38.51
   38.34    39.7   39.18   38.37   39.54    39.4   39.79   39.23   39.27   38.72
   39.19   38.39   38.83   39.16   41.59   41.55   42.01   41.96   42.88   42.76
   43.51   43.33   42.76   43.33
  4556.5  4576.5  4676.5  4683.5  4770.1  4842.5    4892  4942.4  4945.2 4950.11
  4950.2 5041.39  5041.5  5043.6  5062.5  5121.5  5199.1  5259.8  5260.6  5270.6
  5272.4  5384.7  5424.7  5444.7  5474.7  5483.3  5523.3  5533.3  5543.3  5553.3
  5563.3  5603.3  5630.9  5680.9  5730.9    5735  5760.9  5790.9  5800.9  5820.9
  5840.9  5865.5  5940.9  5968.9
   44.93   44.83   44.73   44.66   44.63   44.57   44.52   44.48   44.48   44.48
   44.48   44.41   44.41   44.41   44.38   44.29   44.11   44.01   44.01      44
   43.99   43.88   43.84   43.82   43.79   43.78   43.74   43.73   43.72   43.71
    43.7   43.66   43.63   43.58   43.53   43.53    43.5   43.47   43.46   43.44
   43.52    43.4   42.76   43.33
   44.79   44.17   41.09   40.87   40.95   41.43   40.73   39.71   39.65   39.15
   40.34   40.27   37.99   38.28   39.49   40.25   40.22   40.39   38.93   38.37
    38.2   39.56   39.04   38.23    39.4   39.26   39.65   39.09   39.13   38.58
   39.05   38.25   38.69   39.02   41.45   41.41   41.87   41.82   42.74   42.62
   43.37   43.19   42.62   43.19
Pier Skew, UpSta & Num, DnSta & Num=  ,4981.2, 2 ,4981.2, 2 , 0 , 0 , 0 ,,
       2       2
   27.29   41.48
       2       2
   27.15   41.34
Pier Skew, UpSta & Num, DnSta & Num=  ,5010.8, 2 ,5010.8, 2 , 0 , 0 , 0 ,,
       2       2
   24.67   41.47
       2       2
   24.53   41.33
BR Coef= 1 , 1 , 0 ,1.25, 0 ,,,.8,0,2,0,
WSPro=,,,, 1 ,,,, 0 ,,,, 0 ,,,,-1 ,-1 ,-1 , 0 , 0 , 0 , 0 , 0
BR U #Sta/Elev= 76
  4556.5   44.93  4576.5   44.31  4676.5   41.23  4683.5   41.01  4686.8   41.01
  4768.8   41.09  4770.1   41.09  4842.5   41.57  4881.4   41.01    4892   40.87
 4942.29   39.85  4942.4   39.85 4942.51   39.84  4945.2   39.79  4946.2   39.69
 4950.11   39.29  4950.2   39.28  4950.3   39.27  4963.1   37.96  4970.1   29.62
  4981.2   28.71  4984.1    27.5  4992.1   25.29  5000.5   24.26  5001.5   24.45
  5010.1   26.05  5010.8   25.17  5015.9   27.74  5027.1   28.31    5036   37.36
  5041.3    38.1 5041.39   38.11  5041.5   38.13  5043.6   38.42 5061.99    39.6
  5062.1    39.6 5062.21   39.61  5062.5   39.63  5121.5   40.39  5121.8   40.39
    5196   40.36  5199.1   40.36  5259.8   40.53  5260.6   39.07  5265.8   38.78
  5270.6   38.51  5272.4   38.34  5365.5   39.47  5384.7    39.7  5424.7   39.18
  5444.7   38.37  5465.5   39.18  5474.7   39.54  5483.3    39.4  5523.3   39.79
  5533.3   39.23  5543.3   39.27  5553.3   38.72  5563.3   39.19  5565.5   39.15
  5603.3   38.39  5630.9   38.83  5665.5   39.06  5680.9   39.16  5730.9   41.59
    5735   41.55  5760.9   42.01  5765.5      42  5790.9   41.96  5800.9   42.88
  5813.8    42.8  5820.9   42.76  5840.9   43.51  5865.5   43.33  5940.9   42.76
  5968.9   43.33
BR U #Mann= 4
  4556.5     .12  4963.1     .04    5036     .14  5813.8     .99
BR U Banks=4963.1,5036
BR D #Sta/Elev= 76
  4556.5   44.79  4576.5   44.17  4676.5   41.09  4683.5   40.87  4686.8   40.87
  4768.8   40.95  4770.1   40.95  4842.5   41.43  4881.4   40.87    4892   40.73
 4942.29   39.71  4942.4   39.71 4942.51    39.7  4945.2   39.65  4946.2   39.55
 4950.11   39.15  4950.2   39.14  4950.3   39.13  4963.1   37.82  4970.1   29.48
  4981.2   28.57  4984.1   27.36  4992.1   25.15  5000.5   24.12  5001.5   24.31
  5010.1   25.91  5010.8   25.03  5015.9    27.6  5027.1   28.17    5036   37.22
  5041.3   37.96 5041.39   37.97  5041.5   37.99  5043.6   38.28 5061.99   39.46
  5062.1   39.46 5062.21   39.47  5062.5   39.49  5121.5   40.25  5121.8   40.25
    5196   40.22  5199.1   40.22  5259.8   40.39  5260.6   38.93  5265.8   38.64
  5270.6   38.37  5272.4    38.2  5365.5   39.33  5384.7   39.56  5424.7   39.04
  5444.7   38.23  5465.5   39.04  5474.7    39.4  5483.3   39.26  5523.3   39.65
  5533.3   39.09  5543.3   39.13  5553.3   38.58  5563.3   39.05  5565.5   39.01
  5603.3   38.25  5630.9   38.69  5665.5   38.92  5680.9   39.02  5730.9   41.45
    5735   41.41  5760.9   41.87  5765.5   41.86  5790.9   41.82  5800.9   42.74
  5813.8   42.66  5820.9   42.62  5840.9   43.37  5865.5   43.19  5940.9   42.62
  5968.9   43.19
BR D #Mann= 4
  4556.5     .12  4963.1     .04    5036     .14  5813.8     .99
BR D Banks=4963.1,5036
BC Design=,, 0 ,, 0 ,,,,,,
BC HTab HWMax=44.99

Type RM Length L Ch R = 1 ,62170.5 ,40.9,40.9,40.9
BEGIN DESCRIPTION:
Downstream Section of Bridge/Culvert/Weir. Previously 62537.2
END DESCRIPTION:
XS GIS Cut Line= 5
      3183967.51     13877380.68      3183681.46     13877226.39
      3183415.81     13877079.78      3182924.11     13876817.46
      3182723.29     13876712.33
#Sta/Elev= 30
  4556.5   45.13  4683.5   41.21  4842.5   41.77  4945.2   39.99  4963.1   38.16
  4970.1   29.82  4981.2   28.91  4992.1   25.49  5000.5   24.46  5010.1   26.25
  5010.8   25.37  5015.9   27.94  5027.1   28.51    5036   37.56  5062.5   39.83
  5121.5   40.59  5259.8   40.73  5260.6   39.27  5272.4   38.54  5384.7    39.9
  5444.7   38.57  5474.7   39.74  5523.3   39.99  5603.3   38.59  5680.9   39.36
  5730.9   41.79  5813.8      43  5840.9   43.71  5940.9   42.96  5968.9   43.53
#Mann= 4 ,-1 , 0
  4556.5     .12       0  4963.1     .04       0    5036     .14       0
  5813.8     .99       0
#XS Ineff= 2 , 0
       0    4940      43    5050       0      43
Permanent Ineff=
       F       F
Bank Sta=4963.1,5036
XS Rating Curve= 0
Exp/Cntr=.5,.3

Type RM Length L Ch R = 1 ,62129.6 ,70.6,70.6,70.6
BEGIN DESCRIPTION:
Upstream Section of Bridge/Culvert/Weir. Previously 62496.3
END DESCRIPTION:
XS GIS Cut Line= 4
      3184958.45      13877860.2      3184276.09     13877493.83
       3183286.9     13876967.18       3182233.6     13876403.89
#Sta/Elev= 30
  3439.2   42.46  3439.4   42.45  3550.2   38.68  3605.2   38.47  3860.2   38.58
  3910.2   39.92  3925.2   38.52  4790.9   37.54  4840.9   38.47  4875.9   41.96
  4906.9   39.98  4940.9   36.86  4965.8   39.57  4975.5   37.04    4977    33.9
  4994.6    25.9  4997.3   27.25  5011.2    27.8  5017.2   31.88  5030.7   37.21
    5047   39.39  5050.9   37.35  5065.9   36.98  5270.1   38.98  5385.1   37.85
  5430.1    39.3  5832.8   39.32  6310.4   38.71  6528.4   42.17  6528.8   42.18
#Mann= 7 ,-1 , 0
  3439.2      .2       0  3439.4      .1       0  4906.9     .12       0
  4975.5     .04       0  5030.7      .1       0  5832.8     .99       0
  6528.4      .2       0
#XS Ineff= 2 , 0
       0    4950    42.9    5065       0    42.4
Permanent Ineff=
       F       F
Bank Sta=4975.5,5030.7
XS Rating Curve= 0
Exp/Cntr=.5,.3

Type RM Length L Ch R = 3 ,62094   ,,,
BEGIN DESCRIPTION:
BEAUMONT HWY (Previously 62461.0)
Structure ID: N00-37
END DESCRIPTION:
Bridge Culvert--1,0,-1,-1, 0
Deck Dist Width WeirC Skew NumUp NumDn MinLoCord MaxHiCord MaxSubmerge Is_Ogee
10,50.6,2.6,0, 60, 60, , , .95, 0, 1,1,,
  3439.2  3570.2  3685.2  3860.2  3910.2  3925.2  4101.6  4241.6  4356.6  4431.6
  4476.6  4656.6  4666.6  4790.9  4840.9  4875.9  4895.9  4910.9  4940.9 4959.47
 4959.58 4959.81  4959.9  5017.2 5055.57 5055.68 5055.79  5055.9  5065.9  5075.9
  5140.1  5205.1  5215.1  5270.1  5290.1  5310.1  5350.1  5360.1  5385.1  5395.1
  5415.1  5430.1  5455.1  5465.1  5485.1  5560.1  5570.1  5654.3  5860.4  5940.4
  5965.4  6005.4  6030.4  6105.4  6150.4  6160.4  6215.4  6295.4  6310.4  6528.8
    42.8   42.89   42.82   42.79    42.8    42.8   43.01   43.35   43.63   43.81
   43.92   44.36   44.38   44.76   44.84   44.81   44.76   44.73   44.66   44.62
   46.82   46.82   46.82    46.9   46.83   44.63   44.63   44.63   44.63   44.63
   44.56   44.33   44.29   44.08      44   43.92   43.74   43.69   43.58   43.53
   43.44   43.37   43.25    43.2   43.11   42.76   42.71   42.32   42.35   42.37
   42.37   42.38   42.38   42.39    42.4    42.4   42.41   42.42   42.43   42.52
    42.8    38.9   39.39   38.92   40.26   38.86   39.46   38.43    39.1   38.35
   39.06   37.81   38.31   37.88   38.81    42.3   41.82   39.78    37.2   39.22
   39.23   39.26   42.22    42.3   42.23   42.23   42.23   37.57   37.32   38.36
    37.5   38.94   38.29   39.32   38.38   38.82   38.18   39.08   38.19   39.34
   38.53   39.64   38.91   39.57   38.78   39.35    38.8   40.03    39.3   40.03
   39.31   40.08   39.33   39.77   39.19   39.72   39.05   39.79   39.05   42.52
  3439.2  3570.2  3685.2  3860.2  3910.2  3925.2  4101.6  4241.6  4356.6  4431.6
  4476.6  4656.6  4666.6  4790.9  4840.9  4875.9  4895.9  4910.9  4940.9 4959.47
 4959.58 4959.81  4959.9  5017.2 5055.57 5055.68 5055.79  5055.9  5065.9  5075.9
  5140.1  5205.1  5215.1  5270.1  5290.1  5310.1  5350.1  5360.1  5385.1  5395.1
  5415.1  5430.1  5440.1  5465.1  5485.1  5560.1  5570.1  5654.3  5860.4  5940.4
  5965.4  6005.4  6030.4  6105.4  6150.4  6160.4  6215.4  6295.4  6310.4  6528.8
    42.8   42.89   42.82   42.79    42.8    42.8   43.01   43.35   43.63   43.81
   43.92   44.36   44.38   44.76   44.84   44.81   44.76   44.73   44.66   44.62
   46.82   46.82   46.82    46.9   46.83   44.63   44.63   44.63   44.63   44.63
   44.56   44.33   44.29   44.08      44   43.92   43.74   43.69   43.58   43.53
   43.44   43.37   43.32    43.2   43.11   42.76   42.71   42.32   42.35   42.37
   42.37   42.38   42.38   42.39    42.4    42.4   42.41   42.42   42.43   42.52
   42.71   38.81    39.3   38.83   40.17   38.77   39.37   38.34   39.01   38.26
   38.97   37.72   38.22   37.79   38.72   42.21   41.73   39.69   37.11   39.13
   39.14   39.17   42.13   42.21   42.14   42.14   42.14   37.48   37.23   38.27
   37.41   38.85    38.2   39.23   38.29   38.73   38.09   38.99    38.1   39.25
   38.44   39.55   38.91   39.48   38.69   39.26   38.71   39.94   39.21   39.94
   39.22   39.99   39.24   39.68    39.1   39.63   38.96    39.7   38.96   42.43
Pier Skew, UpSta & Num, DnSta & Num=  ,4977, 2 ,4977, 2 , 0 , 0 , 0 ,,
     1.4     1.4
   32.94   43.24
     1.4     1.4
   32.85   43.15
Pier Skew, UpSta & Num, DnSta & Num=  ,4997.3, 2 ,4997.3, 2 , 0 , 0 , 0 ,,
     1.4     1.4
   26.24   43.27
     1.4     1.4
   26.15   43.18
Pier Skew, UpSta & Num, DnSta & Num=  ,5017.2, 2 ,5017.2, 2 , 0 , 0 , 0 ,,
     1.4     1.4
    30.7    43.3
     1.4     1.4
   30.61   43.21
Pier Skew, UpSta & Num, DnSta & Num=  ,5037.4, 2 ,5037.4, 2 , 0 , 0 , 0 ,,
     1.4     1.4
   37.27   43.26
     1.4     1.4
   37.18   43.17
Abutment Skew #Up #Dn= , 2 , 2
  4959.7  4987.2
   42.22   29.84
  4959.7  4987.2
   42.13   29.75
Abutment Skew #Up #Dn= , 2 , 2
  5012.5 5055.99
   28.73   42.23
  5012.5 5055.99
   28.64   42.14
BR Coef= 1 , 1 , 0 ,1.25, 0 ,,,.8,0,2,0,
WSPro=,,,, 1 ,,,, 0 ,,,, 0 ,,,,-1 ,-1 ,-1 , 0 , 0 , 0 , 0 , 0
BR U #Sta/Elev= 191
  3439.2    42.8  3439.4   42.79  3550.2   39.02  3570.2    38.9  3605.2   38.81
  3625.2    39.2  3629.2   39.18  3650.2   39.09  3670.2   38.97  3685.2   39.39
  3700.2   38.91  3734.2   38.89  3735.2   38.89  3759.2   38.91  3765.2   38.92
  3769.2   39.04  3780.2   39.36  3790.2   39.25  3805.2   39.18  3825.2   38.96
  3860.2   38.92  3875.2   39.33  3885.2   39.26  3895.2   39.66  3910.2   40.26
  3925.2   38.86  3960.2   38.88  3970.2   38.96  4024.2   39.05  4056.6    39.1
  4071.6   39.13  4101.6   39.46  4116.6   39.12  4131.6   39.13  4161.6   39.12
  4181.6    38.7  4241.6   38.43  4251.6   38.95  4261.6   38.62  4286.6   38.95
  4311.6   38.56  4326.6   38.66  4356.6    39.1  4371.6   38.65  4381.6    38.9
  4401.6   38.57  4431.6   38.35  4441.6   38.87  4476.6   39.06  4486.6   38.84
  4501.6   38.48  4511.6   38.85  4521.6   38.57  4541.6   38.65  4561.6   38.02
  4576.6   38.07  4591.6   38.05  4601.6   38.22  4611.6   38.45  4626.6   37.95
  4636.6   38.04  4656.6   37.81  4666.6   38.31  4675.9    38.3  4691.6   38.28
  4710.9   38.26  4740.9   38.05  4747.1   38.11  4760.9   38.25  4770.9   37.86
  4790.9   37.88  4804.6   38.12  4815.9   38.32  4825.9   38.64  4840.9   38.81
  4850.9   40.28  4857.4   40.81  4875.9    42.3  4895.9   41.82  4906.9   40.32
  4910.9   39.78  4920.9   39.36  4940.9    37.2 4959.47   39.22 4959.58   39.23
 4959.69   39.25 4959.81   39.26  4959.9   39.27  4965.8   39.91  4972.7   38.07
  4975.5   37.38    4977   34.24  4987.1   29.88  4987.2   29.84  4987.9   28.72
  4994.6   26.24  4997.3   27.59  4998.9   27.66  5005.6   27.37  5011.2   28.14
  5012.1   28.74  5012.4   28.73  5012.5   28.73  5016.4   31.63  5017.2   32.22
  5030.7   37.55  5037.4   38.35    5047   39.73  5050.9   37.69 5055.46   37.58
 5055.57   37.57 5055.68   37.57 5055.79   37.57  5055.9   37.57  5065.9   37.32
  5075.9   38.36  5095.9   37.62  5115.9   37.94  5122.8   37.81  5140.1    37.5
  5170.1   38.38  5180.1      38  5187.7   38.29  5205.1   38.94  5215.1   38.29
  5230.1   38.54  5246.8   38.61  5250.1   38.62  5260.1   38.86  5270.1   39.32
  5280.1   38.85  5290.1   38.38  5300.1   38.79  5310.1   38.82  5313.9   38.59
  5320.1   38.22  5350.1   38.18  5360.1   39.08  5385.1   38.19  5395.1   39.34
  5405.1   39.08  5415.1   38.53  5430.1   39.64  5440.1      39  5455.1   38.91
  5465.1   39.57  5485.1   38.78  5505.1   39.05  5560.1   39.35  5570.1    38.8
  5585.1    39.3  5595.1   39.43  5615.1   39.02  5640.1   39.47  5650.1   40.01
  5654.3   40.03  5680.1   40.13  5690.1   40.21  5720.1      40  5745.1   39.57
  5775.1   39.63  5790.4   39.77  5832.8   39.66  5840.4   39.64  5860.4    39.3
  5905.4   39.62  5940.4   40.03  5950.4    39.8  5965.4   39.31  5975.4   39.86
  6005.4   40.08  6030.4   39.33  6045.4   39.55  6070.4   39.76  6080.4   39.37
  6095.4    39.7  6105.4   39.77  6120.4   39.23  6150.4   39.19  6160.4   39.72
  6185.4    39.1  6200.4   39.43  6215.4   39.05  6250.4   39.18  6270.4   39.32
  6295.4   39.79  6310.4   39.05  6320.4   39.38  6399.3   40.57  6528.4   42.51
  6528.8   42.52
BR U #Mann= 7
  3439.2      .2  3439.4      .1  4906.9     .12  4975.5     .04  5030.7      .1
  5832.8     .99  6528.4      .2
BR U Banks=4975.5,5030.7
BR D #Sta/Elev= 191
  3439.2   42.71  3439.4    42.7  3550.2   38.93  3570.2   38.81  3605.2   38.72
  3625.2   39.11  3629.2   39.09  3650.2      39  3670.2   38.88  3685.2    39.3
  3700.2   38.82  3734.2    38.8  3735.2    38.8  3759.2   38.82  3765.2   38.83
  3769.2   38.95  3780.2   39.27  3790.2   39.16  3805.2   39.09  3825.2   38.87
  3860.2   38.83  3875.2   39.24  3885.2   39.17  3895.2   39.57  3910.2   40.17
  3925.2   38.77  3960.2   38.79  3970.2   38.87  4024.2   38.96  4056.6   39.01
  4071.6   39.04  4101.6   39.37  4116.6   39.03  4131.6   39.04  4161.6   39.03
  4181.6   38.61  4241.6   38.34  4251.6   38.86  4261.6   38.53  4286.6   38.86
  4311.6   38.47  4326.6   38.57  4356.6   39.01  4371.6   38.56  4381.6   38.81
  4401.6   38.48  4431.6   38.26  4441.6   38.78  4476.6   38.97  4486.6   38.75
  4501.6   38.39  4511.6   38.76  4521.6   38.48  4541.6   38.56  4561.6   37.93
  4576.6   37.98  4591.6   37.96  4601.6   38.13  4611.6   38.36  4626.6   37.86
  4636.6   37.95  4656.6   37.72  4666.6   38.22  4675.9   38.21  4691.6   38.19
  4710.9   38.17  4740.9   37.96  4747.1   38.02  4760.9   38.16  4770.9   37.77
  4790.9   37.79  4804.6   38.03  4815.9   38.23  4825.9   38.55  4840.9   38.72
  4850.9   40.19  4857.4   40.72  4875.9   42.21  4895.9   41.73  4906.9   40.23
  4910.9   39.69  4920.9   39.27  4940.9   37.11 4959.47   39.13 4959.58   39.14
 4959.69   39.16 4959.81   39.17  4959.9   39.18  4965.8   39.82  4972.7   37.98
  4975.5   37.29    4977   34.15  4987.1   29.79  4987.2   29.75  4987.9   28.63
  4994.6   26.15  4997.3    27.5  4998.9   27.57  5005.6   27.28  5011.2   28.05
  5012.1   28.65  5012.4   28.64  5012.5   28.64  5016.4   31.54  5017.2   32.13
  5030.7   37.46  5037.4   38.26    5047   39.64  5050.9    37.6 5055.46   37.49
 5055.57   37.48 5055.68   37.48 5055.79   37.48  5055.9   37.48  5065.9   37.23
  5075.9   38.27  5095.9   37.53  5115.9   37.85  5122.8   37.72  5140.1   37.41
  5170.1   38.29  5180.1   37.91  5187.7    38.2  5205.1   38.85  5215.1    38.2
  5230.1   38.45  5246.8   38.52  5250.1   38.53  5260.1   38.77  5270.1   39.23
  5280.1   38.76  5290.1   38.29  5300.1    38.7  5310.1   38.73  5313.9    38.5
  5320.1   38.13  5350.1   38.09  5360.1   38.99  5385.1    38.1  5395.1   39.25
  5405.1   38.99  5415.1   38.44  5430.1   39.55  5440.1   38.91  5455.1   38.82
  5465.1   39.48  5485.1   38.69  5505.1   38.96  5560.1   39.26  5570.1   38.71
  5585.1   39.21  5595.1   39.34  5615.1   38.93  5640.1   39.38  5650.1   39.92
  5654.3   39.94  5680.1   40.04  5690.1   40.12  5720.1   39.91  5745.1   39.48
  5775.1   39.54  5790.4   39.68  5832.8   39.57  5840.4   39.55  5860.4   39.21
  5905.4   39.53  5940.4   39.94  5950.4   39.71  5965.4   39.22  5975.4   39.77
  6005.4   39.99  6030.4   39.24  6045.4   39.46  6070.4   39.67  6080.4   39.28
  6095.4   39.61  6105.4   39.68  6120.4   39.14  6150.4    39.1  6160.4   39.63
  6185.4   39.01  6200.4   39.34  6215.4   38.96  6250.4   39.09  6270.4   39.23
  6295.4    39.7  6310.4   38.96  6320.4   39.29  6399.3   40.48  6528.4   42.42
  6528.8   42.43
BR D #Mann= 7
  3439.2      .2  3439.4      .1  4906.9     .12  4975.5     .04  5030.7      .1
  5832.8     .99  6528.4      .2
BR D Banks=4975.5,5030.7
BC Design=,, 0 ,, 0 ,,,,,,
BC HTab HWMax=42.46

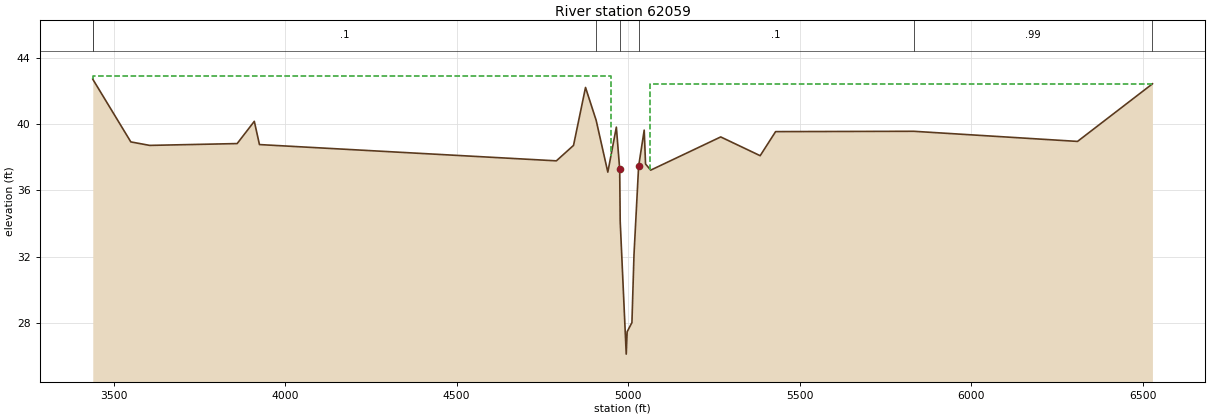
Type RM Length L Ch R = 1 ,62059   ,437.5,437.5,437.5
BEGIN DESCRIPTION:
Downstream Section of Bridge/Culvert/Weir. Previously 62425.7
END DESCRIPTION:
XS GIS Cut Line= 4
      3184987.07     13877795.66      3184304.71     13877429.29
      3183315.52     13876902.64      3182262.22     13876339.35
#Sta/Elev= 30
  3439.2    42.7  3439.4   42.69  3550.2   38.92  3605.2   38.71  3860.2   38.82
  3910.2   40.16  3925.2   38.76  4790.9   37.78  4840.9   38.71  4875.9    42.2
  4906.9   40.22  4940.9    37.1  4965.8   39.81  4975.5   37.28    4977   34.14
  4994.6   26.14  4997.3   27.49  5011.2   28.04  5017.2   32.12  5030.7   37.45
    5047   39.63  5050.9   37.59  5065.9   37.22  5270.1   39.22  5385.1   38.09
  5430.1   39.54  5832.8   39.56  6310.4   38.95  6528.4   42.41  6528.8   42.42
#Mann= 7 ,-1 , 0
  3439.2      .2       0  3439.4      .1       0  4906.9     .12       0
  4975.5     .04       0  5030.7      .1       0  5832.8     .99       0
  6528.4      .2       0
#XS Ineff= 2 , 0
       0    4950    42.9    5065       0    42.4
Permanent Ineff=
       F       F
Bank Sta=4975.5,5030.7
XS Rating Curve= 0
Exp/Cntr=.5,.3