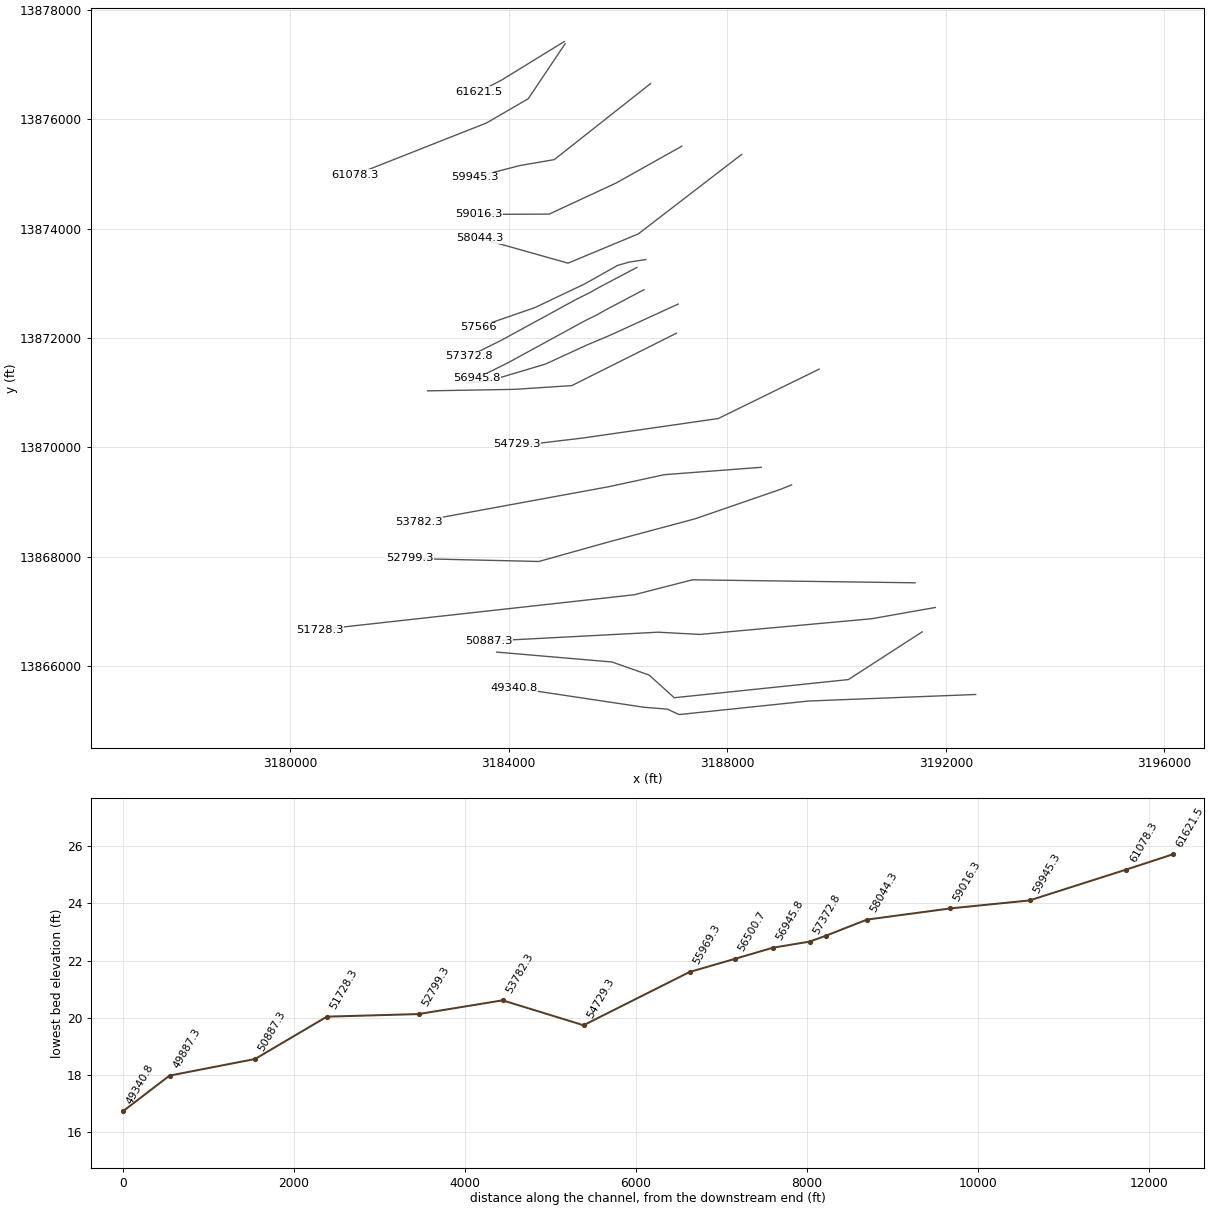
HEC-RAS study N100-00-00.prj: N100-00-00

--- N100-00-00.g01 (geometry) --- (continued)

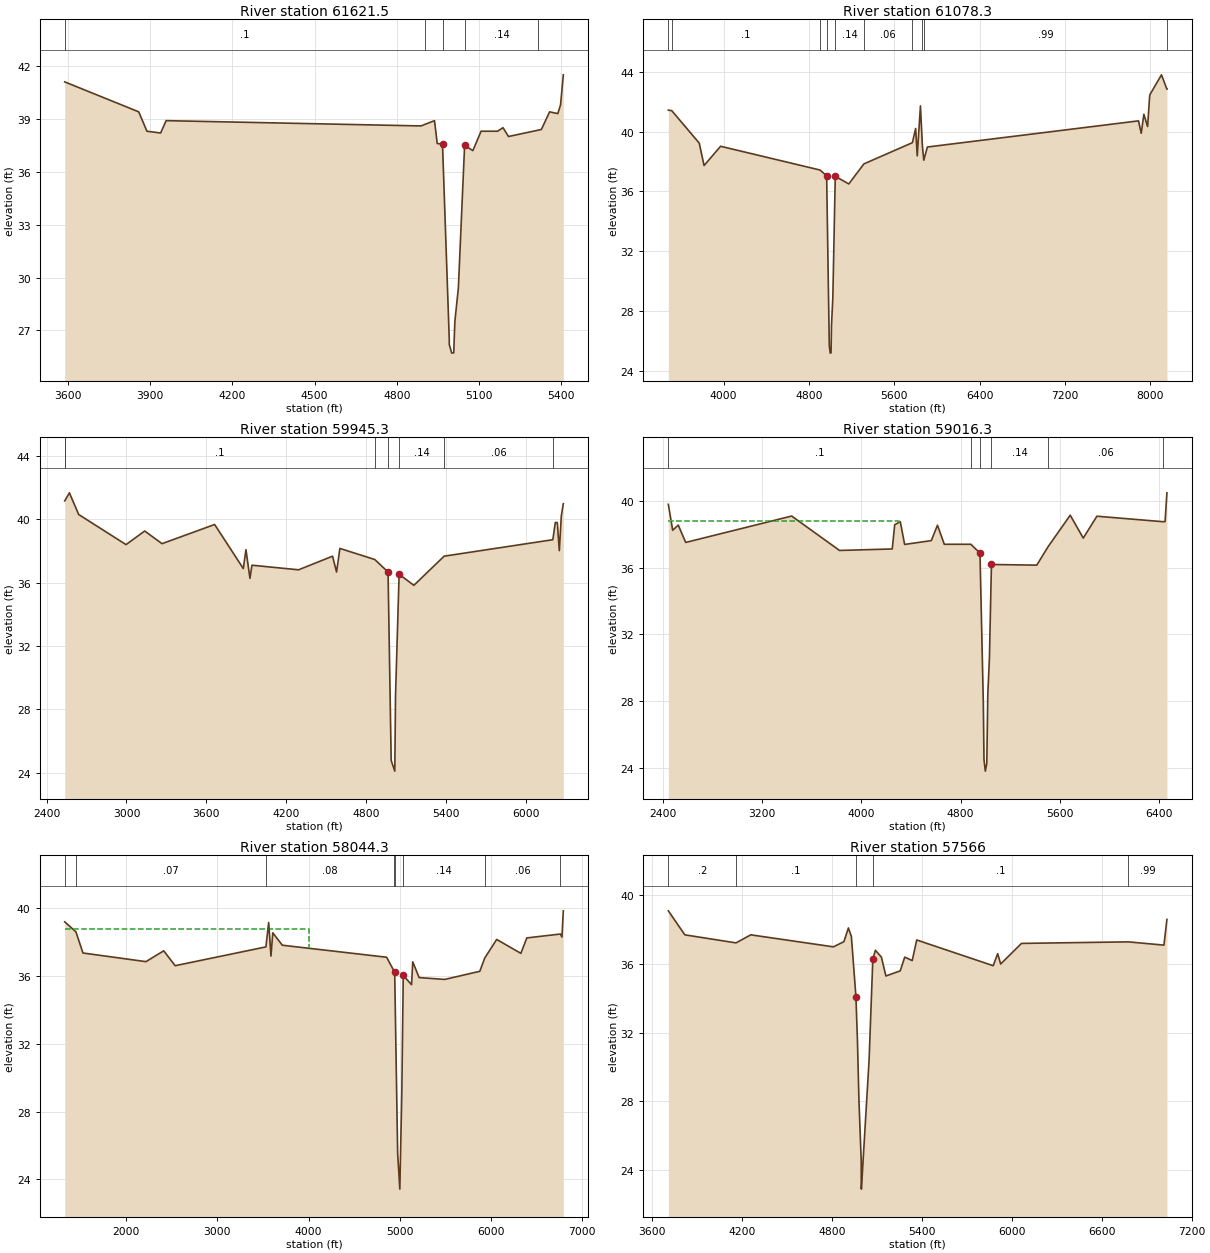
Type RM Length L Ch R = 1 ,61621.5 ,540.6,543.2,546.9
BEGIN DESCRIPTION:
Previously Cross Section 61988.2 - Interpolated
END DESCRIPTION:
XS GIS Cut Line= 3
      3185018.35     13877416.46      3183868.62     13876710.49
      3183450.47     13876495.77
#Sta/Elev= 30
    3588    41.1    3858    39.4    3888    38.3    3938    38.2    3958    38.9
    4888    38.6  4904.3    38.7  4937.2    38.9  4947.2    37.6  4966.4   37.58
  4990.9   26.57  4991.2   26.19  5000.1   25.71  5007.6   25.73  5009.2   26.54
  5011.7   27.54  5024.3   29.41  5047.2   37.54  5057.2    37.4  5077.2    37.2
  5107.2    38.3  5167.2    38.3  5187.2    38.5  5207.2      38  5315.7   38.36
  5327.2    38.4  5357.2    39.4  5387.2    39.3  5397.2    39.8  5407.2    41.5
#Mann= 5 ,-1 , 0
    3588      .1       0  4904.3     .12       0  4966.4     .04       0
  5047.2     .14       0  5315.7     .06       0
Bank Sta=4966.4,5047.2
XS Rating Curve= 0
Exp/Cntr=.3,.1

Type RM Length L Ch R = 1 ,61078.3 ,1169.2,1133,1103.1
BEGIN DESCRIPTION:
Previously Cross Section 61445
Located At: 4TH XS US NEW 90
END DESCRIPTION:
XS GIS Cut Line= 4
      3185034.87     13877376.94      3184358.71     13876371.13
      3183595.98     13875928.63      3181194.42     13874982.34
#Sta/Elev= 30
    3482   41.44  3514.3    41.4    3772   39.23    3817   37.73    3972   39.02
  4904.3   37.43  4966.4   37.05  4991.2   25.66  5000.1   25.18  5007.6    25.2
  5011.7   27.01  5024.3   28.88  5047.2   37.01    5174    36.5  5315.7   37.84
  5770.3   39.26  5800.8   40.21  5815.8   38.38  5845.8   41.72  5864.3   39.02
  5877.3   38.09  5910.8   38.97  7890.8   40.72  7915.8   39.89  7940.8   41.16
  7975.8   40.34  7995.8   42.45  8105.8    43.8  8156.9   42.84    8157   42.84
#Mann= 10 ,-1 , 0
    3482     .99       0  3514.3      .1       0  4904.3     .12       0
  4966.4     .04       0  5047.2     .14       0  5315.7     .06       0
  5770.3     .07       0  5864.3     .12       0  5877.3     .99       0
  8156.9      .2       0
Bank Sta=4966.4,5047.2
XS Rating Curve= 0
Exp/Cntr=.3,.1

Type RM Length L Ch R = 1 ,59945.3 ,902,929,958.4
BEGIN DESCRIPTION:
Previously Cross Section 60312
Located At: 3RD XS US NEW 90
END DESCRIPTION:
XS GIS Cut Line= 5
      3186597.06     13876648.22      3186444.01     13876526.92
      3184836.14     13875259.06      3184206.11      13875150.7
      3183373.71     13874934.47
#Sta/Elev= 30
  2536.6   41.16  2541.6   41.23  2571.6   41.67  2641.6    40.3  2996.9    38.4
  3136.9   39.26  3266.9   38.46  3661.9   39.67  3876.9   36.89  3896.9   38.08
  3926.9   36.27  3941.9    37.1  4291.9   36.81  4546.9   37.67  4576.9   36.67
  4601.9   38.16  4863.8   37.46  4963.4   36.67  4986.9   24.77    5014    24.1
  5019.4   28.84  5046.4   36.53  5157.2   35.83  5384.2   37.67  6200.1   38.71
  6218.8    39.8  6233.8   39.79  6248.8   38.02  6263.8   40.21  6278.8   40.98
#Mann= 7 ,-1 , 0
  2536.6     .99       0  2541.6      .1       0  4863.8     .12       0
  4963.4     .04       0  5046.4     .14       0  5384.2     .06       0
  6200.1     .99       0
Bank Sta=4963.4,5046.4
XS Rating Curve= 0
Exp/Cntr=.3,.1

Type RM Length L Ch R = 1 ,59016.3 ,976.5,972,965.5
BEGIN DESCRIPTION:
Previously Cross Section 59383
Located At: 2ND XS US NEW 90
END DESCRIPTION:
XS GIS Cut Line= 4
      3187169.35     13875504.26      3185964.16     13874829.48
      3184742.98     13874263.44      3183448.02     13874257.15
#Sta/Elev= 30
  2441.9   39.79  2476.9   38.24  2521.9   38.55  2581.9   37.51  3436.9   39.09
  3823.1   37.03  4248.1   37.12  4268.1   38.57  4313.1   38.75  4348.1   37.39
  4563.1   37.62  4613.1   38.54  4668.1    37.4  4882.4    37.4    4956   36.87
  4982.9   27.91  4988.3   24.52    4999   23.82  5010.9   24.28  5019.2   28.45
  5032.2   30.59  5048.4   36.19  5414.1   36.15    5505   37.25  5684.1   39.14
  5789.1   37.77  5899.1   39.08  6434.5   38.75  6449.1   38.76  6464.1   40.48
#Mann= 6 ,-1 , 0
  2441.9      .1       0  4882.4     .12       0    4956     .04       0
  5048.4     .14       0    5505     .06       0  6434.5     .99       0
#XS Ineff= 2 , 0
       0    4300    38.8               0
Permanent Ineff=
       F       F
Bank Sta=4956,5048.4
XS Rating Curve= 0
Exp/Cntr=.3,.1

Type RM Length L Ch R = 1 ,58044.3 ,466.1,478.3,483.1
BEGIN DESCRIPTION:
Previously Cross Section 58411
Located At: 1ST XS US NEW 90
END DESCRIPTION:
XS GIS Cut Line= 5
      3188264.85     13875354.39      3188264.84     13875354.38
      3186373.69     13873901.87       3185086.5      13873366.8
      3183464.55     13873823.54
#Sta/Elev= 30
  1327.9   39.21  1450.7   38.62  1527.9   37.37  2217.9   36.86  2412.9    37.5
  2537.9   36.62  3532.5   37.73  3562.9   39.17  3587.9   37.19  3607.9   38.56
  3712.5   37.83  4855.4   37.12  4934.9   36.32  4943.7   36.23  4976.2   25.55
  4999.9   23.43  5022.1   29.21  5037.5   36.05  5128.7    35.5  5141.5   36.85
  5211.5   35.92  5491.5   35.81  5876.5   36.29  5930.1   37.07  6061.5   38.17
  6326.5   37.35  6391.5   38.26  6759.8   38.49  6776.5   38.31  6791.5   39.86
#Mann= 8 ,-1 , 0
  1327.9     .99       0  1450.7     .07       0  3532.5     .08       0
  4934.9     .14       0  4943.7     .04       0  5037.5     .14       0
  5930.1     .06       0  6759.8     .99       0
#XS Ineff= 2 , 0
       0    4000    38.8               0
Permanent Ineff=
       F       F
Bank Sta=4943.7,5037.5
XS Rating Curve= 0
Exp/Cntr=.3,.1

Type RM Length L Ch R = 1 ,57566   ,90.4,193.2,102.6
BEGIN DESCRIPTION:
Previously Cross Section 57932.7 - Interpolated
END DESCRIPTION:
XS GIS Cut Line= 6
      3186510.98     13873432.75      3186201.69     13873385.69
      3185993.26     13873325.18      3185381.42     13872982.27
      3184473.74     13872551.97      3183443.31     13872196.53
#Sta/Elev= 30
  3708.7    39.1  3818.7    37.7  4160.3   37.23  4258.6    37.7  4809.8      37
  4879.8    37.3  4909.8    38.1  4929.8    37.6    4960    34.1    4970    31.6
    4980    28.1  4995.3   24.51  4995.6   22.97  4996.5   22.87  5047.8   30.39
  5072.8    36.3    5090    36.8    5130    36.4    5160    35.3  5255.6    35.6
  5285.6    36.4  5335.6    36.2  5365.6    37.4  5875.6    35.9  5905.6    36.6
  5925.6      36  6064.6    37.2  6776.3   37.29  7014.6    37.1  7034.6    38.6
#Mann= 5 ,-1 , 0
  3708.7      .2       0  4160.3      .1       0    4960     .04       0
  5072.8      .1       0  6776.3     .99       0
Bank Sta=4960,5072.8
XS Rating Curve= 0
Exp/Cntr=.5,.3

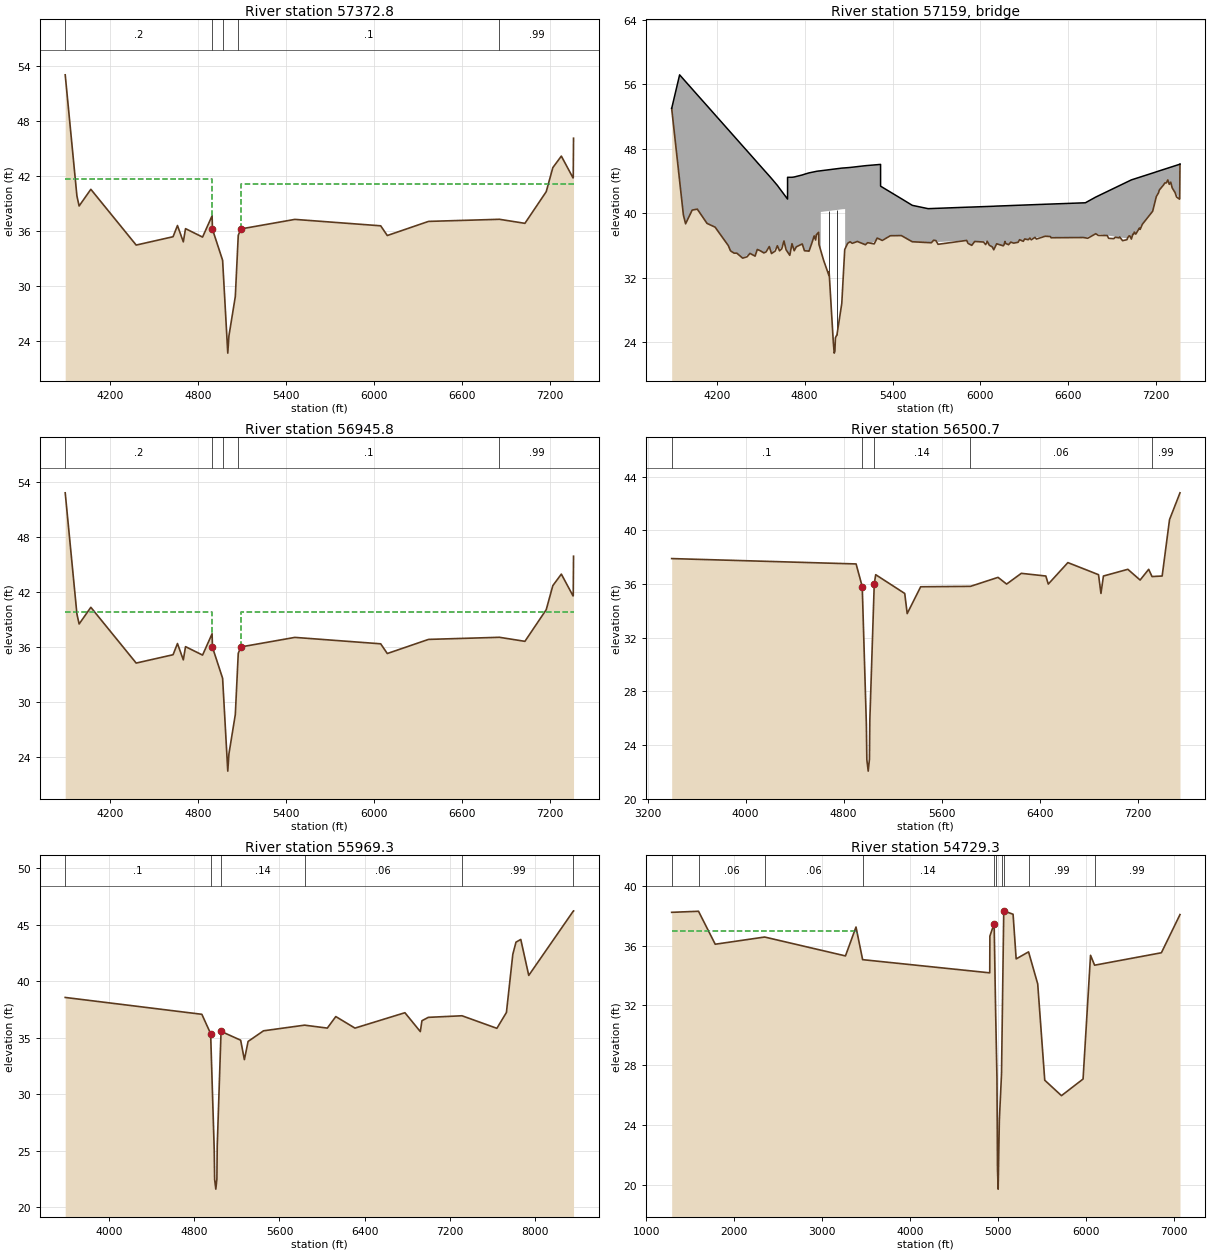
Type RM Length L Ch R = 1 ,57372.8 ,427,427,427
BEGIN DESCRIPTION:
Upstream Section of Bridge/Culvert/Weir. Previously 57739.5
END DESCRIPTION:
XS GIS Cut Line= 6
      3186346.14     13873288.47      3185641.49     13872916.75
      3185478.34     13872824.68      3185260.81     13872718.01
      3183861.98     13871955.37      3183279.37     13871666.38
#Sta/Elev= 30
  3892.1      53  3972.1   39.79  3987.1    38.7  4067.1   40.52  4376.6   34.44
  4628.4   35.35  4658.4   36.57  4698.4   34.79  4713.4   36.23  4829.8   35.31
  4894.8   37.64  4897.2   36.17  4966.6   32.78  5001.8   22.66  5009.9   24.56
  5053.3   28.83  5073.4   35.51  5091.5    36.2  5459.8   37.24  6045.7   36.54
  6090.7   35.48    6372   37.02  6856.3   37.25  7030.1   36.81  7175.6   40.26
  7220.6   42.88  7278.8   44.14  7358.8   41.76    7360    41.8    7362   46.09
#Mann= 5 ,-1 , 0
  3892.1      .2       0  4897.2      .1       0  4966.6     .04       0
  5073.4      .1       0  6856.3     .99       0
#XS Ineff= 2 , 0
       0    4895    41.6    5092       0   41.08
Permanent Ineff=
       F       F
Bank Sta=4897.2,5091.5
XS Rating Curve= 0
Exp/Cntr=.5,.3

Type RM Length L Ch R = 3 ,57159   ,,,
BEGIN DESCRIPTION:
US ROUTE 90 (Previously 57526.0)
Structure ID: N00-35
END DESCRIPTION:
Bridge Culvert--1,0,-1,-1, 0
Deck Dist Width WeirC Skew NumUp NumDn MinLoCord MaxHiCord MaxSubmerge Is_Ogee
10,407,2.6,0, 60, 60, , , .95, 0, 1,1,,
  3892.1  3946.3  3972.1  3987.1  4032.1  4067.1  4133.3  4188.3  4293.3  4376.6
  4426.6  4461.6  4476.6  4521.6  4558.4  4573.4  4613.4  4628.4  4658.4 4683.09
  4683.2  4698.4  4713.4  4728.4  4783.4  4798.4  4829.8  4864.8  4874.8  4879.8
  4894.8  4897.2 4909.91    4910  5053.2 5075.99  5076.1  5109.8  5214.8  5318.1
 5318.21  5459.8  5534.8  5642.8  5905.7  5940.7  6045.7  6090.7  6110.7  6155.7
    6372    6716    6787  7030.1  7175.6  7220.6  7278.8  7358.8    7360    7362
   53.01   57.18   56.65   56.34   55.42    54.7   53.35   52.22   50.07   48.36
   47.34   46.62   46.31   45.39   44.64   44.33   43.47    43.1   42.37   41.77
   44.47   44.47   44.47   44.51   44.76   44.85   45.02   45.15   45.19   45.21
   45.25   45.25   45.28   45.28   45.61   45.64   45.64   45.69   45.91   46.07
   43.37   41.82   40.99   40.58   40.76   40.78   40.85   40.88    40.9   40.93
   41.08   41.31   42.02   44.15      45   45.27   45.61   46.08   46.09    46.1
      53   44.05   39.79    38.7    40.4   40.52   38.75   38.29   35.37   34.44
   35.03   34.69   35.52   35.09   35.88   35.01   35.98   35.35   36.57   35.21
    35.2   34.79   36.23   35.36    36.2   35.36   35.31    37.2   36.69   37.34
   37.64   36.17   35.38   40.17    40.5   40.53   35.61   36.47    36.1   36.74
   36.74   37.24   36.47   36.37   36.64   36.03   36.54   35.48   36.22   35.97
   37.02   36.96   37.47   36.81   40.26   42.88   44.14   41.76    41.8   46.09
  3892.1  3946.3  3972.1  3987.1  4032.1  4067.1  4133.3  4188.3  4293.3  4376.6
  4426.6  4461.6  4476.6  4521.6  4558.4  4573.4  4613.4  4628.4  4658.4 4683.09
  4683.2  4698.4  4713.4  4728.4  4783.4  4798.4  4829.8  4864.8  4874.8  4879.8
  4894.8  4897.2 4909.91    4910  5053.2 5075.99  5076.1  5109.8  5214.8  5318.1
 5318.21  5459.8  5534.8  5642.8  5905.7  5940.7  6045.7  6090.7  6110.7  6155.7
    6372    6716    6787  7030.1  7175.6  7220.6  7278.8  7358.8    7360    7362
   53.01   57.18   56.65   56.34   55.42    54.7   53.35   52.22   50.07   48.36
   47.34   46.62   46.31   45.39   44.64   44.33   43.47    43.1   42.37   41.77
   44.47   44.47   44.47   44.51   44.76   44.85   45.02   45.15   45.19   45.21
   45.25   45.25   45.28   45.28   45.61   45.64   45.64   45.69   45.91   46.07
   43.37   41.82   40.99   40.58   40.76   40.78   40.85   40.88    40.9   40.93
   41.08   41.31   42.02   44.15      45   45.27   45.61   46.08   46.09    46.1
    52.8   43.85   39.59    38.5    40.2   40.32   38.55   38.09   35.17   34.24
   34.83   34.49   35.32   34.89   35.68   34.81   35.78   35.15   36.37   35.01
      35   34.59   36.03   35.16      36   35.16   35.11      37   36.49   37.14
   37.44   35.97   35.18   39.97    40.3   40.33   35.41   36.27    35.9   36.54
   36.54   37.04   36.27   36.17   36.44   35.83   36.34   35.28   36.02   35.77
   36.82   36.76   37.27   36.61   40.06   42.68   43.94   41.56    41.6   45.89
Pier Skew, UpSta & Num, DnSta & Num=  ,4965.5, 2 ,4965.5, 2 , 0 , 0 , 0 ,,
     1.4     1.4
   31.33   41.32
     1.4     1.4
   31.13   41.12
Pier Skew, UpSta & Num, DnSta & Num=  ,5020.5, 2 ,5020.5, 2 , 0 , 0 , 0 ,,
     1.4     1.4
   23.92   41.44
     1.4     1.4
   23.72   41.24
Abutment Skew #Up #Dn= , 2 , 2
  4909.8    4929
   40.17   34.19
  4909.8    4929
   39.97   33.99
Abutment Skew #Up #Dn= , 2 , 2
  5053.3 5076.19
   28.83   40.53
  5053.3 5076.19
   28.63   40.33
BR Coef= 1 , 1 , 0 ,1.25, 0 ,,,.8,0,2,0,
WSPro=,,,, 1 ,,,, 0 ,,,, 0 ,,,,-1 ,-1 ,-1 , 0 , 0 , 0 , 0 , 0
BR U #Sta/Elev= 170
  3892.1      53  3946.3   44.05  3958.3   42.07  3972.1   39.79  3987.1    38.7
  4032.1    40.4  4067.1   40.52  4133.3   38.75  4188.3   38.29  4278.3   36.01
  4293.3   35.37  4298.3   35.29  4318.3   35.06  4336.6   35.06  4376.6   34.44
  4406.6   34.61  4426.6   35.03  4461.6   34.69  4476.6   35.52  4496.6   35.36
  4521.6   35.09  4536.6   35.22  4558.4   35.88  4573.4   35.01  4598.4   35.32
  4601.3   35.45  4613.4   35.98  4628.4   35.35  4643.4    35.6  4658.4   36.57
  4673.4   35.47 4683.09   35.21  4683.2    35.2 4683.31    35.2  4698.4   34.79
  4713.4   36.23    4718   35.96  4728.4   35.36  4743.4   35.85  4771.8    36.1
  4783.4    36.2  4798.4   35.36  4829.8   35.31  4830.1   35.33  4849.8   36.35
  4864.8    37.2  4874.8   36.69  4879.8   37.34  4883.4   37.41  4894.8   37.64
  4897.2   36.17 4909.91   35.38    4910   35.37  4927.9   34.26  4928.9    34.2
    4929   34.19  4965.4    32.3  4966.6   32.78  4986.4   26.68    4990   25.57
    4996   23.86  5001.8   22.66  5006.3   22.89  5009.9   24.56  5020.5   24.95
  5046.8   28.06  5053.2   28.82  5053.3   28.83  5073.4   35.51 5075.99   35.61
  5076.1   35.61  5091.5    36.2  5094.8    36.3  5108.9   36.46  5109.8   36.47
  5124.8   36.28  5159.8   36.51  5195.7   36.24  5214.8    36.1  5229.8   36.36
  5253.9   36.28  5274.8   36.21  5294.8   36.93 5317.99   36.74  5318.1   36.74
 5318.21   36.74  5329.8   36.64  5384.8   37.22  5459.8   37.24  5534.8   36.47
  5537.8   36.47  5577.8   36.43  5642.8   36.37  5664.8   36.35  5680.7   36.67
  5695.7   36.62  5710.7   36.16  5905.7   36.64  5915.7   36.27  5940.7   36.03
  5960.7   36.51  6020.7   36.44  6035.7   36.12  6045.7   36.54  6060.7   36.04
  6080.7   35.83  6090.7   35.48  6110.7   36.22  6155.7   35.97  6160.7   36.09
    6167   36.51    6172   36.26    6192   36.11    6207   36.43    6227    36.3
    6257   36.41    6267   36.73    6292   36.53    6302   36.82    6327   36.73
    6337   36.93    6347   36.72    6372   37.02    6382   36.81    6442   37.16
    6477   37.12    6482   36.97    6702      37    6716   36.96    6732   36.91
    6787   37.47  6805.1   37.26  6856.3   37.25  6865.1   37.25  6875.1    36.9
  6910.1   36.86  6920.1   37.04  6945.1   36.96  6950.1   37.07  6952.7   37.01
  6970.1   36.61  7000.1   36.73  7005.1   36.98  7007.3   37.03  7015.1   37.21
  7020.1   37.18  7030.1   36.81  7040.1   37.41  7045.1    37.4  7050.1   37.67
  7060.1   37.42  7085.1   38.18  7090.1   38.01  7105.1   38.64  7175.6   40.26
  7200.6   42.09  7215.6   42.55  7220.6   42.88  7248.8    43.5  7258.8   43.77
  7268.8   43.78  7278.8   44.14  7288.8    43.6  7298.8   43.86  7308.8   43.15
  7328.8   42.56  7338.8   42.02  7358.8   41.76    7360    41.8    7362   46.09
BR U #Mann= 5
  3892.1      .2  4897.2      .1  4966.6     .04  5073.4      .1  6856.3     .99
BR U Banks=4897.2,5091.5
BR D #Sta/Elev= 170
  3892.1    52.8  3946.3   43.85  3958.3   41.87  3972.1   39.59  3987.1    38.5
  4032.1    40.2  4067.1   40.32  4133.3   38.55  4188.3   38.09  4278.3   35.81
  4293.3   35.17  4298.3   35.09  4318.3   34.86  4336.6   34.86  4376.6   34.24
  4406.6   34.41  4426.6   34.83  4461.6   34.49  4476.6   35.32  4496.6   35.16
  4521.6   34.89  4536.6   35.02  4558.4   35.68  4573.4   34.81  4598.4   35.12
  4601.3   35.25  4613.4   35.78  4628.4   35.15  4643.4    35.4  4658.4   36.37
  4673.4   35.27 4683.09   35.01  4683.2      35 4683.31      35  4698.4   34.59
  4713.4   36.03    4718   35.76  4728.4   35.16  4743.4   35.65  4771.8    35.9
  4783.4      36  4798.4   35.16  4829.8   35.11  4830.1   35.13  4849.8   36.15
  4864.8      37  4874.8   36.49  4879.8   37.14  4883.4   37.21  4894.8   37.44
  4897.2   35.97 4909.91   35.18    4910   35.17  4927.9   34.06  4928.9      34
    4929   33.99  4965.4    32.1  4966.6   32.58  4986.4   26.48    4990   25.37
    4996   23.66  5001.8   22.46  5006.3   22.69  5009.9   24.36  5020.5   24.75
  5046.8   27.86  5053.2   28.62  5053.3   28.63  5073.4   35.31 5075.99   35.41
  5076.1   35.41  5091.5      36  5094.8    36.1  5108.9   36.26  5109.8   36.27
  5124.8   36.08  5159.8   36.31  5195.7   36.04  5214.8    35.9  5229.8   36.16
  5253.9   36.08  5274.8   36.01  5294.8   36.73 5317.99   36.54  5318.1   36.54
 5318.21   36.54  5329.8   36.44  5384.8   37.02  5459.8   37.04  5534.8   36.27
  5537.8   36.27  5577.8   36.23  5642.8   36.17  5664.8   36.15  5680.7   36.47
  5695.7   36.42  5710.7   35.96  5905.7   36.44  5915.7   36.07  5940.7   35.83
  5960.7   36.31  6020.7   36.24  6035.7   35.92  6045.7   36.34  6060.7   35.84
  6080.7   35.63  6090.7   35.28  6110.7   36.02  6155.7   35.77  6160.7   35.89
    6167   36.31    6172   36.06    6192   35.91    6207   36.23    6227    36.1
    6257   36.21    6267   36.53    6292   36.33    6302   36.62    6327   36.53
    6337   36.73    6347   36.52    6372   36.82    6382   36.61    6442   36.96
    6477   36.92    6482   36.77    6702    36.8    6716   36.76    6732   36.71
    6787   37.27  6805.1   37.06  6856.3   37.05  6865.1   37.05  6875.1    36.7
  6910.1   36.66  6920.1   36.84  6945.1   36.76  6950.1   36.87  6952.7   36.81
  6970.1   36.41  7000.1   36.53  7005.1   36.78  7007.3   36.83  7015.1   37.01
  7020.1   36.98  7030.1   36.61  7040.1   37.21  7045.1    37.2  7050.1   37.47
  7060.1   37.22  7085.1   37.98  7090.1   37.81  7105.1   38.44  7175.6   40.06
  7200.6   41.89  7215.6   42.35  7220.6   42.68  7248.8    43.3  7258.8   43.57
  7268.8   43.58  7278.8   43.94  7288.8    43.4  7298.8   43.66  7308.8   42.95
  7328.8   42.36  7338.8   41.82  7358.8   41.56    7360    41.6    7362   45.89
BR D #Mann= 5
  3892.1      .2  4897.2      .1  4966.6     .04  5073.4      .1  6856.3     .99
BR D Banks=4897.2,5091.5
BC Design=,, 0 ,, 0 ,,,,,,
BC HTab HWMax=53

Type RM Length L Ch R = 1 ,56945.8 ,445.1,445.1,445.1
BEGIN DESCRIPTION:
Downstream Section of Bridge/Culvert/Weir. Previously 57312.5
END DESCRIPTION:
XS GIS Cut Line= 6
      3186476.26     13872881.78      3185771.61     13872510.05
      3185608.46     13872417.98      3185390.93     13872311.31
       3183992.1     13871548.67      3183409.49     13871259.69
#Sta/Elev= 30
  3892.1   52.79  3972.1   39.58  3987.1   38.49  4067.1   40.31  4376.6   34.23
  4628.4   35.14  4658.4   36.36  4698.4   34.58  4713.4   36.02  4829.8    35.1
  4894.8   37.43  4897.2   35.96  4966.6   32.57  5001.8   22.45  5009.9   24.35
  5053.3   28.62  5073.4    35.3  5091.5   35.99  5459.8   37.03  6045.7   36.33
  6090.7   35.27    6372   36.81  6856.3   37.04  7030.1    36.6  7175.6   40.05
  7220.6   42.67  7278.8   43.93  7358.8   41.55    7360   41.59    7362   45.88
#Mann= 5 ,-1 , 0
  3892.1      .2       0  4897.2      .1       0  4966.6     .04       0
  5073.4      .1       0  6856.3     .99       0
#XS Ineff= 2 , 0
       0    4895    39.8    5092       0   39.76
Permanent Ineff=
       F       F
Bank Sta=4897.2,5091.5
XS Rating Curve= 0
Exp/Cntr=.5,.3

Type RM Length L Ch R = 1 ,56500.7 ,521.6,531.4,534.4
BEGIN DESCRIPTION:
Previously Cross Section 56867.4 - Interpolated
END DESCRIPTION:
XS GIS Cut Line= 6
      3187102.65      13872619.2      3185852.07      13872047.7
      3185421.76     13871866.16      3184675.44     13871523.26
      3183660.19      13871220.7       3183236.6     13871180.36
#Sta/Elev= 30
  3397.2    37.9  4902.2    37.5  4952.3   35.81    4986   25.55  4989.9   22.92
    5001   22.06  5011.1   22.95  5014.3   25.86  5050.3   36.01  5062.2    36.7
  5299.2    35.3  5319.2    33.8  5429.2    35.8  5835.6   35.83  6060.5    36.5
  6130.5      36  6250.5    36.8  6450.5    36.6  6470.5      36  6630.5    37.6
  6880.5    36.7  6900.5    35.3  6920.5    36.6  7119.9    37.1  7219.9    36.3
  7289.9    37.1  7317.1   36.56  7399.9    36.6  7459.9    40.8  7545.4    42.8
#Mann= 5 ,-1 , 0
  3397.2      .1       0  4952.3     .04       0  5050.3     .14       0
  5835.6     .06       0  7317.1     .99       0
Bank Sta=4952.3,5050.3
XS Rating Curve= 0
Exp/Cntr=.3,.1

Type RM Length L Ch R = 1 ,55969.3 ,1266.4,1240,1192.9
BEGIN DESCRIPTION:
Previously Cross Section 56336
Located At: 1ST XS DS NEW 90
END DESCRIPTION:
XS GIS Cut Line= 5
      3187070.34     13872086.87      3187069.94     13872086.39
      3185155.67     13871129.25      3184102.82     13871060.88
      3182516.71     13871033.54
#Sta/Elev= 30
  3584.1   38.55  4869.7   37.06  4952.3   35.35    4986   25.09  4989.9   22.46
    5001    21.6  5011.1   22.49  5014.3    25.4  5050.3   35.55  5234.7   34.77
  5269.7   33.05  5304.7   34.66  5449.7    35.6  5835.6    36.1  6049.9   35.84
  6129.9   36.86  6309.9   35.84    6780    37.2    6925   35.53    6940   36.49
    7000   36.79  7317.1   36.93    7645   35.82    7735   37.22    7795   42.36
    7825   43.44    7870   43.68    7945    40.5  8365.9   46.21  8366.3   46.21
#Mann= 6 ,-1 , 0
  3584.1      .1       0  4952.3     .04       0  5050.3     .14       0
  5835.6     .06       0  7317.1     .99       0  8365.9      .2       0
Bank Sta=4952.3,5050.3
XS Rating Curve= 0
Exp/Cntr=.3,.1

Type RM Length L Ch R = 1 ,54729.3 ,923.9,947,942.7
BEGIN DESCRIPTION:
Previously Cross Section 55096
Located At: 2ND XS DS NEW 90
END DESCRIPTION:
XS GIS Cut Line= 5
      3189681.55     13871430.06      3187835.65     13870527.62
      3185360.77     13870172.12      3184212.21     13870035.38
      3184150.48     13870055.58
#Sta/Elev= 30
  1288.5   38.22  1593.7   38.29  1783.5   36.09  2345.2   36.57  3263.5   35.31
  3383.2   37.24  3458.5   35.06  4903.2   34.18  4904.6   36.63  4952.4   37.46
    4953   37.47  4969.6    31.7  4985.1   27.16  4991.1   21.09  4998.6   19.74
  5012.1   24.32  5036.8   27.43  5061.9   38.15  5062.3   38.32  5168.2   38.09
  5203.2   35.11  5344.2   35.58  5448.2   33.44  5528.2   27.01  5718.2   25.98
  5963.5   27.09  6048.5   35.35  6094.8   34.69  6853.5   35.52  7065.1   38.07
#Mann= 10 ,-1 , 0
  1288.5     .99       0  1593.7     .06       0  2345.2     .06       0
  3458.5     .14       0  4952.4     .08       0  4969.6     .04       0
  5036.8     .08       0  5061.9     .14       0  5344.2     .99       0
  6094.8     .99       0
#XS Ineff= 2 , 0
       0    3400      37               0
Permanent Ineff=
       F       F
Bank Sta=4953,5062.3
XS Rating Curve= 0
Exp/Cntr=.3,.1

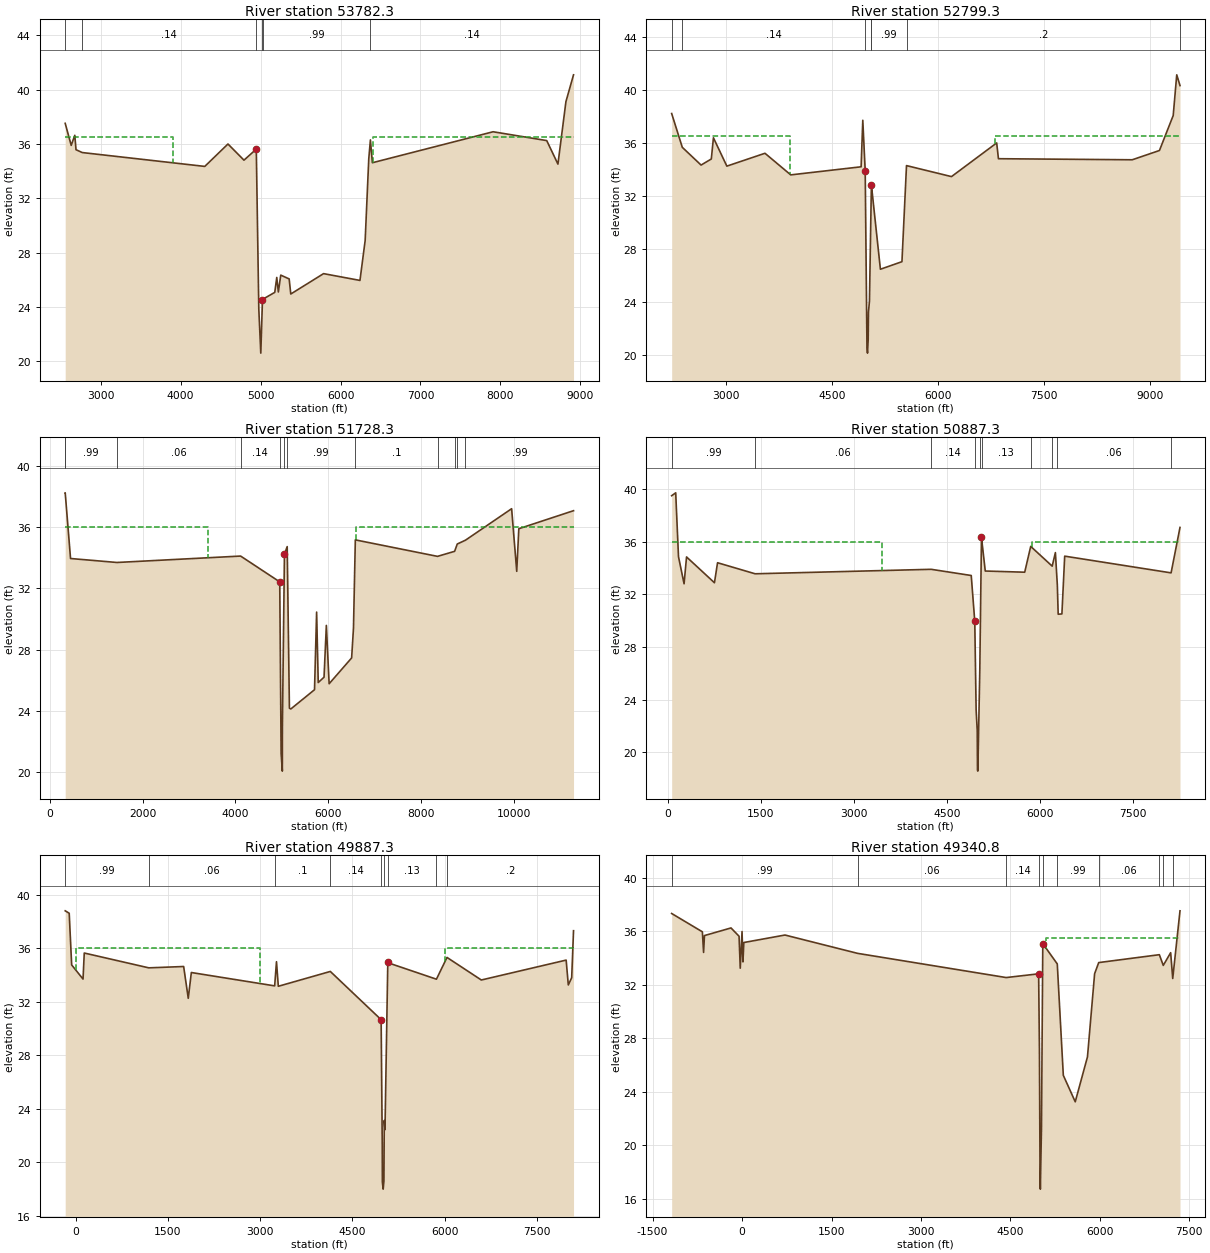
Type RM Length L Ch R = 1 ,53782.3 ,984.1,983,967.7
BEGIN DESCRIPTION:
Previously Cross Section 54149
Located At: 2ND XS DS NEW 90
END DESCRIPTION:
XS GIS Cut Line= 4
      3188621.03     13869636.54      3186851.16     13869502.12
      3185839.34     13869283.35      3182352.41     13868644.72
#Sta/Elev= 30
  2558.2   37.52  2633.2    35.9  2678.2   36.64  2693.2   35.58  2770.9   35.37
  4303.2   34.35  4593.1      36  4793.1   34.81  4947.1   35.62  4978.6   23.85
  5003.5   20.61  5024.4   24.52  5035.3    24.6  5178.1   25.08  5203.1   26.18
  5223.1   25.11  5253.1   26.35  5358.1   26.07  5378.3   24.96  5788.3   26.46
  6243.3   25.96  6308.3    28.9  6353.3    34.9  6373.8    36.3  6398.3   34.62
  7908.3    36.9  8578.3   36.25  8718.3   34.52  8818.3   39.12  8913.3   41.09
#Mann= 6 ,-1 , 0
  2558.2     .06       0  2770.9     .14       0  4947.1     .04       0
  5024.4     .06       0  5035.3     .99       0  6373.8     .14       0
#XS Ineff= 2 , 0
       0    3900    36.5    6400       0    36.5
Permanent Ineff=
       F       F
Bank Sta=4947.1,5024.4
XS Rating Curve= 0
Exp/Cntr=.3,.1

Type RM Length L Ch R = 1 ,52799.3 ,1060.4,1071,1057.2
BEGIN DESCRIPTION:
Previously Cross Section 53166
Located At: 4TH XS DS NEW 90
END DESCRIPTION:
XS GIS Cut Line= 6
      3189177.49     13869315.14      3188967.11     13869231.27
      3187411.77     13868695.39      3185825.66     13868271.52
      3184554.04     13867916.01      3182188.55     13867970.71
#Sta/Elev= 30
  2225.8   38.21  2376.2   35.66  2642.3   34.32  2787.3   34.78  2817.3   36.38
  3007.3   34.24  3547.3   35.21  3912.3   33.58  4908.9   34.19  4932.8    37.7
    4967   33.87  4991.9   20.57  4999.4   20.13  5009.3   21.16    5013   23.22
  5027.3   24.06  5054.5   32.82  5055.2   32.79  5182.2   26.46  5487.4   27.03
  5551.9   34.28  6189.1   33.45  6829.1   35.99  6854.1    34.8  8749.5   34.72
  9134.5   35.42  9329.5   38.06  9379.5   41.13  9425.2   40.33  9425.6   40.32
#Mann= 7 ,-1 , 0
  2225.8      .2       0  2376.2     .14       0    4967     .04       0
  5054.5     .06       0  5055.2     .99       0  5551.9      .2       0
  9425.2      .2       0
#XS Ineff= 2 , 0
       0    3900    36.5    6800       0    36.5
Permanent Ineff=
       F       F
Bank Sta=4967,5054.5
XS Rating Curve= 0
Exp/Cntr=.3,.1

Type RM Length L Ch R = 1 ,51728.3 ,858.9,841,787
BEGIN DESCRIPTION:
Previously Cross Section 52095
Located At: 5TH XS DS NEW 90
END DESCRIPTION:
XS GIS Cut Line= 4
      3191438.57     13867526.32      3187363.91     13867581.02
      3186297.39     13867307.55      3180547.75     13866671.74
#Sta/Elev= 30
     331   38.26   331.1   38.26     446   33.96  1446.8    33.7  4113.4   34.12
  4956.8   32.43  4986.7    21.2  5012.9   20.04  5014.3   23.02  5058.4   34.24
  5117.6   34.74  5165.5   24.16  5196.2   24.11    5707   25.37    5752   30.45
    5787   25.84    5912   26.19    5962   29.58    6022   25.76    6507   27.45
    6547   29.41  6586.8   35.18  8358.5    34.1  8727.7   34.43  8785.1   34.91
  8962.1   35.16    9957   37.22   10067   33.12   10112   35.91 11291.7   37.09
#Mann= 12 ,-1 , 0
     331      .2       0   331.1     .99       0  1446.8     .06       0
  4113.4     .14       0  4956.8     .04       0  5058.4     .14       0
  5117.6     .99       0  6586.8      .1       0  8358.5     .06       0
  8727.7      .1       0  8785.1     .06       0  8962.1     .99       0
#XS Ineff= 2 , 0
       0    3400      36    6600       0      36
Permanent Ineff=
       F       F
Bank Sta=4956.8,5058.4
XS Rating Curve= 0
Exp/Cntr=.3,.1

Type RM Length L Ch R = 1 ,50887.3 ,1074.5,1000,897.1
BEGIN DESCRIPTION:
Previously Cross Section 51254
Located At: 6TH XS DS NEW 90
END DESCRIPTION:
XS GIS Cut Line= 5
      3191807.75      13867075.1      3190645.52       13866870.
      3187500.65     13866582.86      3186734.94     13866623.88
      3183644.13     13866461.77
#Sta/Elev= 30
    59.9   39.48   124.9    39.7   169.9   34.85   259.9   32.79   299.9   34.83
   749.9   32.87   799.9   34.39  1406.2   33.55    4246   33.89  4892.3   33.42
  4948.8   29.97  4949.3   29.94  4971.3    23.2  4989.1   21.63    4993   18.63
  4998.8   18.56  5030.4   26.22  5057.3   36.32  5060.2    36.2  5118.6   33.76
  5754.9   33.67  5851.8   35.63  6198.2   34.13  6249.9   35.16  6281.2   32.69
  6294.9   30.48  6354.9    30.5  6399.9   34.89  8116.2   33.62  8259.9   37.07
#Mann= 10 ,-1 , 0
    59.9     .99       0  1406.2     .06       0    4246     .14       0
  4949.3     .04       0  5030.4     .08       0  5060.2     .13       0
  5851.8     .06       0  6198.2      .1       0  6281.2     .06       0
  8116.2      .1       0
#XS Ineff= 2 , 0
       0    3450      36    5865       0      36
Permanent Ineff=
       F       F
Bank Sta=4948.8,5057.3
XS Rating Curve= 0
Exp/Cntr=.3,.1

Type RM Length L Ch R = 1 ,49887.3 ,561.7,546.5,545.4
BEGIN DESCRIPTION:
Previously Cross Section 50254
Located At: 5TH XS US WALLISVILLE
END DESCRIPTION:
XS GIS Cut Line= 6
      3191567.17     13866629.35      3190217.06     13865758.06
      3187030.47      13865426.3      3186572.34     13865839.85
      3185892.05     13866079.21      3183779.81     13866260.31
#Sta/Elev= 30
  -172.2   38.82  -107.2   38.64   -67.2   34.77   117.8   33.71   137.8   35.66
  1187.6   34.55  1754.6   34.65  1829.6   32.27  1879.6    34.2  3235.1    33.2
  3264.6   35.01  3294.6   33.17  4140.4   34.28  4966.9   30.67  4967.1   30.66
  4985.3   21.24  4987.1   18.51  5000.2   17.98  5012.7    18.6  5017.9   23.12
  5029.7   22.43  5075.6   34.99  5079.1   34.93  5866.6    33.7  6038.4   35.33
  6596.8   33.64  7976.8   35.13  8011.8   33.27  8066.8   33.81  8096.8   37.33
#Mann= 9 ,-1 , 0
  -172.2     .99       0  1187.6     .06       0  3235.1      .1       0
  4140.4     .14       0  4967.1     .04       0  5017.9     .08       0
  5079.1     .13       0  5866.6     .06       0  6038.4      .2       0
#XS Ineff= 2 , 0
       0    3000      36    6000       0      36
Permanent Ineff=
       F       F
Bank Sta=4966.9,5075.6
XS Rating Curve= 0
Exp/Cntr=.5,.3

Type RM Length L Ch R = 1 ,49340.8 ,11.5,11.5,11.5
BEGIN DESCRIPTION:
Upstream Section of Bridge/Culvert/Weir. Previously 49707.5
END DESCRIPTION:
XS GIS Cut Line= 6
      3192546.46     13865485.58       3189488.4     13865366.16
      3187118.96     13865118.55      3186905.64     13865217.59
      3186476.24     13865252.37      3184091.49     13865609.93
#Sta/Elev= 30
   -1181   37.34    -666   35.97    -646   34.43    -631   35.69    -186   36.26
     -51   35.64     -31   33.25      -1   35.99      14   33.72      29   35.17
     719   35.73  1936.4   34.36  4428.5   32.55 4972.55   32.83    4986   27.04
 4996.44   17.57 5001.22   16.73 5020.18   21.32 5042.21   35.09    5285   33.57
  5386.4   25.24  5586.4   23.26  5791.4   26.62  5911.4   32.84    5980   33.67
  6996.6   34.26  7062.6   33.46  7186.4   34.41  7221.1   32.48    7343   37.54
#Mann= 10 ,-1 , 0
   -1181     .99       0  1936.4     .06       0  4428.5     .14       0
 4972.55     .04       0 5042.21     .14       0    5285     .99       0
    5980     .06       0  6996.6      .1       0  7062.6     .06       0
  7221.1      .1       0
#XS Ineff= 2 , 0
       0    4969    31.9 5101.21       0   35.49
Permanent Ineff=
       F       F
Bank Sta=4972.55,5042.21
XS Rating Curve= 0
Exp/Cntr=.5,.3