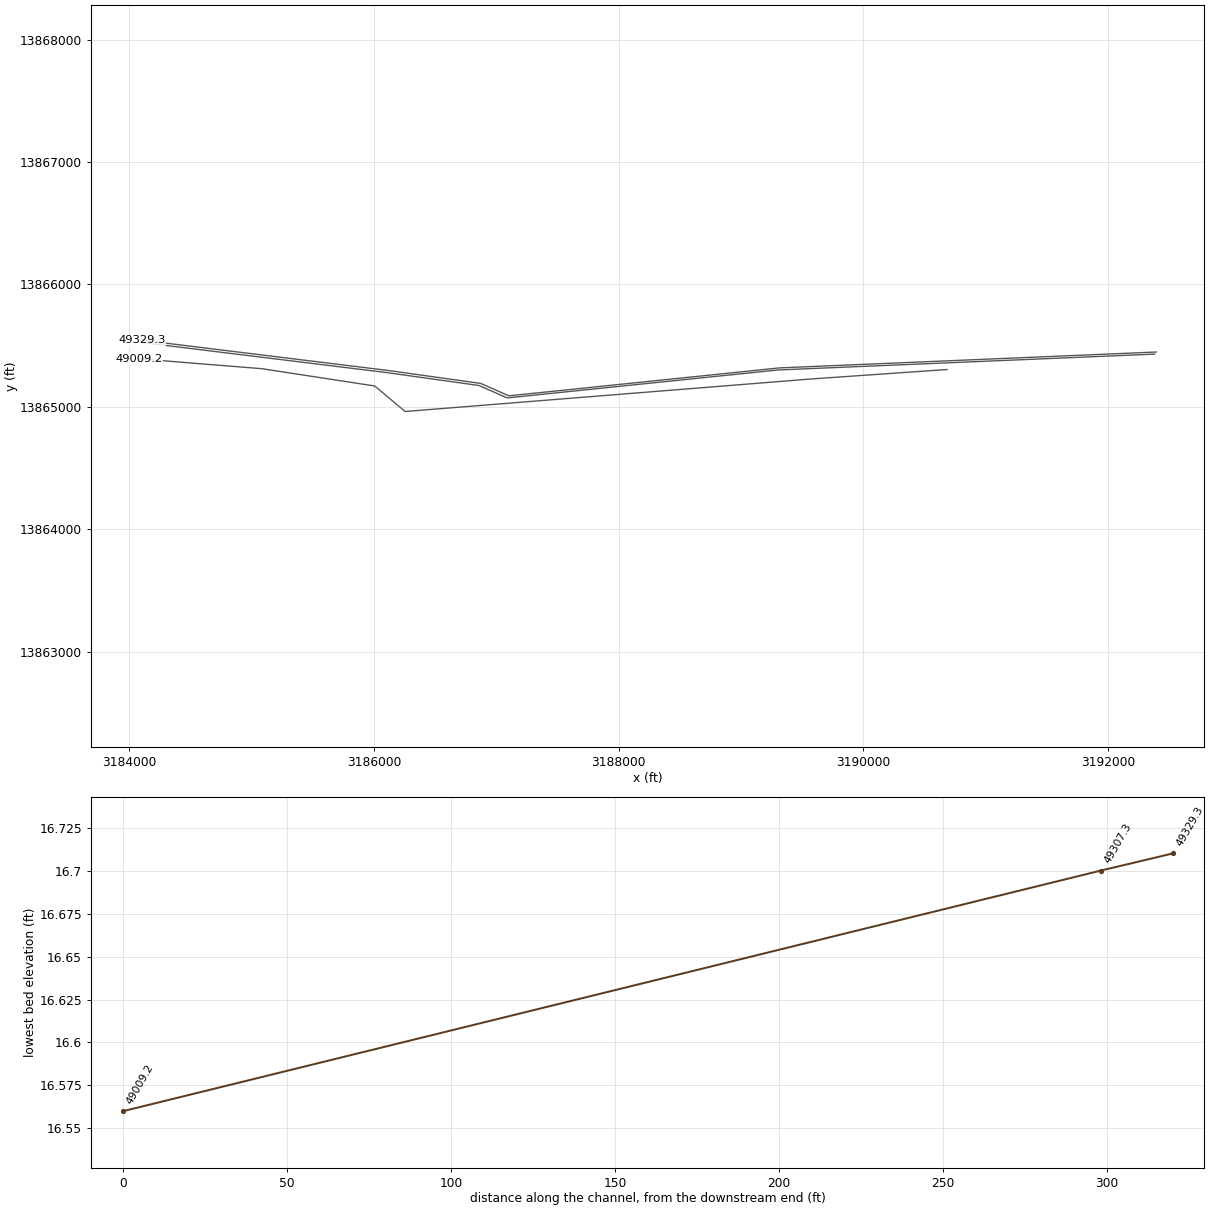
HEC-RAS study N100-00-00.prj: N100-00-00

--- N100-00-00.g01 (geometry) --- (continued)

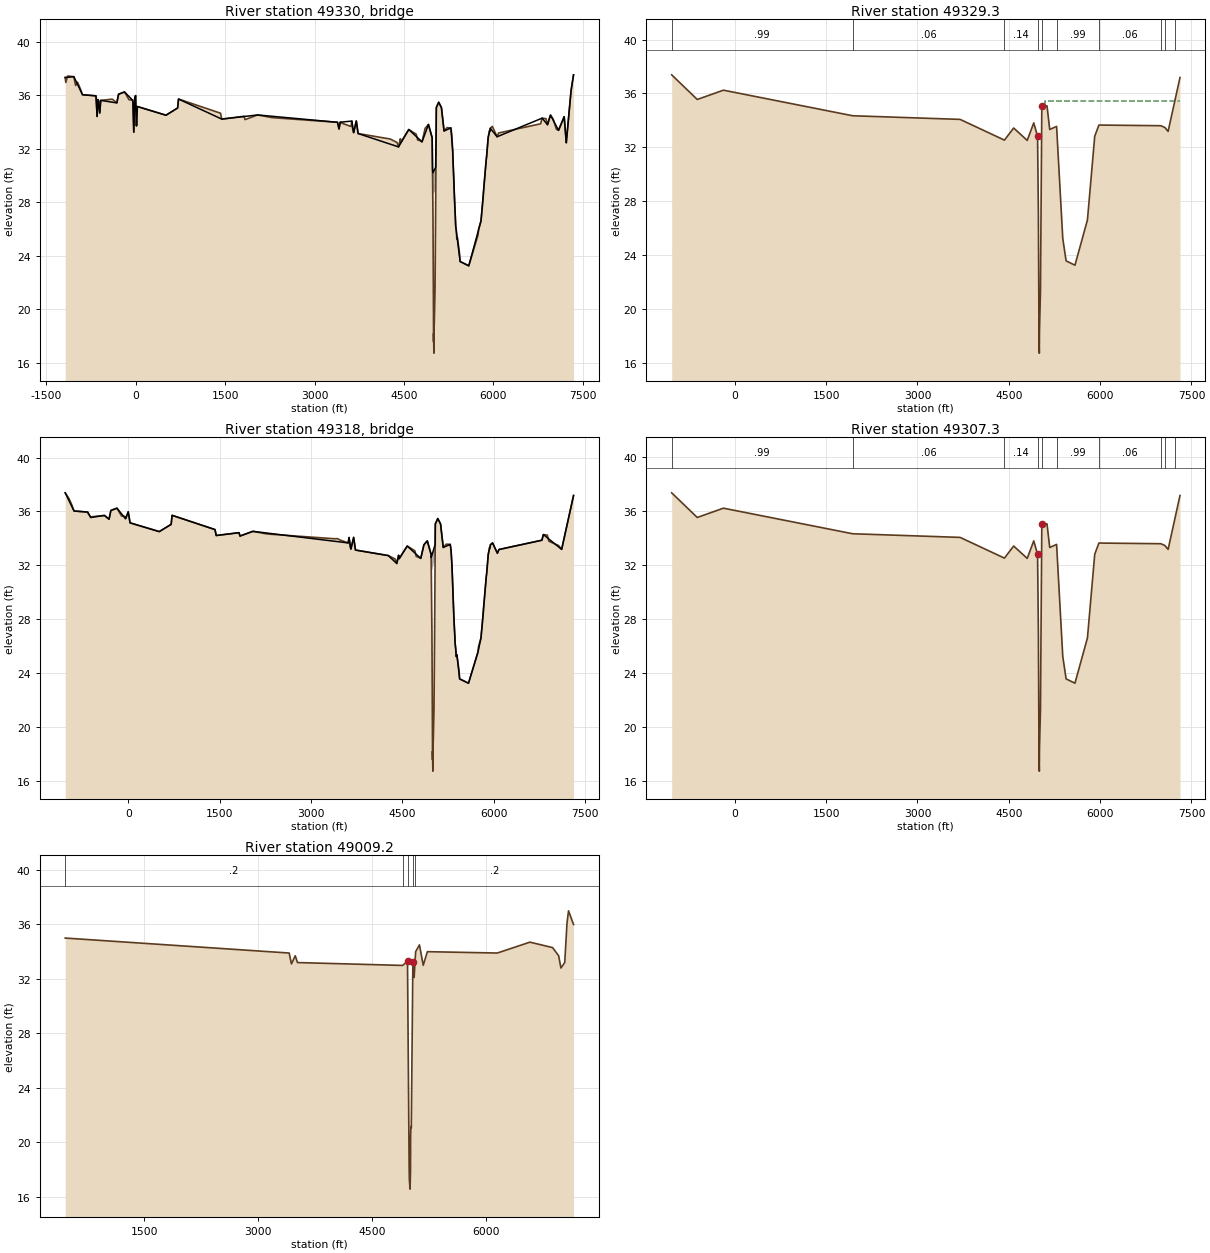
Type RM Length L Ch R = 3 ,49330   ,,,
BEGIN DESCRIPTION:
12" DIAMETER PIPELINE - 35 Degree Skew (Previously 49697.0)
END DESCRIPTION:
Bridge Culvert--1,0,-1,-1, 0
Deck Dist Width WeirC Skew NumUp NumDn MinLoCord MaxHiCord MaxSubmerge Is_Ogee
10,1,2.6,0, 60, 60, , , .95, 0, 1,1,,
   -1181   -1036    -891    -666    -646    -631    -601    -586    -316    -286
    -186     -51     -46     -31     -16      -1      14      29     509     704
     719    1444  2045.5  3385.5  3410.5  3430.5  3625.5  3655.5  3700.5  3730.5
  4408.9    4580 4802.53  4910.1 4972.55 4978.01    4986 5030.46  5040.5 5042.21
 5081.98 5127.66 5172.13  5286.4  5316.4  5366.4  5441.4  5586.4  5791.4  5911.4
  5946.4  6061.4  6816.4  6906.4  6956.4  7091.4  7186.4  7221.4  7301.4    7343
   37.32   37.38   36.03   35.95   34.41   35.67   34.67   35.61   35.42   36.07
   36.24   35.62   35.46   33.23   35.72   35.97    33.7   35.15    34.5   35.04
   35.71   34.21   34.52   33.97   33.47   33.98   34.06    33.2   34.07   33.13
   32.13   33.43   32.51   33.81   32.82   30.47    30.2    30.6   33.93   35.08
   35.47   35.07   33.32   33.55   31.85   26.24   23.56   23.24    26.6   32.82
   33.52   32.89   34.28   33.79   34.51   33.37   34.39   32.44   36.33   37.52
   37.32   37.38   36.03   35.95   34.41   35.67   34.67   35.61   35.42   36.07
   36.24   35.62   35.46   33.23   35.72   35.97    33.7   35.15    34.5   35.04
   35.71   34.21   34.52   33.97   33.47   33.98   34.06    33.2   34.07   33.13
   32.13   33.43   32.51   33.81   32.81   30.46   28.53   28.93   33.92   35.07
   35.47   35.07   33.32   33.55   31.85   26.24   23.56   23.24    26.6   32.82
   33.52   32.89   34.28   33.79   34.51   33.37   34.39   32.44   36.33   37.52
   -1181   -1036    -891    -666    -646    -631    -601    -586    -316    -286
    -186     -51     -46     -31     -16      -1      14      29     509     704
     719    1444  2045.5  3385.5  3410.5  3430.5  3625.5  3655.5  3700.5  3730.5
  4408.9    4580 4802.53  4910.1 4972.55 4978.01    4986 5030.46  5040.5 5042.21
 5081.98 5127.66 5172.13  5286.4  5316.4  5366.4  5441.4  5586.4  5791.4  5911.4
  5946.4  6061.4  6816.4  6906.4  6956.4  7091.4  7186.4  7221.4  7301.4    7343
   37.32   37.38   36.03   35.95   34.41   35.67   34.67   35.61   35.42   36.07
   36.24   35.62   35.46   33.23   35.72   35.97    33.7   35.15    34.5   35.04
   35.71   34.21   34.52   33.97   33.47   33.98   34.06    33.2   34.07   33.13
   32.13   33.43   32.51   33.81   32.82   30.47    30.2    30.6   33.93   35.08
   35.47   35.07   33.32   33.55   31.85   26.24   23.56   23.24    26.6   32.82
   33.52   32.89   34.28   33.79   34.51   33.37   34.39   32.44   36.33   37.52
   37.32   37.38   36.03   35.95   34.41   35.67   34.67   35.61   35.42   36.07
   36.24   35.62   35.46   33.23   35.72   35.97    33.7   35.15    34.5   35.04
   35.71   34.21   34.52   33.97   33.47   33.98   34.06    33.2   34.07   33.13
   32.13   33.43   32.51   33.81   32.81   30.46   28.53   28.93   33.92   35.07
   35.47   35.07   33.32   33.55   31.85   26.24   23.56   23.24    26.6   32.82
   33.52   32.89   34.28   33.79   34.51   33.37   34.39   32.44   36.33   37.52
BR Coef= 1 , 1 , 0 ,1.25, 0 ,,,.8,0,2,0,
WSPro=,,,, 1 ,,,, 0 ,,,, 0 ,,,,-1 ,-1 ,-1 , 0 , 0 , 0 , 0 , 0
BR U #Sta/Elev= 126
   -1181   37.32   -1171   36.95   -1141   37.43   -1036   37.38   -1006   36.72
    -976   36.97    -931   36.52    -891   36.03    -666   35.95    -661   35.85
    -646   34.41    -631   35.67    -616   35.55    -601   34.67    -586   35.61
    -391    35.7    -316   35.42    -286   36.07    -186   36.24    -111   35.66
     -51   35.62     -46   35.46     -31   33.23     -16   35.72      -1   35.97
      14    33.7      29   35.15     509    34.5     704   35.04     719   35.71
    1424   34.65    1444   34.21    1819   34.42    1834   34.17  1936.4   34.34
  2045.5   34.52  2285.5   34.32  3385.5   33.97  3410.5   33.47  3430.5   33.98
  3480.5   33.87  3610.5   33.66  3625.5   34.06  3640.5   33.41  3655.5    33.2
  3700.5   34.07  3730.5   33.13  4268.9   32.72  4383.9   32.46  4408.9   32.13
  4428.5   32.53  4438.9   32.74  4448.9   32.49    4580   33.43    4705   33.08
    4730   32.64 4741.05   32.65 4802.53   32.51 4854.45   33.52  4910.1   33.81
 4953.01   33.12 4972.55   32.81 4977.92    30.5 4978.01   30.46    4986   27.02
 4991.91    22.1 4996.44   17.55 4996.53   18.03 4996.69   18.19 5001.22   16.71
 5003.17   17.65 5003.49   18.29 5009.49   19.25 5020.18    21.3 5030.46   27.18
  5040.5   33.92 5040.61      34 5042.21   35.07 5045.61    35.1 5081.98   35.47
 5127.66   35.07 5172.13   33.32 5222.35   33.57    5285   33.55  5286.4   33.55
  5301.4   33.05  5316.4   31.85  5346.4   28.14  5361.4   26.88  5366.4   26.24
  5376.4   25.89  5386.4   25.22  5396.4   25.35  5431.4   24.16  5441.4   23.56
  5586.4   23.24  5741.4   25.54  5751.4   25.96  5791.4    26.6  5826.4   28.25
  5836.4   28.94  5876.4   31.11  5886.4   31.38  5911.4   32.82  5931.4   33.33
  5941.4   33.26  5946.4   33.52    5980   33.65  5981.4   33.66  6061.4   32.89
  6086.4   33.17  6791.4   33.86  6816.4   34.28  6881.4   34.24  6906.4   33.79
  6956.4   34.51  6996.6   34.24  7001.4   34.21  7056.4   33.45  7062.6   33.44
  7091.4   33.37  7186.4   34.39  7221.1   32.46  7221.4   32.44  7301.4   36.33
    7343   37.52
BR U #Mann= 11
   -1181      .2   -1181     .99  1936.4     .06  4428.5     .14 4972.55     .04
 5042.21     .14    5285     .99    5980     .06  6996.6      .1  7062.6     .06
  7221.1      .1
BR U Banks=4972.55,5042.21
BR D #Sta/Elev= 126
   -1181   37.32   -1171   36.95   -1141   37.43   -1036   37.38   -1006   36.72
    -976   36.97    -931   36.52    -891   36.03    -666   35.95    -661   35.85
    -646   34.41    -631   35.67    -616   35.55    -601   34.67    -586   35.61
    -391    35.7    -316   35.42    -286   36.07    -186   36.24    -111   35.66
     -51   35.62     -46   35.46     -31   33.23     -16   35.72      -1   35.97
      14    33.7      29   35.15     509    34.5     704   35.04     719   35.71
    1424   34.65    1444   34.21    1819   34.42    1834   34.17  1936.4   34.34
  2045.5   34.52  2285.5   34.32  3385.5   33.97  3410.5   33.47  3430.5   33.98
  3480.5   33.87  3610.5   33.66  3625.5   34.06  3640.5   33.41  3655.5    33.2
  3700.5   34.07  3730.5   33.13  4268.9   32.72  4383.9   32.46  4408.9   32.13
  4428.5   32.53  4438.9   32.74  4448.9   32.49    4580   33.43    4705   33.08
    4730   32.64 4741.05   32.65 4802.53   32.51 4854.45   33.52  4910.1   33.81
 4953.01   33.12 4972.55   32.81 4977.92    30.5 4978.01   30.46    4986   27.02
 4991.91    22.1 4996.44   17.55 4996.53   18.03 4996.69   18.19 5001.22   16.71
 5003.17   17.65 5003.49   18.29 5009.49   19.25 5020.18    21.3 5030.46   27.18
  5040.5   33.92 5040.61      34 5042.21   35.07 5045.61    35.1 5081.98   35.47
 5127.66   35.07 5172.13   33.32 5222.35   33.57    5285   33.55  5286.4   33.55
  5301.4   33.05  5316.4   31.85  5346.4   28.14  5361.4   26.88  5366.4   26.24
  5376.4   25.89  5386.4   25.22  5396.4   25.35  5431.4   24.16  5441.4   23.56
  5586.4   23.24  5741.4   25.54  5751.4   25.96  5791.4    26.6  5826.4   28.25
  5836.4   28.94  5876.4   31.11  5886.4   31.38  5911.4   32.82  5931.4   33.33
  5941.4   33.26  5946.4   33.52    5980   33.65  5981.4   33.66  6061.4   32.89
  6086.4   33.17  6791.4   33.86  6816.4   34.28  6881.4   34.24  6906.4   33.79
  6956.4   34.51  6996.6   34.24  7001.4   34.21  7056.4   33.45  7062.6   33.44
  7091.4   33.37  7186.4   34.39  7221.1   32.46  7221.4   32.44  7301.4   36.33
    7343   37.52
BR D #Mann= 11
   -1181      .2   -1181     .99  1936.4     .06  4428.5     .14 4972.55     .04
 5042.21     .14    5285     .99    5980     .06  6996.6      .1  7062.6     .06
  7221.1      .1
BR D Banks=4972.55,5042.21
BC Design=,, 0 ,, 0 ,,,,,,
BC HTab HWMax=37.54

Type RM Length L Ch R = 1 ,49329.3 ,22,22,22
BEGIN DESCRIPTION:
Upstream Section of Bridge/Culvert/Weir. Previously 49696
END DESCRIPTION:
XS GIS Cut Line= 6
      3192393.39      13865447.1      3189314.74     13865317.39
      3187103.13     13865089.12      3186873.31     13865190.32
      3186124.23     13865295.33      3184104.28     13865543.51
#Sta/Elev= 30
   -1036   37.38    -616   35.55    -186   36.24  1936.4   34.34  3700.5   34.07
  4428.5   32.53    4580   33.43 4802.53   32.51  4910.1   33.81 4972.55   32.81
    4986   27.02 4996.44   17.55 5001.22   16.71 5003.49   18.29 5020.18    21.3
 5042.21   35.07 5127.66   35.07 5172.13   33.32    5285   33.55  5386.4   25.22
  5441.4   23.56  5586.4   23.24  5791.4    26.6  5911.4   32.82    5980   33.65
  6996.6    33.6  7062.6   33.47  7116.4   33.18  7221.1   35.33  7311.4   37.18
#Mann= 10 ,-1 , 0
   -1036     .99       0  1936.4     .06       0  4428.5     .14       0
 4972.55     .04       0 5042.21     .14       0    5285     .99       0
    5980     .06       0  6996.6      .1       0  7062.6     .06       0
  7221.1      .1       0
#XS Ineff= 2 , 0
       0    4969    31.9 5101.21       0   35.47
Permanent Ineff=
       F       F
Bank Sta=4972.55,5042.21
XS Rating Curve= 0
Exp/Cntr=.5,.3

Type RM Length L Ch R = 3 ,49318   ,,,
BEGIN DESCRIPTION:
24" DIAMETER PIPELINE - Skew 35 Degrees (Previously 49685.0)
END DESCRIPTION:
Bridge Culvert--1,0,-1,-1, 0
Deck Dist Width WeirC Skew NumUp NumDn MinLoCord MaxHiCord MaxSubmerge Is_Ogee
10,2,2.6,0, 60, 60, , , .95, 0, 1,1,,
   -1036    -891    -666    -616    -391    -316    -286    -186     -46      -1
      29     509     704     719    1424    1444    1819    1834  2045.5  3610.5
  3625.5  3655.5  3700.5  3730.5  4268.9  4408.9  4438.9  4448.9    4580 4802.53
 4854.45  4910.1 4972.55 4973.11    4986 5038.16 5042.21 5081.98 5127.66 5172.13
  5286.4  5301.4  5316.4  5346.4  5366.4  5386.4  5396.4  5441.4  5586.4  5741.4
  5791.4  5911.4  5946.4  5981.4  6061.4  6086.4  6791.4  6816.4  7116.4  7311.4
   37.38   36.03   35.95   35.55    35.7   35.42   36.07   36.24   35.46   35.97
   35.15    34.5   35.04   35.71   34.65   34.21   34.42   34.17   34.52   33.66
   34.06    33.2   34.07   33.13   32.72   32.13   32.74   32.49   33.43   32.51
   33.52   33.81   32.81   32.58   32.75   33.53   35.08   35.47   35.07   33.32
   33.55   33.05   31.85   28.14   26.24   25.22   25.35   23.56   23.24   25.54
    26.6   32.82   33.52   33.66   32.89   33.17   33.86   34.28   33.18   37.18
   37.38   36.03   35.95   35.55    35.7   35.42   36.07   36.24   35.46   35.97
   35.15    34.5   35.04   35.71   34.65   34.21   34.42   34.17   34.52   33.66
   34.06    33.2   34.07   33.13   32.72   32.13   32.74   32.49   33.43   32.51
   33.52   33.81   32.81   32.57   31.58   32.48   35.07   35.47   35.07   33.32
   33.55   33.05   31.85   28.14   26.24   25.22   25.35   23.56   23.24   25.54
    26.6   32.82   33.52   33.66   32.89   33.17   33.86   34.28   33.18   37.18
   -1036    -891    -666    -616    -391    -316    -286    -186     -46      -1
      29     509     704     719    1424    1444    1819    1834  2045.5  3610.5
  3625.5  3655.5  3700.5  3730.5  4268.9  4408.9  4438.9  4448.9    4580 4802.53
 4854.45  4910.1 4972.55 4973.11    4986 5038.16 5042.21 5081.98 5127.66 5172.13
  5286.4  5301.4  5316.4  5346.4  5366.4  5386.4  5396.4  5441.4  5586.4  5741.4
  5791.4  5911.4  5946.4  5981.4  6061.4  6086.4  6791.4  6816.4  7116.4  7311.4
   37.38   36.03   35.95   35.55    35.7   35.42   36.07   36.24   35.46   35.97
   35.15    34.5   35.04   35.71   34.65   34.21   34.42   34.17   34.52   33.66
   34.06    33.2   34.07   33.13   32.72   32.13   32.74   32.49   33.43   32.51
   33.52   33.81   32.81   32.58   32.75   33.53   35.08   35.47   35.07   33.32
   33.55   33.05   31.85   28.14   26.24   25.22   25.35   23.56   23.24   25.54
    26.6   32.82   33.52   33.66   32.89   33.17   33.86   34.28   33.18   37.18
   37.38   36.03   35.95   35.55    35.7   35.42   36.07   36.24   35.46   35.97
   35.15    34.5   35.04   35.71   34.65   34.21   34.42   34.17   34.52   33.66
   34.06    33.2   34.07   33.13   32.72   32.13   32.74   32.49   33.43   32.51
   33.52   33.81   32.81   32.57   31.58   32.48   35.07   35.47   35.07   33.32
   33.55   33.05   31.85   28.14   26.24   25.22   25.35   23.56   23.24   25.54
    26.6   32.82   33.52   33.66   32.89   33.17   33.86   34.28   33.18   37.18
BR Coef= 1 , 1 , 0 ,1.25, 0 ,,,.8,0,2,0,
WSPro=,,,, 1 ,,,, 0 ,,,, 0 ,,,,-1 ,-1 ,-1 , 0 , 0 , 0 , 0 , 0
BR U #Sta/Elev= 113
   -1036   37.38    -976   36.97    -931   36.52    -891   36.03    -666   35.95
    -661   35.85    -631   35.67    -616   35.55    -586   35.61    -391    35.7
    -316   35.42    -286   36.07    -186   36.24    -111   35.66     -51   35.62
     -46   35.46     -16   35.72      -1   35.97      29   35.15     509    34.5
     704   35.04     719   35.71    1424   34.65    1444   34.21    1819   34.42
    1834   34.17  1936.4   34.34  2045.5   34.52  2285.5   34.32  3385.5   33.97
  3430.5   33.98  3480.5   33.87  3610.5   33.66  3625.5   34.06  3640.5   33.41
  3655.5    33.2  3700.5   34.07  3730.5   33.13  4268.9   32.72  4383.9   32.46
  4408.9   32.13  4428.5   32.53  4438.9   32.74  4448.9   32.49    4580   33.43
    4705   33.08    4730   32.64 4741.05   32.65 4802.53   32.51 4854.45   33.52
  4910.1   33.81 4972.55   32.81 4972.91   32.66 4973.02   32.61 4973.11   32.57
    4986   27.02 4991.91    22.1 4996.44   17.55 4996.53   18.03 4996.69   18.19
 5001.22   16.71 5003.17   17.65 5003.49   18.29 5009.49   19.25 5020.18    21.3
 5030.46   27.18 5038.16   32.48 5042.21   35.07  5048.9   35.14 5049.01   35.14
 5051.01   35.16 5081.98   35.47 5127.66   35.07 5172.13   33.32 5222.35   33.57
    5285   33.55  5286.4   33.55  5301.4   33.05  5316.4   31.85  5346.4   28.14
  5361.4   26.88  5366.4   26.24  5376.4   25.89  5386.4   25.22  5396.4   25.35
  5431.4   24.16  5441.4   23.56  5586.4   23.24  5741.4   25.54  5751.4   25.96
  5791.4    26.6  5826.4   28.25  5836.4   28.94  5876.4   31.11  5886.4   31.38
  5911.4   32.82  5931.4   33.33  5941.4   33.26  5946.4   33.52    5980   33.65
  5981.4   33.66  6061.4   32.89  6086.4   33.17  6791.4   33.86  6816.4   34.28
  6881.4   34.24  6906.4   33.79  6996.6    33.6  7062.6   33.47  7066.4   33.46
  7116.4   33.18  7221.1   35.33  7311.4   37.18
BR U #Mann= 10
   -1036     .99  1936.4     .06  4428.5     .14 4972.55     .04 5042.21     .14
    5285     .99    5980     .06  6996.6      .1  7062.6     .06  7221.1      .1
BR U Banks=4972.55,5042.21
BR D #Sta/Elev= 113
   -1036   37.38    -976   36.97    -931   36.52    -891   36.03    -666   35.95
    -661   35.85    -631   35.67    -616   35.55    -586   35.61    -391    35.7
    -316   35.42    -286   36.07    -186   36.24    -111   35.66     -51   35.62
     -46   35.46     -16   35.72      -1   35.97      29   35.15     509    34.5
     704   35.04     719   35.71    1424   34.65    1444   34.21    1819   34.42
    1834   34.17  1936.4   34.34  2045.5   34.52  2285.5   34.32  3385.5   33.97
  3430.5   33.98  3480.5   33.87  3610.5   33.66  3625.5   34.06  3640.5   33.41
  3655.5    33.2  3700.5   34.07  3730.5   33.13  4268.9   32.72  4383.9   32.46
  4408.9   32.13  4428.5   32.53  4438.9   32.74  4448.9   32.49    4580   33.43
    4705   33.08    4730   32.64 4741.05   32.65 4802.53   32.51 4854.45   33.52
  4910.1   33.81 4972.55   32.81 4972.91   32.66 4973.02   32.61 4973.11   32.57
    4986   27.02 4991.91    22.1 4996.44   17.55 4996.53   18.03 4996.69   18.19
 5001.22   16.71 5003.17   17.65 5003.49   18.29 5009.49   19.25 5020.18    21.3
 5030.46   27.18 5038.16   32.48 5042.21   35.07  5048.9   35.14 5049.01   35.14
 5051.01   35.16 5081.98   35.47 5127.66   35.07 5172.13   33.32 5222.35   33.57
    5285   33.55  5286.4   33.55  5301.4   33.05  5316.4   31.85  5346.4   28.14
  5361.4   26.88  5366.4   26.24  5376.4   25.89  5386.4   25.22  5396.4   25.35
  5431.4   24.16  5441.4   23.56  5586.4   23.24  5741.4   25.54  5751.4   25.96
  5791.4    26.6  5826.4   28.25  5836.4   28.94  5876.4   31.11  5886.4   31.38
  5911.4   32.82  5931.4   33.33  5941.4   33.26  5946.4   33.52    5980   33.65
  5981.4   33.66  6061.4   32.89  6086.4   33.17  6791.4   33.86  6816.4   34.28
  6881.4   34.24  6906.4   33.79  6996.6    33.6  7062.6   33.47  7066.4   33.46
  7116.4   33.18  7221.1   35.33  7311.4   37.18
BR D #Mann= 10
   -1036     .99  1936.4     .06  4428.5     .14 4972.55     .04 5042.21     .14
    5285     .99    5980     .06  6996.6      .1  7062.6     .06  7221.1      .1
BR D Banks=4972.55,5042.21
BC Design=,, 0 ,, 0 ,,,,,,
BC HTab HWMax=37.38

Type RM Length L Ch R = 1 ,49307.3 ,298.1,298.1,298.1
BEGIN DESCRIPTION:
Downstream Section of Bridge/Culvert/Weir. Previously 49674
END DESCRIPTION:
XS GIS Cut Line= 6
      3192379.51     13865430.03      3189300.86     13865300.31
      3187089.25     13865072.04      3186859.43     13865173.24
      3186110.35     13865278.25       3184090.4     13865526.44
#Sta/Elev= 30
   -1036   37.37    -616   35.54    -186   36.23  1936.4   34.33  3700.5   34.06
  4428.5   32.52    4580   33.42 4802.53    32.5  4910.1    33.8 4972.55    32.8
    4986   27.01 4996.44   17.54 5001.22    16.7 5003.49   18.28 5020.18   21.29
 5042.21   35.06 5127.66   35.06 5172.13   33.31    5285   33.54  5386.4   25.21
  5441.4   23.55  5586.4   23.23  5791.4   26.59  5911.4   32.81    5980   33.64
  6996.6   33.59  7062.6   33.46  7116.4   33.17  7221.1   35.32  7311.4   37.17
#Mann= 10 ,-1 , 0
   -1036     .99       0  1936.4     .06       0  4428.5     .14       0
 4972.55     .04       0 5042.21     .14       0    5285     .99       0
    5980     .06       0  6996.6      .1       0  7062.6     .06       0
  7221.1      .1       0
#XS Ineff= 2 , 0
       0    4969    31.9 5052.11       0   35.06
Permanent Ineff=
       F       F
Bank Sta=4972.55,5042.21
XS Rating Curve= 0
Exp/Cntr=.5,.3

Type RM Length L Ch R = 1 ,49009.2 ,94.9,89.9,70.6
BEGIN DESCRIPTION:
Previously Cross Section 49375.9 - Interpolated
END DESCRIPTION:
XS GIS Cut Line= 6
      3190682.35     13865304.07       3189570.2     13865226.64
      3186255.48     13864961.06      3186006.71     13865169.49
      3185085.58     13865310.69      3184083.77     13865391.37
#Sta/Elev= 30
   456.4      35  3409.2    33.9  3439.2    33.1  3489.2    33.7  3519.2    33.2
  4904.3   32.99  4969.3   33.29  4991.2      18  4993.5   17.27    5003   16.56
  5008.8   17.89  5010.1    20.4  5014.2   21.16  5019.3   21.04    5040   33.24
  5056.7    32.1  5069.3    33.3  5076.7      34  5126.7    34.5  5176.7      33
  5231.2      34  6153.1    33.9  6583.1    34.7  6882.1    34.3  6962.1    33.7
  6992.1    32.8  7042.1    33.2  7072.1    36.1  7092.1      37  7158.2      36
#Mann= 5 ,-1 , 0
   456.4      .2       0  4904.3     .06       0  4969.3     .04       0
    5040     .06       0  5069.3      .2       0
Bank Sta=4969.3,5040
XS Rating Curve= 0
Exp/Cntr=.5,.3