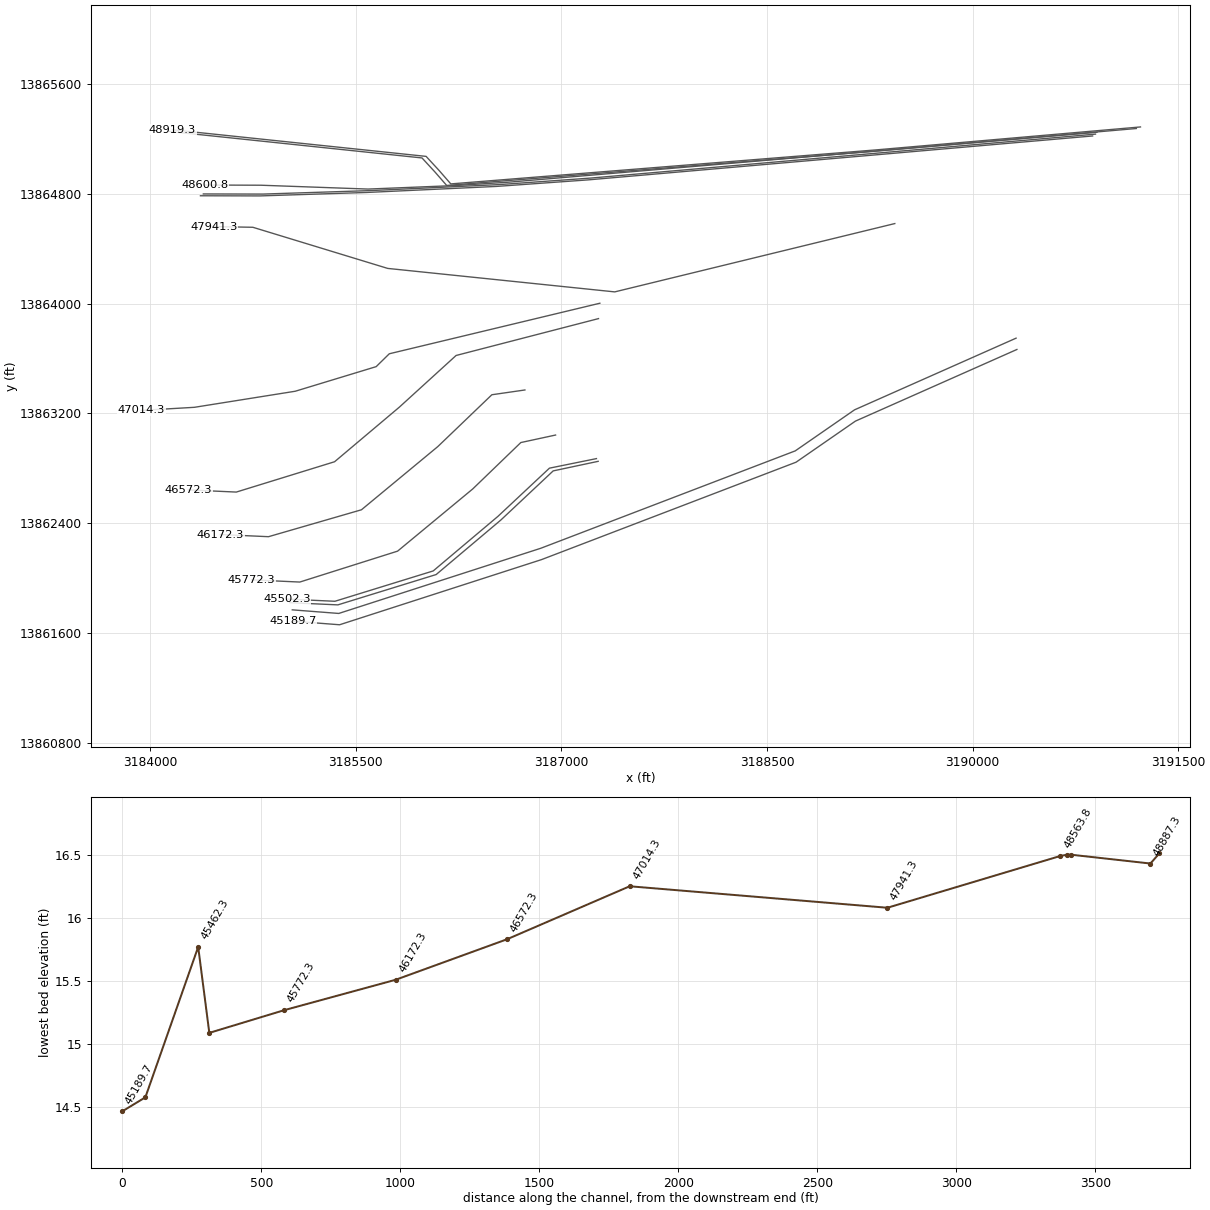
HEC-RAS study N100-00-00.prj: N100-00-00

--- N100-00-00.g01 (geometry) --- (continued)

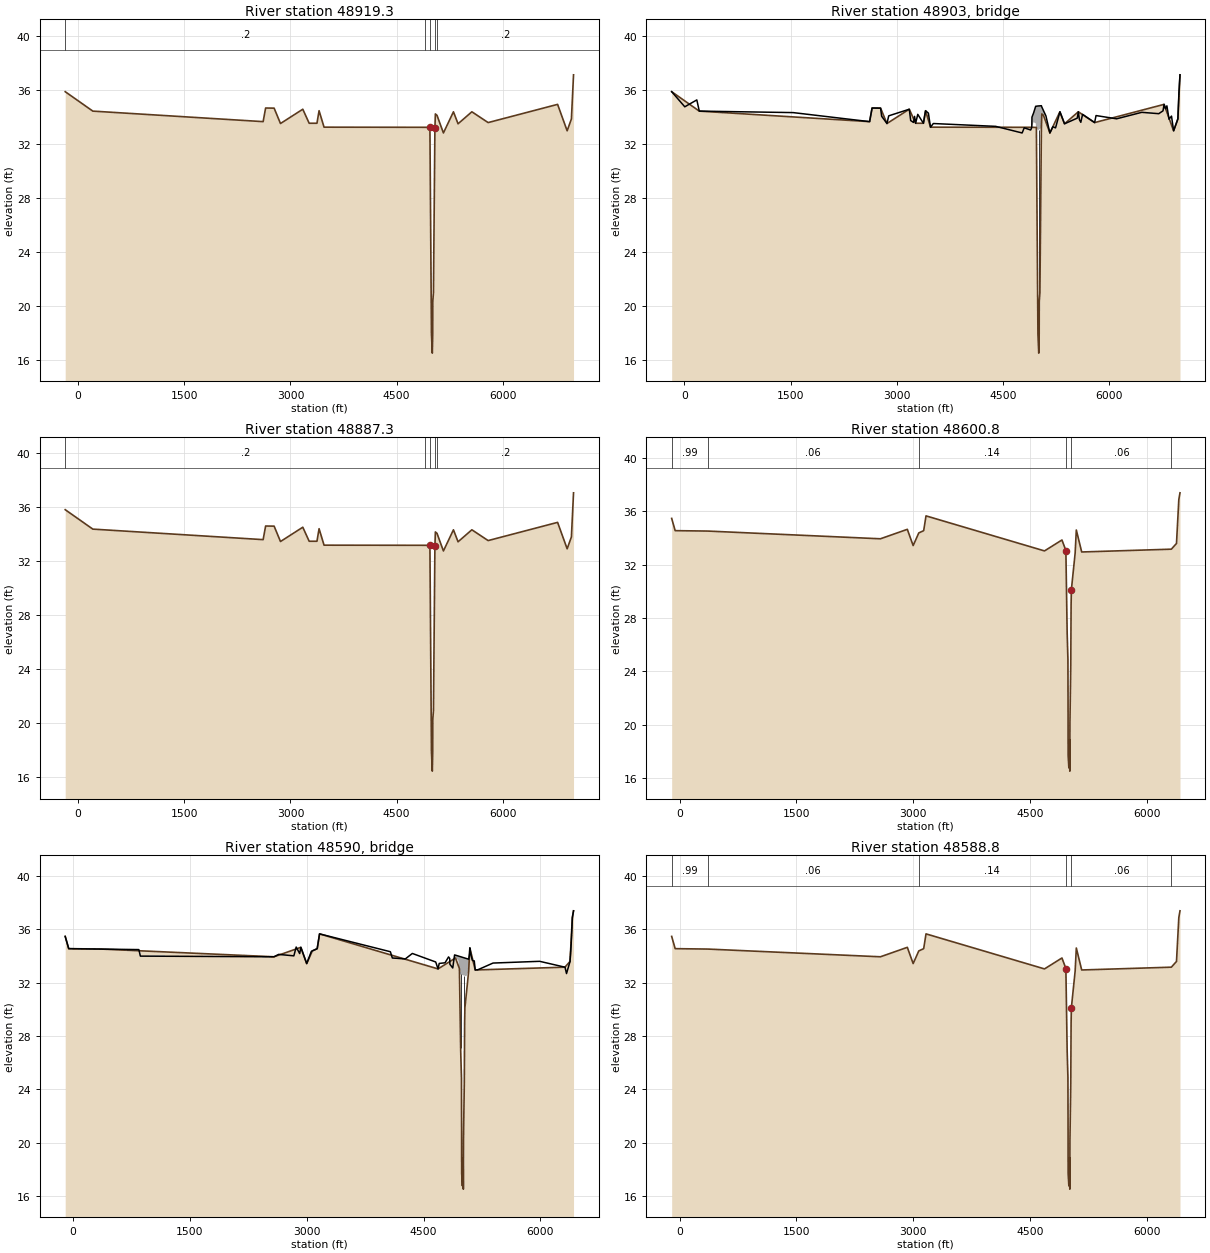
Type RM Length L Ch R = 1 ,48919.3 ,32,32,32
BEGIN DESCRIPTION:
Upstream Section of Bridge/Culvert/Weir. Previously 49286
END DESCRIPTION:
XS GIS Cut Line= 6
      3191224.73      13865285.6      3189292.91     13865118.29
      3186193.48       13864871.      3186107.49      13864969.5
       3186013.4     13865071.32      3184163.23     13865264.93
#Sta/Elev= 30
  -180.7   35.89   209.3   34.45  2614.3   33.67  2649.3   34.68  2769.3   34.67
  2859.3   33.53  3174.3   34.59  3264.3   33.55  3374.3   33.55  3404.3   34.48
  3474.3   33.26  4904.3   33.25  4969.3   33.24  4991.2   17.95    5003   16.51
  5008.8   17.84  5010.1   20.35  5019.3   20.99    5040   33.19  5046.4   34.24
  5069.3   34.14  5160.2   32.83  5301.7    34.4  5366.7   33.51  5561.7    34.4
  5791.7    33.6  6772.4   34.95  6907.4   32.99  6967.4   33.87  6997.4   37.14
#Mann= 5 ,-1 , 0
  -180.7      .2       0  4904.3     .06       0  4969.3     .04       0
    5040     .06       0  5069.3      .2       0
#XS Ineff= 2 , 0
       0    4960    32.7    5050       0    32.6
Permanent Ineff=
       F       F
Bank Sta=4969.3,5040
XS Rating Curve= 0
Exp/Cntr=.5,.3

Type RM Length L Ch R = 3 ,48903   ,,,
Bridge Culvert--1,0,-1,-1, 0
Deck Dist Width WeirC Skew NumUp NumDn MinLoCord MaxHiCord MaxSubmerge Is_Ogee
10,12,2.6,0, 60, 60, , , .95, 0, 1,1,,
  -180.7     4.3   174.3   209.3  1534.3  2614.3  2649.3  2769.3  2784.3  2859.3
  2884.3  3174.3  3194.3  3234.3  3249.3  3264.3  3294.3  3374.3  3404.3  3444.3
  3474.3  3514.3  4395.1    4768  4797.9    4889  4904.3  4906.8  4929.6  4959.6
  4964.7  4991.1    5040  5046.4  5103.8  5160.2  5201.4  5240.3  5301.7  5366.7
  5546.7  5561.7  5576.7  5596.7  5621.7  5791.7  5811.7  6102.4  6457.4  6697.4
  6757.4  6772.4  6792.4  6812.4  6842.4  6877.4  6907.4  6967.4  6982.4  6997.4
   35.89   34.77   35.28   34.45   34.34   33.67   34.68   34.67   34.07   33.53
    34.1   34.59   33.75   33.61   34.06   33.55   34.21   33.55   34.48    34.3
   33.26   33.53   33.32   32.83   33.21   33.05   33.25      34   34.31   34.81
   34.81   34.83   34.85   34.75    34.1   32.83   33.29   33.21    34.4   33.51
   33.93    34.4   33.82   33.62   34.21    33.6   34.12   33.88   34.36   34.26
   34.47   34.95   34.62   34.84   33.85   34.08   32.99   33.87   35.84   37.14
   35.89   34.77   35.28   34.45   34.34   33.67   34.68   34.67   34.07   33.53
    34.1   34.59   33.75   33.61   34.06   33.55   34.21   33.55   34.48    34.3
   33.26   33.53   33.32   32.83   33.21   33.05   33.25   33.29   33.63   33.55
   33.16   33.03   33.19   34.24    34.1   32.83   33.29   33.21    34.4   33.51
   33.93    34.4   33.82   33.62   34.21    33.6   34.12   33.88   34.36   34.26
   34.47   34.95   34.62   34.84   33.85   34.08   32.99   33.87   35.84   37.14
  -180.7     4.3   174.3   209.3  1534.3  2614.3  2649.3  2769.3  2784.3  2859.3
  2884.3  3174.3  3194.3  3234.3  3249.3  3264.3  3294.3  3374.3  3404.3  3444.3
  3474.3  3514.3  4395.1    4768  4797.9    4889  4904.3  4906.8  4929.6  4959.6
  4964.7  4991.1    5040  5046.4  5103.8  5160.2  5201.4  5240.3  5301.7  5366.7
  5546.7  5561.7  5576.7  5596.7  5621.7  5791.7  5811.7  6102.4  6457.4  6697.4
  6757.4  6772.4  6792.4  6812.4  6842.4  6877.4  6907.4  6967.4  6982.4  6997.4
   35.89   34.77   35.28   34.45   34.34   33.67   34.68   34.67   34.07   33.53
    34.1   34.59   33.75   33.61   34.06   33.55   34.21   33.55   34.48    34.3
   33.26   33.53   33.32   32.83   33.21   33.05   33.25      34   34.31   34.81
   34.81   34.83   34.85   34.75    34.1   32.83   33.29   33.21    34.4   33.51
   33.93    34.4   33.82   33.62   34.21    33.6   34.12   33.88   34.36   34.26
   34.47   34.95   34.62   34.84   33.85   34.08   32.99   33.87   35.84   37.14
   35.81   34.69    35.2   34.37   34.26   33.59    34.6   34.59   33.99   33.45
   34.02   34.51   33.67   33.53   33.98   33.47   34.13   33.47    34.4   34.22
   33.18   33.45   33.24   32.75   33.13   32.97   33.17   33.21   33.55   33.47
   33.08   32.95   33.11   34.16   34.02   32.75   33.21   33.13   34.32   33.43
   33.85   34.32   33.74   33.54   34.13   33.52   34.04    33.8   34.28   34.18
   34.39   34.87   34.54   34.76   33.77      34   32.91   33.79   35.76   37.06
Pier Skew, UpSta & Num, DnSta & Num=  ,5000.5, 2 ,5000.5, 2 , 0 , 0 , 0 ,,
     1.7     1.7
   15.87   34.03
     1.7     1.7
   15.79   33.95
Abutment Skew #Up #Dn= , 2 , 2
  4959.6  4991.2
   33.54   17.95
  4959.6  4991.2
   33.46   17.87
Abutment Skew #Up #Dn= , 2 , 2
  5040.1 5042.99
   33.21    33.8
  5040.1 5042.99
   33.13   33.72
BR Coef= 1 , 1 , 0 ,1.25, 0 ,,,.8,0,2,1,
WSPro=,,,, 1 ,,,, 0 ,,,, 0 ,,,,-1 ,-1 ,-1 , 0 , 0 , 0 , 0 , 0
BC Design=,, 0 ,, 0 ,,,,,,
BC HTab HWMax=37.14

Type RM Length L Ch R = 1 ,48887.3 ,286.5,286.5,286.5
BEGIN DESCRIPTION:
Downstream Section of Bridge/Culvert/Weir. Previously 49254
END DESCRIPTION:
XS GIS Cut Line= 6
      3191194.81     13865274.25      3189262.99     13865106.95
      3186163.56     13864859.66      3186077.57     13864958.16
      3185983.48     13865059.98      3184133.31     13865253.59
#Sta/Elev= 30
  -180.7   35.81   209.3   34.37  2614.3   33.59  2649.3    34.6  2769.3   34.59
  2859.3   33.45  3174.3   34.51  3264.3   33.47  3374.3   33.47  3404.3    34.4
  3474.3   33.18  4904.3   33.17  4969.3   33.16  4991.2   17.87    5003   16.43
  5008.8   17.76  5010.1   20.27  5019.3   20.91    5040   33.11  5046.4   34.16
  5069.3   34.06  5160.2   32.75  5301.7   34.32  5366.7   33.43  5561.7   34.32
  5791.7   33.52  6772.4   34.87  6907.4   32.91  6967.4   33.79  6997.4   37.06
#Mann= 5 ,-1 , 0
  -180.7      .2       0  4904.3     .06       0  4969.3     .04       0
    5040     .06       0  5069.3      .2       0
#XS Ineff= 2 , 0
       0    4960    32.7    5050       0    32.6
Permanent Ineff=
       F       F
Bank Sta=4969.3,5040
XS Rating Curve= 0
Exp/Cntr=.5,.3

Type RM Length L Ch R = 1 ,48600.8 ,12,12,12
BEGIN DESCRIPTION:
Upstream Section of Bridge/Culvert/Weir. Previously 48967.5
END DESCRIPTION:
XS GIS Cut Line= 6
      3190907.47     13865246.99      3186609.41     13864883.07
      3186224.22       13864859.      3185589.56     13864833.45
      3184808.61     13864861.41       3184399.3     13864862.77
#Sta/Elev= 30
  -100.6   35.47   -55.6   34.55   360.1   34.52  2579.4   33.94  2924.4   34.65
  2999.4   33.43  3071.7   34.38  3134.4   34.55  3164.4   35.66  4685.5   33.03
 4909.39   33.85 4959.78   33.06 4976.31   26.88 4986.17   24.87  4988.1   20.86
 4988.79    17.7 4998.36   16.74 5007.43   18.85 5010.45    16.5 5011.87   20.12
 5022.65   24.49 5026.81   28.99 5030.51   30.12 5078.85   32.87 5093.84    34.6
 5162.92   32.95  6313.9   33.16  6379.8   33.59  6409.8   36.89  6424.8   37.39
#Mann= 6 ,-1 , 0
  -100.6     .99       0   360.1     .06       0  3071.7     .14       0
 4959.78     .04       0 5030.51     .06       0  6313.9      .1       0
#XS Ineff= 2 , 0
       0    4918   33.15    5113       0    32.5
Permanent Ineff=
       F       F
Bank Sta=4959.78,5030.51
XS Rating Curve= 0
Exp/Cntr=.5,.3

Type RM Length L Ch R = 3 ,48590   ,,,
BEGIN DESCRIPTION:
12" DIAMETER PIPELINE - Skewed 55 Degrees
END DESCRIPTION:
Bridge Culvert--1,0,-1,-1, 0
Deck Dist Width WeirC Skew NumUp NumDn MinLoCord MaxHiCord MaxSubmerge Is_Ogee
10,1,2.6,0, 48, 48, , , .95, 0, 1,1,,
  -100.6   -55.6   844.4   864.4  2579.4  2639.4  2834.4  2864.4  2909.4  2924.4
  2999.4  3059.4  3134.4  3164.4  4073.6  4098.6  4265.5  4355.5  4655.5  4685.5
  4700.5  4775.5  4820.5  4835.5 4837.51 4874.28 4897.63 4909.39 4945.01 4959.78
 4966.62 5049.55 5078.85 5090.32 5093.84  5108.6 5126.16 5150.43 5162.92 5198.09
  5391.6  5989.8  6314.8  6334.8  6379.8  6394.8  6409.8  6424.8
   35.47   34.55   34.48   33.99   33.94   34.12   34.01   34.67   34.18   34.65
   33.43   34.35   34.55   35.66   34.32   33.85   33.78   34.19   33.55   33.03
   33.44   33.49   33.93   33.81   33.38    33.1   34.08   34.06      34   33.97
   33.96   33.81   33.76    34.2   34.61   34.06   33.67   33.63   32.95   32.97
   33.47    33.6   33.16   32.68   33.59    34.9   36.89   37.39
   35.47   34.55   34.48   33.99   33.94   34.12   34.01   34.67   34.18   34.65
   33.43   34.35   34.55   35.66   34.32   33.85   33.78   34.19   33.55   33.03
   33.44   33.49   33.93   33.81   33.38    33.1    33.6   33.85   33.68   33.06
   32.63   32.48   32.87   34.19    34.6   34.05   33.66   33.19   32.95   32.97
   33.47    33.6   33.16   32.68   33.59    34.9   36.89   37.39
  -100.6   -55.6   844.4   864.4  2579.4  2639.4  2834.4  2864.4  2909.4  2924.4
  2999.4  3059.4  3134.4  3164.4  4073.6  4098.6  4265.5  4355.5  4655.5  4685.5
  4700.5  4775.5  4820.5  4835.5 4837.51 4874.28 4897.63 4909.39 4945.01 4959.78
 4966.62 5049.55 5078.85 5090.32 5093.84  5108.6 5126.16 5150.43 5162.92 5198.09
  5391.6  5989.8  6314.8  6334.8  6379.8  6394.8  6409.8  6424.8
   35.47   34.55   34.48   33.99   33.94   34.12   34.01   34.67   34.18   34.65
   33.43   34.35   34.55   35.66   34.32   33.85   33.78   34.19   33.55   33.03
   33.44   33.49   33.93   33.81   33.38    33.1   34.08   34.06      34   33.97
   33.96   33.81   33.76    34.2   34.61   34.06   33.67   33.63   32.95   32.97
   33.47    33.6   33.16   32.68   33.59    34.9   36.89   37.39
   35.47   34.55   34.48   33.99   33.94   34.12   34.01   34.67   34.18   34.65
   33.43   34.35   34.55   35.66   34.32   33.85   33.78   34.19   33.55   33.03
   33.44   33.49   33.93   33.81   33.38    33.1    33.6   33.85   33.68   33.06
   32.63   32.48   32.87   34.19    34.6   34.05   33.66   33.19   32.95   32.97
   33.47    33.6   33.16   32.68   33.59    34.9   36.89   37.39
Pier Skew, UpSta & Num, DnSta & Num=  ,4975.7, 2 ,4975.7, 2 , 0 , 0 , 0 ,,
       1       1
   25.91   33.61
       1       1
   25.91   33.61
Pier Skew, UpSta & Num, DnSta & Num=  ,5021.2, 2 ,5021.2, 2 , 0 , 0 , 0 ,,
       1       1
   22.72   33.53
       1       1
   22.72   33.53
BR Coef=-1 , 1 , 0 ,1.25, 0 ,,,.8,0,2,0,
WSPro=,,,, 1 ,,,, 0 ,,,, 0 ,,,,-1 ,-1 ,-1 , 0 , 0 , 0 , 0 , 0
BC Design=,, 0 ,, 0 ,,,,,,
BC HTab HWMax=37.39

Type RM Length L Ch R = 1 ,48588.8 ,25,25,25
BEGIN DESCRIPTION:
Upstream Section of Bridge/Culvert/Weir. Previously 48955.5
END DESCRIPTION:
XS GIS Cut Line= 6
      3190896.67     13865233.36      3187216.34     13864913.63
      3186546.09     13864865.98      3185600.99     13864822.09
      3184823.18       13864797.      3184388.26     13864798.05
#Sta/Elev= 30
  -100.6   35.47   -55.6   34.55   360.1   34.52  2579.4   33.94  2924.4   34.65
  2999.4   33.43  3071.7   34.38  3134.4   34.55  3164.4   35.66  4685.5   33.03
 4909.39   33.85 4959.78   33.06 4976.31   26.88 4986.17   24.87  4988.1   20.86
 4988.79    17.7 4998.36   16.74 5007.43   18.85 5010.45    16.5 5011.87   20.12
 5022.65   24.49 5026.81   28.99 5030.51   30.12 5078.85   32.87 5093.84    34.6
 5162.92   32.95  6313.9   33.16  6379.8   33.59  6409.8   36.89  6424.8   37.39
#Mann= 6 ,-1 , 0
  -100.6     .99       0   360.1     .06       0  3071.7     .14       0
 4959.78     .04       0 5030.51     .06       0  6313.9      .1       0
#XS Ineff= 2 , 0
       0    4916    33.7    5080       0    32.5
Permanent Ineff=
       F       F
Bank Sta=4959.78,5030.51
XS Rating Curve= 0
Exp/Cntr=.5,.3

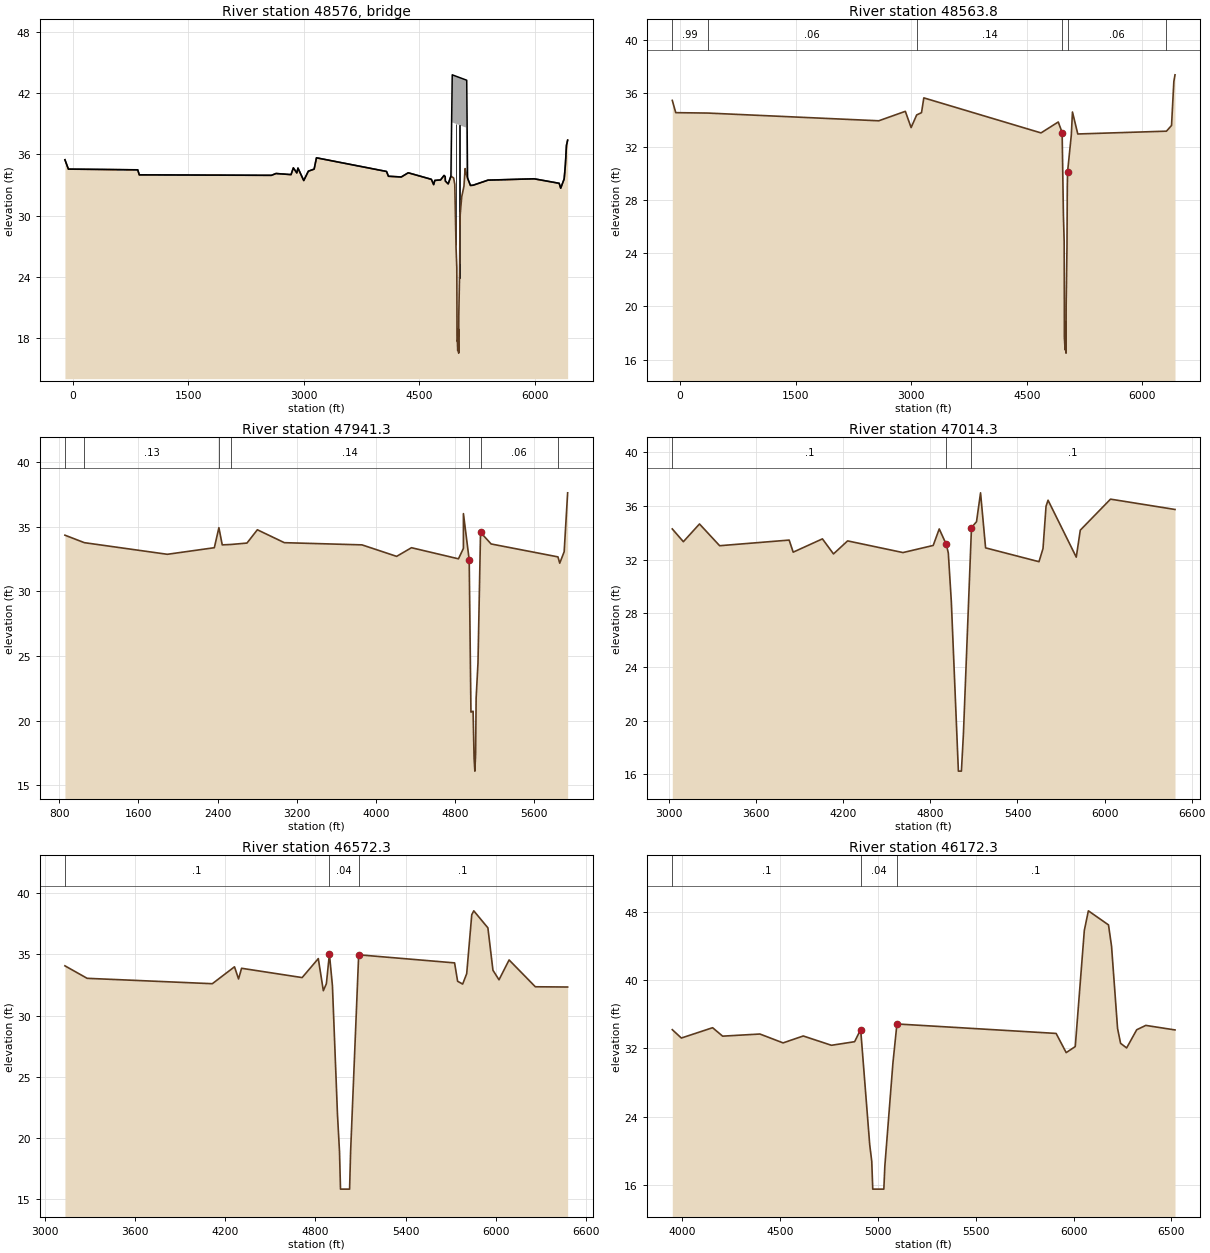
Type RM Length L Ch R = 3 ,48576   ,,,
BEGIN DESCRIPTION:
5' DIAMETER PIPELINE - 55 Degree Skew (Previously 48943.0)
END DESCRIPTION:
Bridge Culvert--1,0,-1,-1, 0
Deck Dist Width WeirC Skew NumUp NumDn MinLoCord MaxHiCord MaxSubmerge Is_Ogee
10,5,2.6,0, 44, 44, , , .95, 0, 1,1,,
  -100.6   -55.6   844.4   864.4  2579.4  2639.4  2834.4  2864.4  2909.4  2924.4
  2999.4  3059.4  3134.4  3164.4  4073.6  4098.6  4265.5  4355.5  4655.5  4685.5
  4700.5  4775.5  4820.5  4835.5 4837.51 4874.28 4909.39 4926.73 4926.84 4926.93
 5104.82 5104.93 5114.93 5126.16 5162.92 5198.09  5391.6  5989.8  6314.8  6334.8
  6379.8  6394.8  6409.8  6424.8
   35.47   34.55   34.48   33.99   33.94   34.12   34.01   34.67   34.18   34.65
   33.43   34.35   34.55   35.66   34.32   33.85   33.78   34.19   33.55   33.03
   33.44   33.49   33.93   33.81   33.38    33.1   33.85    43.8    43.8    43.8
    43.3    43.3   43.27   33.66   32.95   32.97   33.47    33.6   33.16   32.68
   33.59    34.9   36.89   37.39
   35.47   34.55   34.48   33.99   33.94   34.12   34.01   34.67   34.18   34.65
   33.43   34.35   34.55   35.66   34.32   33.85   33.78   34.19   33.55   33.03
   33.44   33.49   33.93   33.81   33.38    33.1   33.85   33.77   33.77   39.13
   38.63   34.19   33.91   33.66   32.95   32.97   33.47    33.6   33.16   32.68
   33.59    34.9   36.89   37.39
  -100.6   -55.6   844.4   864.4  2579.4  2639.4  2834.4  2864.4  2909.4  2924.4
  2999.4  3059.4  3134.4  3164.4  4073.6  4098.6  4265.5  4355.5  4655.5  4685.5
  4700.5  4775.5  4820.5  4835.5 4837.51 4874.28 4909.39 4926.73 4926.84 4926.93
 5104.82 5104.93 5114.93 5126.16 5162.92 5198.09  5391.6  5989.8  6314.8  6334.8
  6379.8  6394.8  6409.8  6424.8
   35.47   34.55   34.48   33.99   33.94   34.12   34.01   34.67   34.18   34.65
   33.43   34.35   34.55   35.66   34.32   33.85   33.78   34.19   33.55   33.03
   33.44   33.49   33.93   33.81   33.38    33.1   33.85    43.8    43.8    43.8
    43.3    43.3   43.27   33.66   32.95   32.97   33.47    33.6   33.16   32.68
   33.59    34.9   36.89   37.39
   35.47   34.55   34.48   33.99   33.94   34.12   34.01   34.67   34.18   34.65
   33.43   34.35   34.55   35.66   34.32   33.85   33.78   34.19   33.55   33.03
   33.44   33.49   33.93   33.81   33.38    33.1   33.85   33.77   33.77   39.13
   38.63   34.19   33.91   33.66   32.95   32.97   33.47    33.6   33.16   32.68
   33.59    34.9   36.89   37.39
Pier Skew, UpSta & Num, DnSta & Num=  ,4975.7, 2 ,4975.7, 2 , 0 , 0 , 0 ,,
       1       1
   25.91   39.99
       1       1
   25.91   39.99
Pier Skew, UpSta & Num, DnSta & Num=  ,5021.2, 2 ,5021.2, 2 , 0 , 0 , 0 ,,
       1       1
   22.72   39.87
       1       1
   22.72   39.87
BR Coef= 1 , 1 , 0 ,1.25, 0 ,,,.8,0,2,0,
WSPro=,,,, 1 ,,,, 0 ,,,, 0 ,,,,-1 ,-1 ,-1 , 0 , 0 , 0 , 0 , 0
BR U #Sta/Elev= 67
  -100.6   35.47   -55.6   34.55   360.1   34.52   844.4   34.48   864.4   33.99
  2579.4   33.94  2639.4   34.12  2834.4   34.01  2864.4   34.67  2909.4   34.18
  2924.4   34.65  2999.4   33.43  3059.4   34.35  3071.7   34.38  3134.4   34.55
  3164.4   35.66  4073.6   34.32  4098.6   33.85  4265.5   33.78  4355.5   34.19
  4655.5   33.55  4685.5   33.03  4700.5   33.44  4775.5   33.49  4820.5   33.93
  4835.5   33.81 4837.51   33.38 4874.28    33.1 4909.39   33.85 4926.73   33.77
 4926.84   33.77 4926.93   33.77 4945.01   33.68 4959.78   33.06 4966.62   30.61
 4976.31   26.88 4986.17   24.87  4988.1   20.86 4988.79    17.7 4993.12   17.73
 4998.36   16.74 5007.43   18.85 5010.45    16.5 5011.87   20.12  5012.1   20.26
 5022.65   24.49 5026.81   28.99 5030.51   30.12 5049.55   31.82 5078.85   32.87
 5093.84    34.6 5104.82   34.19 5104.93   34.19  5108.6   34.05 5114.93   33.91
 5126.16   33.66 5162.92   32.95 5198.09   32.97  5391.6   33.47  5989.8    33.6
  6313.9   33.16  6314.8   33.16  6334.8   32.68  6379.8   33.59  6394.8    34.9
  6409.8   36.89  6424.8   37.39
BR U #Mann= 6
  -100.6     .99   360.1     .06  3071.7     .14 4959.78     .04 5030.51     .06
  6313.9      .1
BR U Banks=4959.78,5030.51
BR D #Sta/Elev= 67
  -100.6   35.47   -55.6   34.55   360.1   34.52   844.4   34.48   864.4   33.99
  2579.4   33.94  2639.4   34.12  2834.4   34.01  2864.4   34.67  2909.4   34.18
  2924.4   34.65  2999.4   33.43  3059.4   34.35  3071.7   34.38  3134.4   34.55
  3164.4   35.66  4073.6   34.32  4098.6   33.85  4265.5   33.78  4355.5   34.19
  4655.5   33.55  4685.5   33.03  4700.5   33.44  4775.5   33.49  4820.5   33.93
  4835.5   33.81 4837.51   33.38 4874.28    33.1 4909.39   33.85 4926.73   33.77
 4926.84   33.77 4926.93   33.77 4945.01   33.68 4959.78   33.06 4966.62   30.61
 4976.31   26.88 4986.17   24.87  4988.1   20.86 4988.79    17.7 4993.12   17.73
 4998.36   16.74 5007.43   18.85 5010.45    16.5 5011.87   20.12  5012.1   20.26
 5022.65   24.49 5026.81   28.99 5030.51   30.12 5049.55   31.82 5078.85   32.87
 5093.84    34.6 5104.82   34.19 5104.93   34.19  5108.6   34.05 5114.93   33.91
 5126.16   33.66 5162.92   32.95 5198.09   32.97  5391.6   33.47  5989.8    33.6
  6313.9   33.16  6314.8   33.16  6334.8   32.68  6379.8   33.59  6394.8    34.9
  6409.8   36.89  6424.8   37.39
BR D #Mann= 6
  -100.6     .99   360.1     .06  3071.7     .14 4959.78     .04 5030.51     .06
  6313.9      .1
BR D Banks=4959.78,5030.51
BC Design=,, 0 ,, 0 ,,,,,,
BC HTab HWMax=37.39

Type RM Length L Ch R = 1 ,48563.8 ,622.5,622.5,622.5
BEGIN DESCRIPTION:
Downstream Section of Bridge/Culvert/Weir. Previously 48930.5
END DESCRIPTION:
XS GIS Cut Line= 6
      3190875.56     13865219.97      3187195.24     13864900.23
      3186524.99     13864852.58      3185579.89     13864808.69
      3184802.08      13864783.6      3184367.15     13864784.66
#Sta/Elev= 30
  -100.6   35.46   -55.6   34.54   360.1   34.51  2579.4   33.93  2924.4   34.64
  2999.4   33.42  3071.7   34.37  3134.4   34.54  3164.4   35.65  4685.5   33.02
 4909.39   33.84 4959.78   33.05 4976.31   26.87 4986.17   24.86  4988.1   20.85
 4988.79   17.69 4998.36   16.73 5007.43   18.84 5010.45   16.49 5011.87   20.11
 5022.65   24.48 5026.81   28.98 5030.51   30.11 5078.85   32.86 5093.84   34.59
 5162.92   32.94  6313.9   33.15  6379.8   33.58  6409.8   36.88  6424.8   37.38
#Mann= 6 ,-1 , 0
  -100.6     .99       0   360.1     .06       0  3071.7     .14       0
 4959.78     .04       0 5030.51     .06       0  6313.9      .1       0
#XS Ineff= 2 , 0
       0    4916    33.7    5080       0    32.5
Permanent Ineff=
       F       F
Bank Sta=4959.78,5030.51
XS Rating Curve= 0
Exp/Cntr=.5,.3

Type RM Length L Ch R = 1 ,47941.3 ,927,927,927
BEGIN DESCRIPTION:
Previously Cross Section 48308
Located At: 3RD XS US WALLISVILLE
END DESCRIPTION:
XS GIS Cut Line= 5
      3189432.51     13864582.31      3187389.52     13864084.98
      3185733.35     13864255.85      3184749.54     13864555.27
      3184464.56     13864560.36
#Sta/Elev= 30
     857   34.35  1053.6   33.77    1892   32.87    2367   33.38  2413.2   34.93
    2447    33.6  2535.3   33.63    2697   33.74    2802   34.77  3074.6   33.77
  3859.6    33.6  4209.6   32.71  4359.6   33.38  4834.6   32.52  4884.6   33.33
  4884.7   36.02    4943   32.44  4960.7   20.65  4982.4   20.72  4992.5   17.07
  5000.3   16.08    5008   17.44  5013.1   21.73  5031.8   24.45  5057.6   34.57
  5164.6   33.67  5840.2   32.67    5858   32.18    5903   33.07    5938   37.63
#Mann= 7 ,-1 , 0
     857     .06       0  1053.6     .13       0  2413.2     .06       0
  2535.3     .14       0    4943     .04       0  5057.6     .06       0
  5840.2      .1       0
Bank Sta=4943,5057.6
XS Rating Curve= 0
Exp/Cntr=.3,.1

Type RM Length L Ch R = 1 ,47014.3 ,442,442,442
BEGIN DESCRIPTION:
End Channel Improvements
END DESCRIPTION:
XS GIS Cut Line= 6
      3187280.91     13864002.35     3185744.885      13863634.5
     3185649.127     13863540.87     3185058.667     13863361.75
     3184323.265     13863244.82     3183935.343     13863222.22
#Sta/Elev= 30
  3022.1   34.29 3098.45   33.34 3209.51   34.66 3348.34   33.04 3827.29   33.46
 3855.05   32.56 4056.35   33.55  4132.7   32.43 4229.88    33.4  4611.4   32.53
 4819.53   33.06 4861.18   34.29 4909.76   33.14 4923.65    32.5 4944.47   28.88
 4993.06   16.25 5013.88   16.25 5027.77   19.02  5083.3   34.39    5118   34.83
 5145.77   36.98 5180.47   32.88 5548.34   31.85 5576.11   32.83 5596.93   35.98
 5610.82   36.43 5805.17   32.19 5832.94    34.2 6041.17   36.51 6485.41   35.74
#Mann= 3 , 0 , 0
  3022.1      .1       0 4909.76     .04       0  5083.3      .1       0
Bank Sta=4909.76,5083.3
XS Rating Curve= 0
Exp/Cntr=.3,.1

Type RM Length L Ch R = 1 ,46572.3 ,400,400,400
BEGIN DESCRIPTION:
Channel Improvements
END DESCRIPTION:
XS GIS Cut Line= 6
      3187270.97      13863890.5      3186232.04     13863622.07
      3185817.86     13863245.73     3185345.635     13862848.58
     3184628.657     13862627.81     3184277.817      13862643.7
#Sta/Elev= 30
 3133.16   34.06 3280.91   33.04 4113.66    32.6 4261.27   33.98 4288.13   32.99
 4308.28   33.86 4711.23    33.1 4818.68   34.65 4852.26   32.03  4872.4    32.6
 4892.55   35.02  4912.7   32.44 4946.28   21.92 4959.71   18.91 4966.42   15.83
 5026.86   15.83 5033.58   18.88 5087.31   34.96  5725.3    34.3 5745.45    32.8
 5779.03   32.57 5805.89   33.42 5839.47   38.23  5852.9   38.55 5946.92   37.16
  5980.5    33.7 6020.79   32.92 6087.95   34.54 6262.48   32.35 6477.38   32.33
#Mann= 3 , 0 , 0
 3133.16      .1       0 4892.55     .04       0 5087.31      .1       0
Bank Sta=4892.55,5087.31
XS Rating Curve= 0
Exp/Cntr=.3,.1

Type RM Length L Ch R = 1 ,46172.3 ,400,400,400
BEGIN DESCRIPTION:
Channel Improvements
END DESCRIPTION:
XS GIS Cut Line= 6
       3186734.1     13863371.04     3186493.016     13863336.24
     3186098.815     13862958.99     3185541.742     13862498.92
      3184863.53       13862303.      3184512.69      13862318.9
#Sta/Elev= 30
 3950.02    34.2 3996.35   33.22 4155.94   34.43 4207.21   33.44 4397.68   33.69
 4516.09   32.65 4619.05   33.46 4763.19   32.37 4881.59   32.79 4912.48   34.22
 4958.81    20.7 4969.11   18.78 4974.26   15.51 5030.89   15.51 5036.03   18.22
 5077.22   30.27 5097.81   34.87  5911.1   33.76 5962.58   31.51 6008.91   32.22
 6055.24   45.83 6075.83   48.13 6178.75   46.48 6194.19   44.01 6225.08   34.34
 6240.52    32.6 6271.41   32.06 6322.89   34.19 6369.22    34.7 6518.52   34.17
#Mann= 3 , 0 , 0
 3950.02      .1       0 4912.48     .04       0 5097.81      .1       0
Bank Sta=4912.48,5097.81
XS Rating Curve= 0
Exp/Cntr=.3,.1

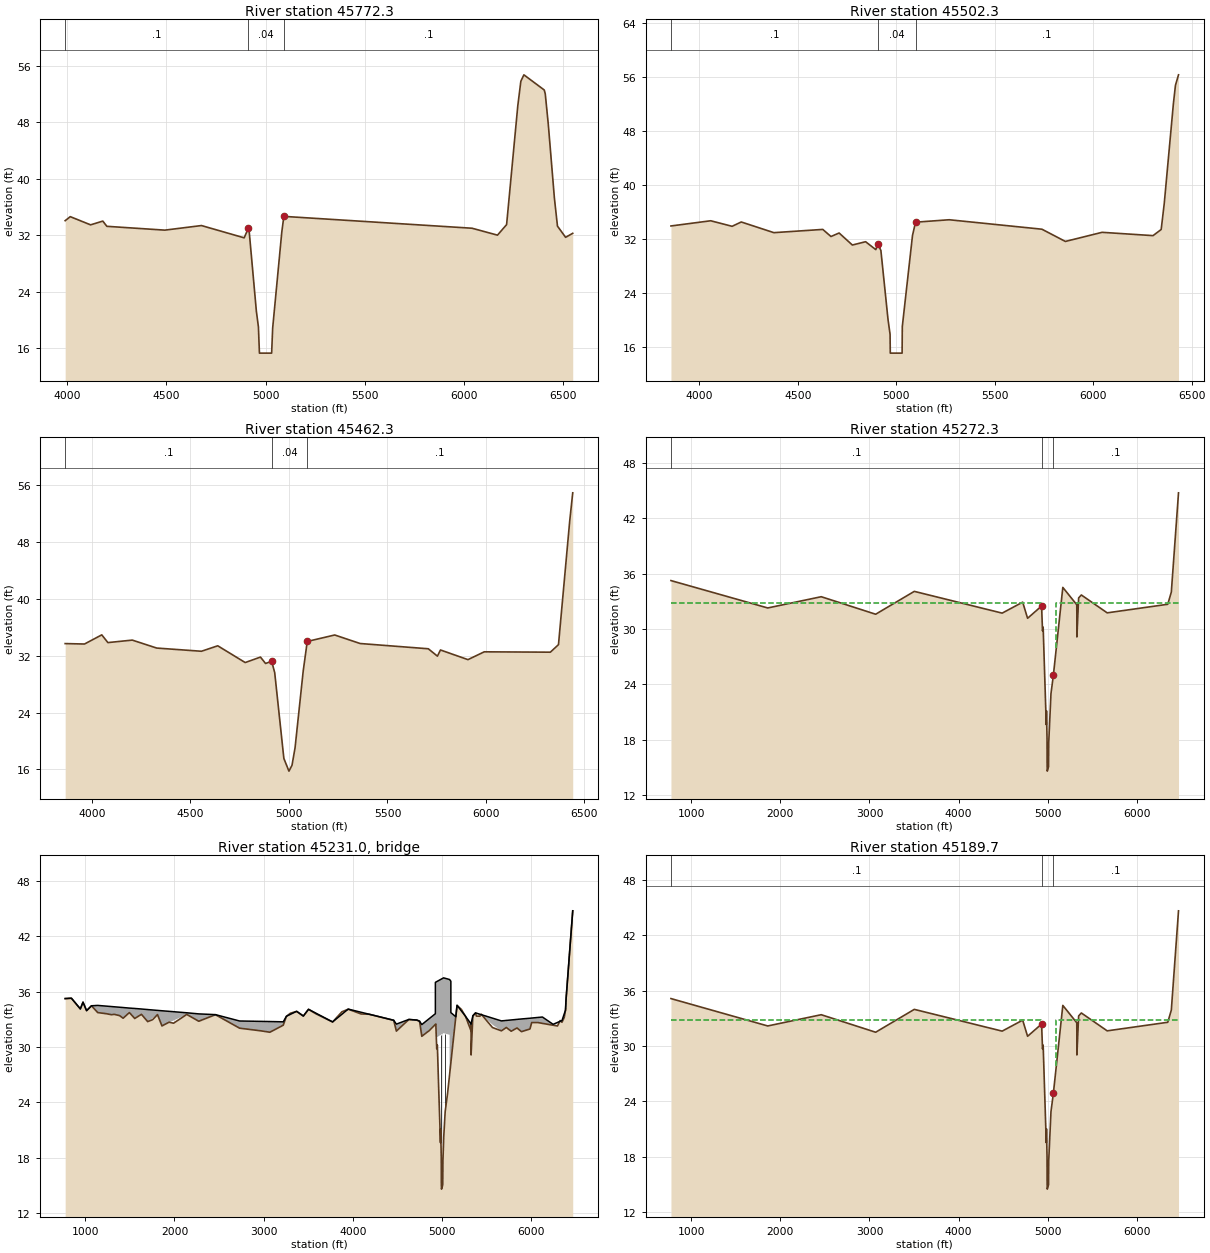
Type RM Length L Ch R = 1 ,45772.3 ,270,270,270
BEGIN DESCRIPTION:
Channel Improvments.
END DESCRIPTION:
XS GIS Cut Line= 6
       3186957.8     13863042.95     3186704.282     13862988.27
     3186353.529     13862650.57     3185805.378     13862197.87
     3185091.914     13861972.84     3184741.074     13861988.74
#Sta/Elev= 30
 3990.92   34.04 4016.54   34.61    4119   33.45 4180.48   33.98 4200.97   33.24
 4492.81    32.7 4677.25   33.35 4892.42   31.61 4912.91   32.94 4918.03    32.4
  4953.9   21.19 4964.14   18.99 4969.26   15.27 5030.74   15.27 5035.87   18.81
 5081.98   32.46 5092.22   34.65 6039.92   32.97    6168   31.99 6214.03   33.48
 6270.39   50.33 6285.76    53.8 6301.13   54.71 6403.59   52.56 6408.71   52.02
 6424.08   47.67 6454.82   37.21 6470.19   33.27 6511.18   31.68 6547.04   32.25
#Mann= 3 , 0 , 0
 3990.92      .1       0 4912.91     .04       0 5092.22      .1       0
Bank Sta=4912.91,5092.22
XS Rating Curve= 0
Exp/Cntr=.3,.1

Type RM Length L Ch R = 1 ,45502.3 ,40,40,40
BEGIN DESCRIPTION:
Channel Improvments.
END DESCRIPTION:
XS GIS Cut Line= 6
      3187256.05     13862871.45     3186913.062     13862801.86
     3186537.265     13862450.84      3186065.04     13862053.69
     3185348.062     13861832.92     3184997.222     13861848.81
#Sta/Elev= 30
 3856.34   33.91 4058.19   34.68 4166.89   33.86 4213.28    34.5 4378.91   32.92
 4627.34    33.4 4668.75   32.35 4710.16   32.87 4777.44   31.09 4844.73   31.58
 4896.48   30.41 4906.84   31.26 4922.36   30.28 4958.59   20.05 4968.94   17.88
    4970   15.09    5030   15.09 5031.05   19.02 5082.81    32.5 5098.34   34.47
 5269.14   34.83 5740.06   33.43  5859.1   31.62 6045.43   32.97 6304.18   32.48
 6345.59   33.39 6361.11   37.23  6407.7   52.05 6418.05   54.73 6433.57   56.28
#Mann= 3 , 0 , 0
 3856.34      .1       0 4906.84     .04       0 5098.34      .1       0
Bank Sta=4906.84,5098.34
XS Rating Curve= 0
Exp/Cntr=.3,.1

Type RM Length L Ch R = 1 ,45462.3 ,190,190,190
BEGIN DESCRIPTION:
Begin Channel Improvments.
END DESCRIPTION:
XS GIS Cut Line= 6
      3187268.48     13862851.57     3186940.403     13862781.98
     3186558.916     13862424.63     3186086.691     13862027.47
     3185369.713      13861806.7     3185018.873      13861822.6
#Sta/Elev= 30
 3864.07   33.73 3962.18   33.67 4049.96   34.96 4080.94   33.87 4204.83   34.22
 4328.75    33.1 4555.94   32.65 4638.56   33.42 4777.97   31.06 4855.43   31.83
 4881.24   30.93 4912.22   31.24 4927.71   29.64 4974.19   17.56    5000   15.77
 5015.49   16.59 5030.98   19.04 5072.29   29.84 5092.95   34.03 5232.36   34.94
 5361.35   33.74 5707.31      33 5753.78   31.96 5769.27   32.83 5908.68   31.47
  5991.3   32.57 6326.92   32.52 6368.23   33.58 6425.03   50.94 6440.52   54.96
#Mann= 3 , 0 , 0
 3864.07      .1       0 4912.22     .04       0 5092.95      .1       0
Bank Sta=4912.22,5092.95
XS Rating Curve= 0
Exp/Cntr=.3,.1

Type RM Length L Ch R = 1 ,45272.3 ,82.6,82.6,82.6
BEGIN DESCRIPTION:
Upstream Section of Bridge/Culvert/Weir
END DESCRIPTION:
XS GIS Cut Line= 6
      3190317.25     13863748.17      3189139.11     13863226.54
      3188706.26     13862927.67      3186849.72     13862218.71
      3185376.15     13861744.32      3185037.11     13861770.47
#Sta/Elev= 30
   774.5   35.25  1859.5   32.28  2459.2    33.5  3069.4    31.6  3502.4   34.08
  4487.4   31.72  4717.4   32.91  4772.4   31.16  4929.5   32.49  4939.8    29.8
    4947    30.2  4981.8   19.62  4984.2   21.12  4990.6   18.06  4991.6   15.19
  4993.2   14.58  5007.3   15.07  5009.3   17.63  5034.6   22.99  5061.8      25
  5167.5   34.51  5323.8   32.63    5325   31.37  5325.1   29.14  5344.8   33.37
  5374.8   33.69  5664.8   31.75  6343.8   32.68  6383.8      34  6464.4   44.77
#Mann= 3 , 1 , 0
   774.5      .1       0  4929.5     .04       0  5061.8      .1       0
#XS Ineff= 2 , 0
       0    4925    32.8    5095       0    32.8
Permanent Ineff=
       F       F
Bank Sta=4929.5,5061.8
XS Rating Curve= 0
Exp/Cntr=.5,.3

Type RM Length L Ch R = 3 ,45231.0 ,,,
BEGIN DESCRIPTION:
WALLSVILLE ROAD
Structure ID: N00-30
END DESCRIPTION:
Bridge Culvert--1,0,-1,-1, 0
Deck Dist Width WeirC Skew NumUp NumDn MinLoCord MaxHiCord MaxSubmerge Is_Ogee
10,62.6,2.6,0, 60, 60, , , .95, 0, 1,1,,
   774.5   844.5   944.5   974.5  1014.5  1069.5  1139.5  1424.5  1494.5  1554.5
  1629.5  1699.5  1809.5  1859.5  2137.4  2272.4  2459.2  2729.4  3069.4  3219.4
  3254.4  3369.4  3444.4  3502.4  3772.4  3947.4  4457.4  4487.4  4627.4  4717.4
  4747.4  4772.4 4924.49  4924.6  4929.5 4935.11  5016.7 5083.99  5084.1  5098.3
 5098.41  5153.7  5167.5  5262.4  5323.3  5323.8    5325  5325.1  5344.8  5374.8
  5664.8  5889.8  5984.8  6004.8  6124.4  6244.4  6343.8  6383.8  6388.8  6464.4
   35.25   35.29   34.13   34.86   33.94   34.47   34.51   34.28   34.22   34.18
   34.12   34.06   33.97   33.93   33.71   33.59   33.51   32.82   32.76   32.73
   33.33   33.87   33.36   34.09   32.72   34.11    32.9   32.48   32.99   32.92
    32.8   32.43   33.61   37.01   37.04   37.07    37.5   37.32   37.32   37.13
   33.73   33.28   34.52   33.33   32.52   32.64   32.52   32.52   33.38    33.7
   32.83   33.04   33.12   33.14   33.25   32.46   32.87   34.01   35.07   44.77
   35.25   35.29   34.13   34.86   33.94   34.47   33.73   33.12   33.73   33.09
   33.54   32.75   33.51   32.28   33.53   32.79    33.5   32.04    31.6   32.36
   33.32   33.86   33.35   34.08   32.71    34.1   32.89   31.72   32.98   32.91
   32.79   31.16   32.44   32.44   32.49   31.02    31.5   31.32   27.01   28.28
   28.29   33.27   34.51   33.32   31.78   32.63   31.37   29.14   33.37   33.69
   31.75   31.66   31.95   32.65   32.56   32.36   32.68      34   35.06   44.77
   774.5   844.5   944.5   974.5  1014.5  1069.5  1139.5  1424.5  1494.5  1554.5
  1629.5  1699.5  1809.5  1859.5  2137.4  2272.4  2459.2  2729.4  3069.4  3219.4
  3254.4  3369.4  3444.4  3502.4  3772.4  3947.4  4457.4  4487.4  4627.4  4717.4
  4747.4  4772.4 4924.49  4924.6  4929.5 4935.11  5016.7 5083.99  5084.1  5098.3
 5098.41  5153.7  5167.5  5262.4  5323.3  5323.8    5325  5325.1  5344.8  5374.8
  5664.8  5889.8  5984.8  6004.8  6124.4  6244.4  6343.8  6383.8  6388.8  6464.4
   35.25   35.29   34.13   34.86   33.94   34.47   34.51   34.28   34.22   34.18
   34.12   34.06   33.97   33.93   33.71   33.59   33.51   32.82   32.76   32.73
   33.33   33.87   33.36   34.09   32.72   34.11    32.9   32.48   32.99   32.92
    32.8   32.43   33.61   37.01   37.04   37.07    37.5   37.32   37.32   37.13
   33.73   33.28   34.52   33.33   32.52   32.64   32.52   32.52   33.38    33.7
   32.83   33.04   33.12   33.14   33.25   32.46   32.87   34.01   35.07   44.77
   35.16    35.2   34.04   34.77   33.85   34.38   33.64   33.03   33.64      33
   33.45   32.66   33.42   32.19   33.44    32.7   33.41   31.95   31.51   32.27
   33.23   33.77   33.26   33.99   32.62   34.01    32.8   31.63   32.89   32.82
    32.7   31.07   32.35   32.35    32.4   30.93   31.41   31.23   26.92   28.19
    28.2   33.18   34.42   33.23   31.69   32.54   31.28   29.05   33.28    33.6
   31.66   31.57   31.86   32.56   32.47   32.27   32.59   33.91   34.97   44.68
Pier Skew, UpSta & Num, DnSta & Num=  ,4984.2, 2 ,4984.2, 2 , 0 , 0 , 0 ,,
     1.3     1.3
   19.71   32.33
     1.3     1.3
   19.62   32.24
Pier Skew, UpSta & Num, DnSta & Num=  ,5034.6, 2 ,5034.6, 2 , 0 , 0 , 0 ,,
     1.3     1.3
   21.88   32.45
     1.3     1.3
   21.79   32.36
Abutment Skew #Up #Dn= , 2 , 2
  5059.3 5084.19
   24.82   31.32
  5059.3 5084.19
   24.73   31.23
BR Coef= 1 , 1 , 0 ,1.25, 0 ,,,.8,0,2,0,
WSPro=,,,, 1 ,,,, 0 ,,,, 0 ,,,,-1 ,-1 ,-1 , 0 , 0 , 0 , 0 , 0
BR U #Sta/Elev= 125
   774.5   35.25   844.5   35.29   944.5   34.13   974.5   34.86  1014.5   33.94
  1069.5   34.47  1134.5   33.78  1139.5   33.73  1234.5   33.61  1294.5    33.5
  1324.5   33.54  1384.5    33.4  1424.5   33.12  1494.5   33.73  1554.5   33.09
  1629.5   33.54  1699.5   32.75  1754.5   32.96  1809.5   33.51  1859.5   32.28
  1939.5   32.69  1989.5   32.58  2062.9   33.05  2137.4   33.53  2272.4   32.79
  2374.5   33.18  2459.2    33.5    2589    32.8  2729.4   32.04  2969.4   31.75
  3069.4    31.6  3219.4   32.36  3254.4   33.32  3299.4   33.66  3369.4   33.86
  3444.4   33.35  3502.4   34.08  3587.4   33.59  3772.4   32.71  3877.4   33.82
  3947.4    34.1  4092.4   33.58  4182.4   33.55  4457.4   32.89  4487.4   31.72
  4576.3   32.52  4627.4   32.98  4717.4   32.91  4747.4   32.79  4772.4   31.16
  4779.2   31.21  4838.7   31.65  4854.3   31.76  4895.4   32.16 4924.49   32.44
  4924.6   32.44 4924.71   32.44  4929.5   32.49 4935.11   31.02  4935.2      31
  4935.8   30.84  4939.8    29.8    4947    30.2  4961.4   25.63  4981.8   19.62
  4984.2   21.12  4990.6   18.06  4991.6   15.19  4993.2   14.58  5003.7   14.91
  5007.3   15.07  5008.4   16.47  5009.3   17.63  5016.7   19.77  5018.3   20.23
  5034.6   22.99  5059.3   24.82  5061.8      25 5083.99      27  5084.1   27.01
  5084.2   27.02  5084.8   27.07 5098.19   28.27  5098.3   28.28 5098.41   28.29
  5153.7   33.27  5167.5   34.51  5216.4   34.07  5233.9   33.78  5262.4   33.32
  5305.4   32.23  5323.3   31.78  5323.8   32.63    5325   31.37  5325.1   29.14
  5344.8   33.37  5374.8   33.69  5384.8   33.35  5424.8   33.34  5439.8   33.55
  5564.8   32.11  5664.8   31.75  5719.8   32.11  5774.8   31.71  5839.8   32.06
  5889.8   31.66  5984.8   31.95  6004.8   32.65  6073.8   32.65  6124.4   32.56
  6244.4   32.36  6293.8   32.28  6323.8   32.87  6343.8   32.68  6368.8   33.19
  6383.8      34  6384.4   34.13  6388.8   35.06  6409.4   37.71  6414.4   38.35
  6419.4   38.99  6424.4   39.63  6434.4   40.92  6449.4   42.84  6464.4   44.77
BR U #Mann= 3
   774.5      .1  4929.5     .04  5061.8      .1
BR U Banks=4929.5,5061.8
BR D #Sta/Elev= 125
   774.5   35.16   844.5    35.2   944.5   34.04   974.5   34.77  1014.5   33.85
  1069.5   34.38  1134.5   33.69  1139.5   33.64  1234.5   33.52  1294.5   33.41
  1324.5   33.45  1384.5   33.31  1424.5   33.03  1494.5   33.64  1554.5      33
  1629.5   33.45  1699.5   32.66  1754.5   32.87  1809.5   33.42  1859.5   32.19
  1939.5    32.6  1989.5   32.49  2062.9   32.96  2137.4   33.44  2272.4    32.7
  2374.5   33.09  2459.2   33.41    2589   32.71  2729.4   31.95  2969.4   31.66
  3069.4   31.51  3219.4   32.27  3254.4   33.23  3299.4   33.57  3369.4   33.77
  3444.4   33.26  3502.4   33.99  3587.4    33.5  3772.4   32.62  3877.4   33.73
  3947.4   34.01  4092.4   33.49  4182.4   33.46  4457.4    32.8  4487.4   31.63
  4576.3   32.43  4627.4   32.89  4717.4   32.82  4747.4    32.7  4772.4   31.07
  4779.2   31.12  4838.7   31.56  4854.3   31.67  4895.4   32.07 4924.49   32.35
  4924.6   32.35 4924.71   32.35  4929.5    32.4 4935.11   30.93  4935.2   30.91
  4935.8   30.75  4939.8   29.71    4947   30.11  4961.4   25.54  4981.8   19.53
  4984.2   21.03  4990.6   17.97  4991.6    15.1  4993.2   14.49  5003.7   14.82
  5007.3   14.98  5008.4   16.38  5009.3   17.54  5016.7   19.68  5018.3   20.14
  5034.6    22.9  5059.3   24.73  5061.8   24.91 5083.99   26.91  5084.1   26.92
  5084.2   26.93  5084.8   26.98 5098.19   28.18  5098.3   28.19 5098.41    28.2
  5153.7   33.18  5167.5   34.42  5216.4   33.98  5233.9   33.69  5262.4   33.23
  5305.4   32.14  5323.3   31.69  5323.8   32.54    5325   31.28  5325.1   29.05
  5344.8   33.28  5374.8    33.6  5384.8   33.26  5424.8   33.25  5439.8   33.46
  5564.8   32.02  5664.8   31.66  5719.8   32.02  5774.8   31.62  5839.8   31.97
  5889.8   31.57  5984.8   31.86  6004.8   32.56  6073.8   32.56  6124.4   32.47
  6244.4   32.27  6293.8   32.19  6323.8   32.78  6343.8   32.59  6368.8    33.1
  6383.8   33.91  6384.4   34.04  6388.8   34.97  6409.4   37.62  6414.4   38.26
  6419.4    38.9  6424.4   39.54  6434.4   40.83  6449.4   42.75  6464.4   44.68
BR D #Mann= 3
   774.5      .1  4929.5     .04  5061.8      .1
BR D Banks=4929.5,5061.8
BC Design=,, 0 ,, 0 ,,,,,,
BC HTab HWMax=44.77

Type RM Length L Ch R = 1 ,45189.7 ,594.9,594.9,594.9
BEGIN DESCRIPTION:
Downstream Section of Bridge/Culvert/Weir
END DESCRIPTION:
XS GIS Cut Line= 6
      3190323.22     13863665.78      3189145.07     13863144.16
      3188712.22     13862845.29      3186855.68     13862136.33
      3185382.11     13861661.94      3185043.08     13861688.09
#Sta/Elev= 30
   774.5   35.14  1859.5   32.17  2459.2   33.39  3069.4   31.49  3502.4   33.97
  4487.4   31.61  4717.4    32.8  4772.4   31.05  4929.5   32.38  4939.8   29.69
    4947   30.09  4981.8   19.51  4984.2   21.01  4990.6   17.95  4991.6   15.08
  4993.2   14.47  5007.3   14.96  5009.3   17.52  5034.6   22.88  5061.8   24.89
  5167.5    34.4  5323.8   32.52    5325   31.26  5325.1   29.03  5344.8   33.26
  5374.8   33.58  5664.8   31.64  6343.8   32.57  6383.8   33.89  6464.4   44.66
#Mann= 3 , 1 , 0
   774.5      .1       0  4929.5     .04       0  5061.8      .1       0
#XS Ineff= 2 , 0
       0    4925    32.8    5095       0    32.8
Permanent Ineff=
       F       F
Bank Sta=4929.5,5061.8
XS Rating Curve= 0
Exp/Cntr=.5,.3