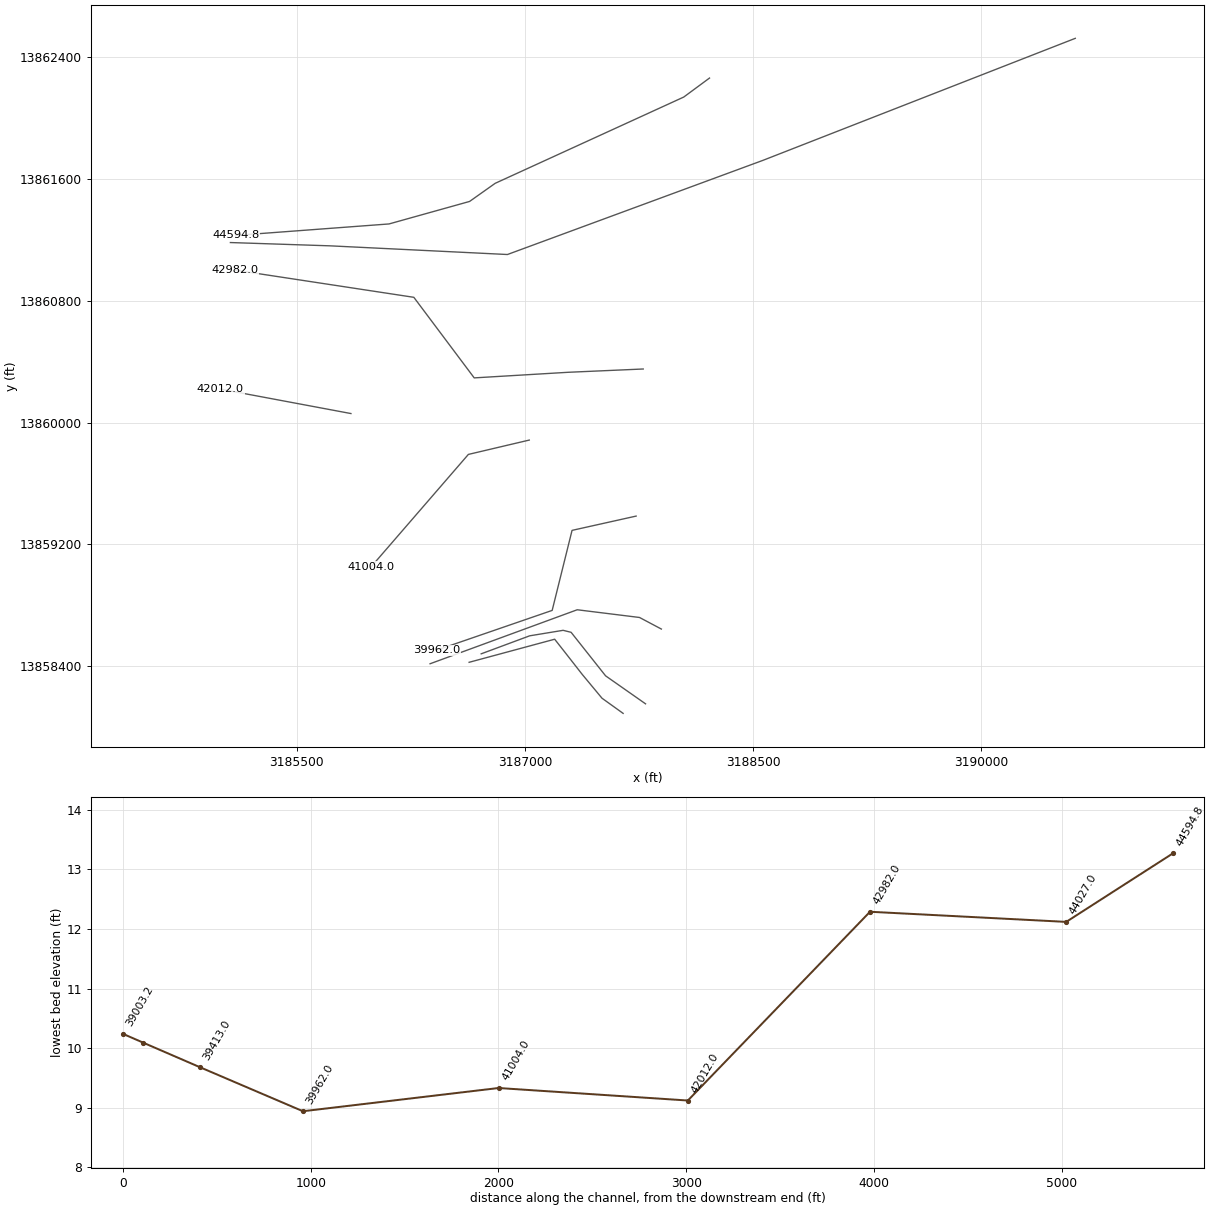
HEC-RAS study N100-00-00.prj: N100-00-00

--- N100-00-00.g01 (geometry) --- (continued)

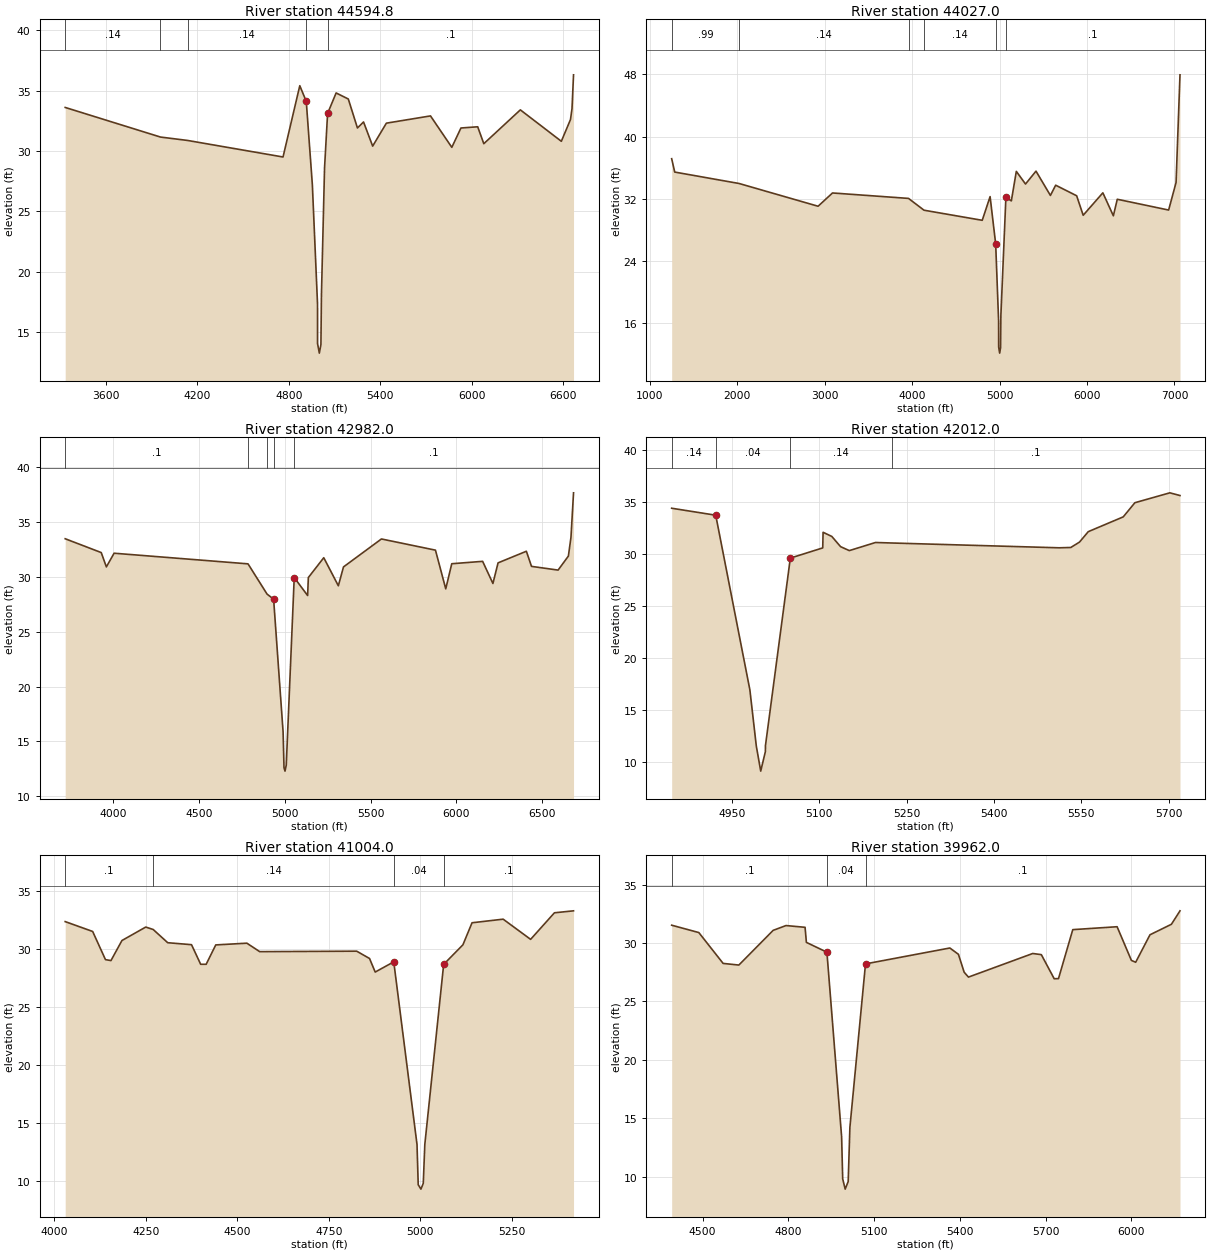
Type RM Length L Ch R = 1 ,44594.8 ,512.2,567.8,496.5
BEGIN DESCRIPTION:
Cross Section 44594.8 - Interpolated
END DESCRIPTION:
XS GIS Cut Line= 6
       3188213.3     13862262.08      3188044.03     13862137.29
      3186804.69     13861570.97      3186636.44     13861451.96
      3186107.05     13861304.23      3185100.72     13861229.08
#Sta/Elev= 30
  3332.1    33.6  3957.8   31.15  4135.4   30.87  4762.4    29.5  4872.4    35.4
    4915    34.1    4955    27.2  4988.8   17.36  4989.2   14.05  5000.9   13.27
  5011.2   13.98  5014.6    18.1    5035    28.6    5055    33.1    5111    34.8
    5191    34.3    5251    31.9    5291    32.4    5351    30.4    5441    32.3
  5730.7    32.9  5870.7    30.3  5930.7    31.9  6040.7      32  6080.7    30.6
  6320.7    33.4  6589.9    30.8  6649.9    32.6  6659.9    33.5  6669.9    36.3
#Mann= 5 , 1 , 0
  3332.1     .14       0  3957.8     .06       0  4135.4     .14       0
    4915     .04       0    5055      .1       0
Bank Sta=4915,5055
XS Rating Curve= 0
Exp/Cntr=.3,.1

Type RM Length L Ch R = 1 ,44027.0 ,1420.7,1045,809.3
BEGIN DESCRIPTION:
Cross Section 44027
Located At: 1ST XS DS WALLISVILLE
END DESCRIPTION:
XS GIS Cut Line= 5
      3190617.14     13862522.75      3188564.96      13861721.9
      3186885.08     13861103.54      3185719.05     13861160.52
      3185064.41      13861182.1
#Sta/Elev= 30
  1248.4   37.15  1283.4   35.43  2019.6   33.96  2923.4   31.03  3088.4   32.74
  3957.8   32.04  4135.4   30.52  4801.3   29.22  4891.3   32.27  4955.2   26.18
  4988.8   16.21  4989.2    12.9  5000.9   12.12  5011.2   12.83  5014.6   16.95
  5072.1   32.18  5134.3   31.72  5191.3   35.52  5296.4   33.89  5416.4   35.55
  5581.4   32.42  5641.4   33.74  5881.4   32.38  5956.4   29.87  6181.4   32.76
  6301.4    29.8  6346.4   31.93  6933.8   30.54  7018.8   34.09  7063.8   47.95
#Mann= 6 , 1 , 0
  1248.4     .99       0  2019.6     .14       0  3957.8     .06       0
  4135.4     .14       0  4955.2     .04       0  5072.1      .1       0
Bank Sta=4955.2,5072.1
XS Rating Curve= 0
Exp/Cntr=.3,.1

Type RM Length L Ch R = 1 ,42982.0 ,385.1,970,1074.6
BEGIN DESCRIPTION:
Cross Section 42982
Located At: 2ND XS DS WALLISVILLE
END DESCRIPTION:
XS GIS Cut Line= 5
      3187777.69     13860351.99      3187283.94     13860330.32
       3186666.8     13860293.59      3186270.07     13860822.56
      3185093.57     13861001.44
#Sta/Elev= 30
  3719.5   33.49  3929.5   32.23  3959.5   30.92  4004.5   32.17  4785.4    31.2
  4896.4   28.44  4934.6   27.98  4989.9   15.86  4995.2   12.59    5001   12.29
  5008.3   12.83  5054.8   29.95  5132.9   28.31    5137   29.95    5227   31.76
    5312    29.2    5342   30.92  5563.2   33.47  5878.2   32.45  5938.2   28.92
  5973.2   31.21  6153.2   31.43  6213.2   29.41  6243.2   31.29  6408.2   32.35
  6438.2   30.97  6593.2   30.63  6653.2   31.91  6668.2   33.61  6683.2   37.68
#Mann= 5 , 1 , 0
  3719.5      .1       0  4785.4     .14       0  4896.4     .07       0
  4934.6     .04       0  5054.8      .1       0
Bank Sta=4934.6,5054.8
XS Rating Curve= 0
Exp/Cntr=.3,.1

Type RM Length L Ch R = 1 ,42012.0 ,386.3,1008,1068
BEGIN DESCRIPTION:
Cross Section 42012
Located At: AT S END EVASHAM
END DESCRIPTION:
XS GIS Cut Line= 2
      3185856.64     13860059.47      3184999.29     13860219.91
#Sta/Elev= 23
    4847   34.37  4922.6    33.7  4981.2   16.92  4992.2   11.54  4999.8    9.12
  5007.8      11  5007.9   11.56  5050.6   29.58  5106.2   30.56  5106.8   32.06
  5121.8   31.66  5136.8   30.68  5151.8    30.3  5196.8   31.08  5225.4   31.03
  5511.8   30.57  5531.8    30.6  5546.8   31.12  5561.8   32.12  5621.8   33.54
  5641.8    34.9  5701.8   35.85  5719.2   35.59
#Mann= 4 , 1 , 0
    4847     .14       0  4922.6     .04       0  5050.6     .14       0
  5225.4      .1       0
Bank Sta=4922.6,5050.6
XS Rating Curve= 0
Exp/Cntr=.3,.1

Type RM Length L Ch R = 1 ,41004.0 ,921.2,1042,1088.9
BEGIN DESCRIPTION:
Cross Section 41004
Located At: OAKENGATES AT CROXTON
END DESCRIPTION:
XS GIS Cut Line= 3
      3187028.71     13859885.36      3186628.46     13859791.18
       3185988.7     13859052.49
#Sta/Elev= 30
  4030.3    32.4  4105.3   31.55  4140.3   29.12  4155.3   29.04  4185.3   30.77
  4250.3   31.93  4270.6   31.72  4310.3   30.58  4375.3   30.41  4400.3   28.72
  4415.3   28.72  4441.5   30.39  4526.5   30.54  4561.5   29.81  4826.5   29.85
  4861.5   29.22    4877   28.05  4927.7   28.93  4991.2   13.18  4994.5    9.71
  5001.9    9.33  5008.3    9.83  5012.5   13.18    5064   28.71  5116.6    30.4
  5141.5    32.3  5226.5   32.61  5301.5   30.87  5366.5   33.16  5418.7   33.33
#Mann= 4 , 1 , 0
  4030.3      .1       0  4270.6     .14       0  4927.7     .04       0
    5064      .1       0
Bank Sta=4927.7,5064
XS Rating Curve= 0
Exp/Cntr=.3,.1

Type RM Length L Ch R = 1 ,39962.0 ,659.7,549,376.4
BEGIN DESCRIPTION:
Cross Section 39962
Located At: AT SOUTH SILVERGREEN
END DESCRIPTION:
XS GIS Cut Line= 4
      3187731.06     13859386.33      3187309.87     13859292.53
      3187179.21     13858767.11      3186417.91     13858505.28
#Sta/Elev= 30
    4392   31.52    4487   30.89    4572   28.25    4627   28.11    4747   31.08
    4792   31.49  4858.6   31.34  4863.2   30.05    4935   29.21  4986.4   13.42
  4990.2    9.82  4998.9    8.94  5009.4    9.59  5015.4   14.23    5070   28.21
    5365   29.57    5395   29.03    5415    27.5    5430   27.08    5655    29.1
    5685      29    5730   26.94    5745   26.95    5795   31.14    5950   31.39
    6000   28.51    6015   28.35    6065    30.7    6140    31.6    6170   32.75
#Mann= 3 , 1 , 0
    4392      .1       0    4935     .04       0    5070      .1       0
#XS Ineff= 2 , 0
       0    4792   31.49    5365       0   29.57
Permanent Ineff=
       F       F
Bank Sta=4935,5070
XS Rating Curve= 0
Exp/Cntr=.3,.1

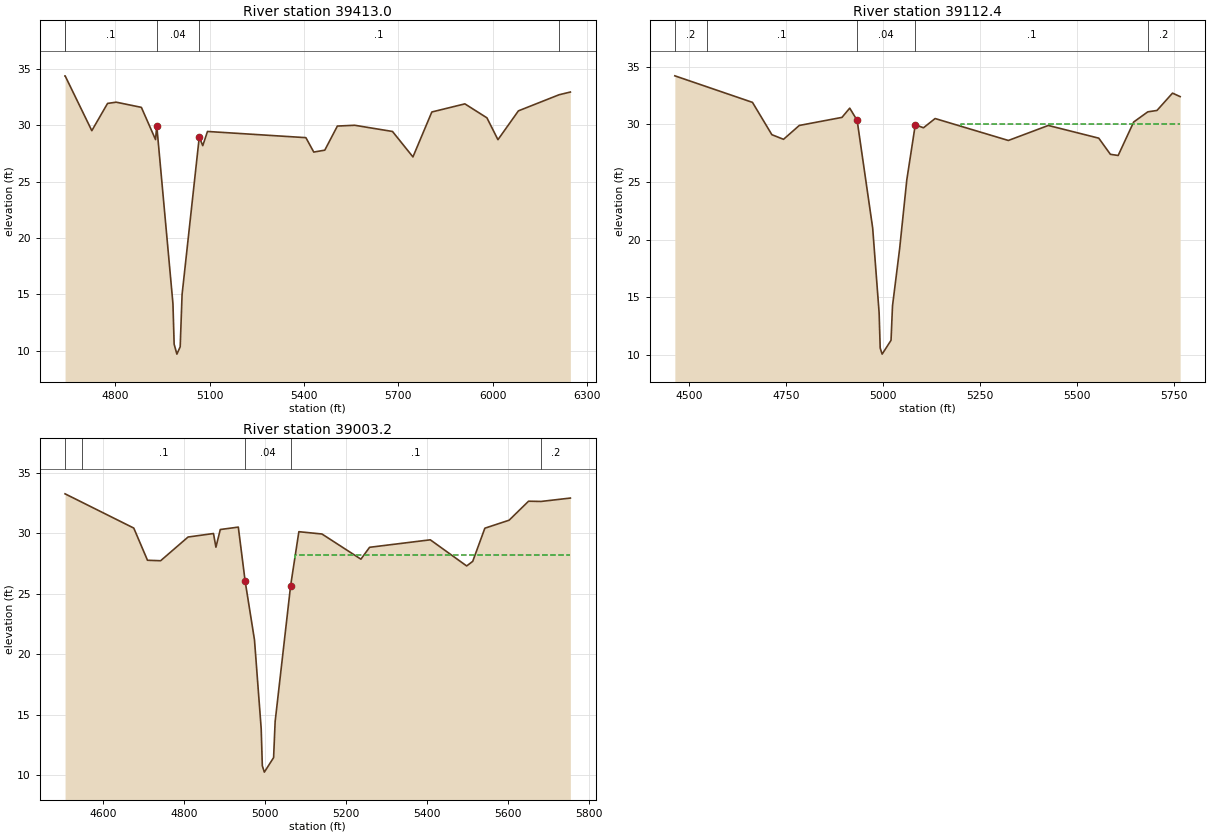
Type RM Length L Ch R = 1 ,39413.0 ,369,300.6,229.4
BEGIN DESCRIPTION:
Cross Section 39413-Interpolated
END DESCRIPTION:
XS GIS Cut Line= 4
      3187896.84     13858644.69      3187753.31     13858720.67
      3187343.84     13858771.33      3186376.72     13858416.86
#Sta/Elev= 30
  4641.2   34.39  4641.4   34.39  4726.2   29.52  4776.2   31.94  4803.6   32.05
  4883.6   31.59  4928.6   28.73  4932.5   29.95  4983.9   14.16  4987.7   10.56
  4996.4    9.68  5006.9   10.33  5012.9   14.97  5067.5   28.95  5078.6   28.19
  5093.6   29.45  5406.2    28.9  5431.2   27.62  5466.2   27.79  5506.2   29.93
  5561.2      30  5681.2   29.45  5746.2   27.19  5806.2   31.18  5911.2    31.9
  5981.2   30.66  6016.2   28.72  6081.2   31.28  6210.4   32.71  6246.2   32.95
#Mann= 5 , 1 , 0
  4641.2      .2       0  4641.4      .1       0  4932.5     .04       0
  5067.5      .1       0  6210.4      .2       0
#XS Ineff= 2 , 0
       0                  5093.6       0   29.45
Permanent Ineff=
       F       F
Bank Sta=4932.5,5067.5
XS Rating Curve= 0
Exp/Cntr=.3,.1

Type RM Length L Ch R = 1 ,39112.4 ,113.7,109.2,108.2
BEGIN DESCRIPTION:
Cross Section 39112.4 - Interpolated
END DESCRIPTION:
XS GIS Cut Line= 6
      3187792.88     13858153.77      3187530.24     13858337.61
      3187303.71     13858623.24      3187251.18     13858636.37
      3187031.22     13858600.25      3186712.77     13858482.07
#Sta/Elev= 30
    4464    34.2  4546.6   33.25    4664    31.9    4714    29.1    4744    28.7
  4784.6    29.9  4894.6    30.6  4914.6    31.4  4933.7   30.34  4973.7   21.02
  4990.3   13.68  4993.1   10.61  4998.1   10.09    5021   11.29  5024.8   14.27
  5043.2   19.23  5061.6   25.18  5083.5   29.96  5104.6    29.7  5134.6    30.5
  5323.3    28.6  5426.2    29.9  5556.2    28.8  5586.2    27.4  5606.2    27.3
  5646.2    30.2  5682.6   31.08  5706.2    31.2  5746.2    32.7  5765.9    32.4
#Mann= 5 , 1 , 0
    4464      .2       0  4546.6      .1       0  4933.7     .04       0
  5083.5      .1       0  5682.6      .2       0
#XS Ineff= 2 , 0
       0                    5200       0      30
Permanent Ineff=
       F       F
Bank Sta=4933.7,5083.5
XS Rating Curve= 0
Exp/Cntr=.5,.3

Type RM Length L Ch R = 1 ,39003.2 ,68.4,68.4,68.4
BEGIN DESCRIPTION:
Upstream Section of Bridge/Culvert/Weir
END DESCRIPTION:
XS GIS Cut Line= 6
      3187645.52     13858091.11      3187506.82     13858190.51
      3187377.01     13858346.63      3187270.01     13858483.46
      3187195.62     13858577.95      3186633.33     13858426.38
#Sta/Elev= 30
  4505.1   33.24  4546.6   32.55  4675.1   30.41    4709   27.75  4741.5   27.71
  4809.4   29.67  4872.3   29.96  4878.3   28.83  4889.1   30.29  4933.7   30.49
  4950.6   26.02  4973.7   21.17  4990.3   13.83  4993.1   10.76  4998.1   10.24
    5021   11.44  5024.8   14.42  5063.1   25.65  5083.5   30.11  5140.6   29.92
    5237   27.84  5258.4   28.82  5408.6   29.44  5498.6   27.28  5513.6   27.66
  5543.6    30.4  5603.6   31.06  5651.7   32.63  5682.6   32.61  5755.1   32.89
#Mann= 5 , 1 , 0
  4505.1      .2       0  4546.6      .1       0  4950.6     .04       0
  5063.1      .1       0  5682.6      .2       0
#XS Ineff= 2 , 0
       0    4941    28.5    5073       0    28.2
Permanent Ineff=
       F       F
Bank Sta=4950.6,5063.1
XS Rating Curve= 0
Exp/Cntr=.5,.3