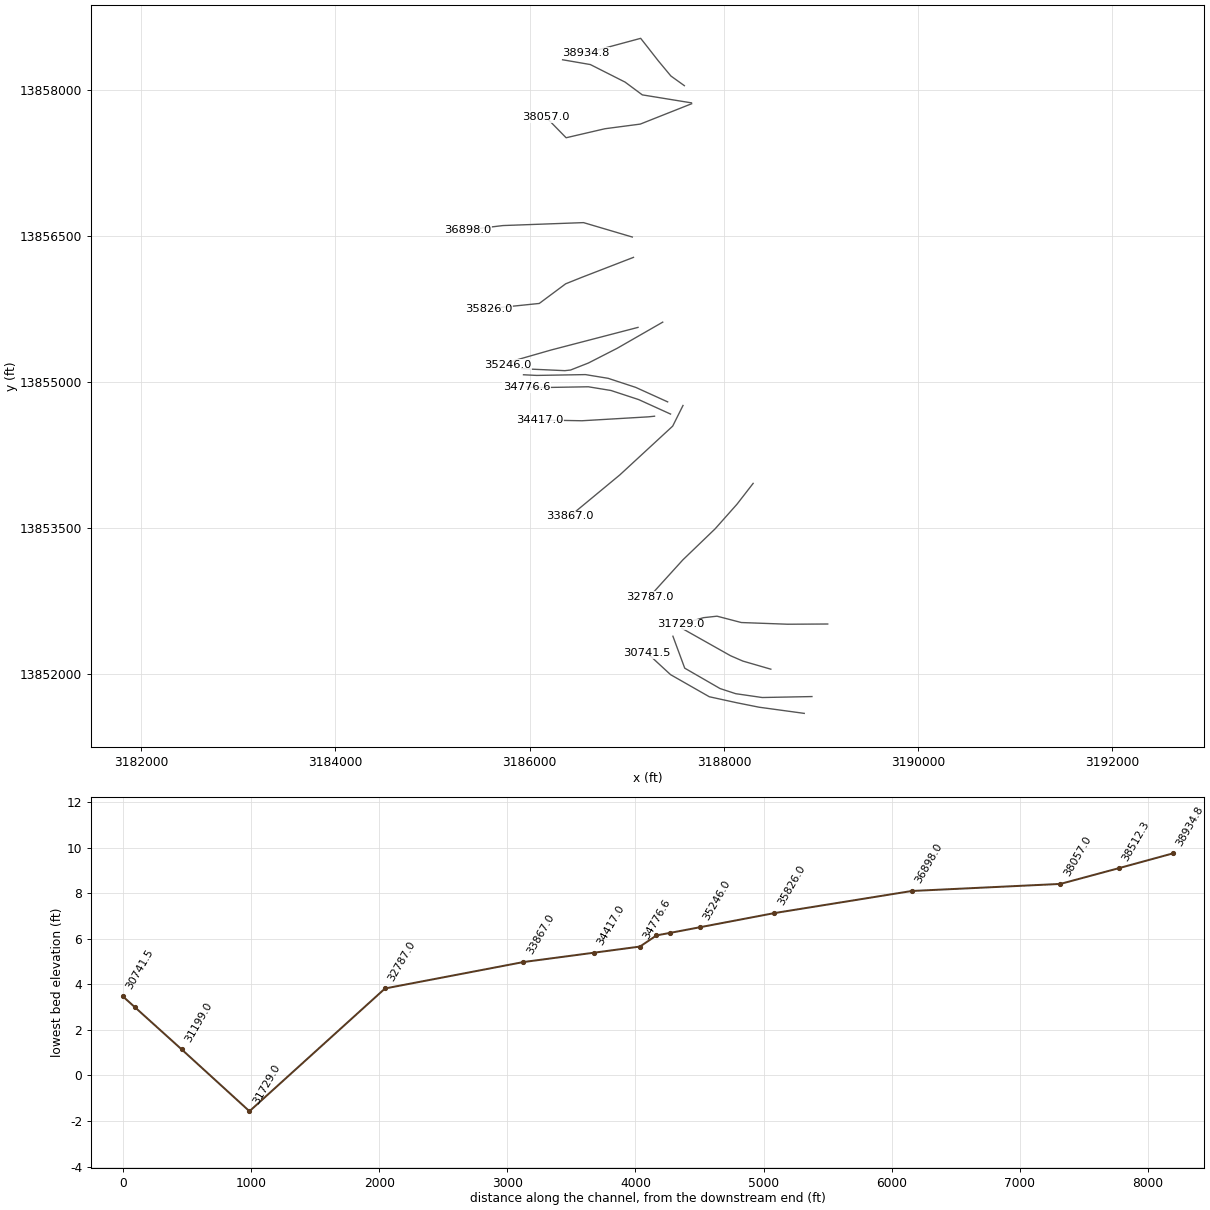
HEC-RAS study N100-00-00.prj: N100-00-00

--- N100-00-00.g01 (geometry) --- (continued)

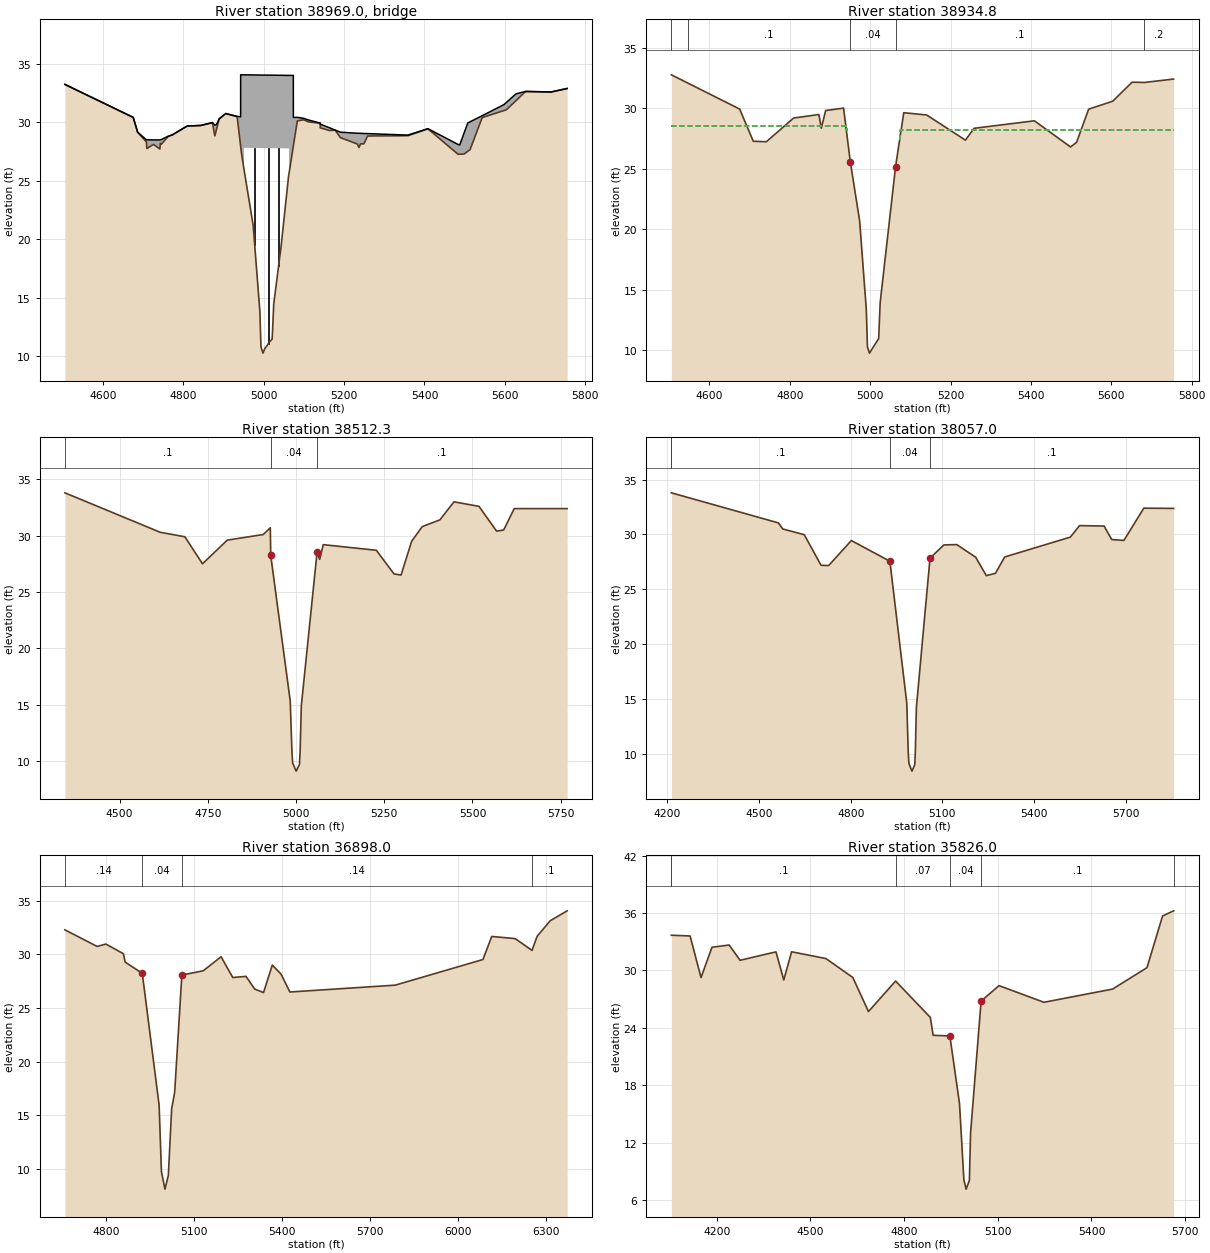
Type RM Length L Ch R = 3 ,38969.0 ,,,
BEGIN DESCRIPTION:
SILVER GREEN DRIVE, SKEW ANGLE OF 31 DEGREES
Structure ID: N00-28
END DESCRIPTION:
Bridge Culvert--1,0,-1,-1, 0
Deck Dist Width WeirC Skew NumUp NumDn MinLoCord MaxHiCord MaxSubmerge Is_Ogee
10,48.4,2.6,0, 55, 55, , , .95, 0, 1,1,,
  4505.1  4675.1  4686.2  4707.9    4709  4725.6  4741.5  4742.5  4744.8  4762.7
  4772.1  4809.4  4843.1  4872.3  4878.3  4882.4  4889.1  4905.5  4933.7 4942.39
  4942.5  4944.6 4950.72 4950.81 5063.05  5063.1  5073.6 5073.71  5083.5  5099.1
  5111.8  5140.6  5140.7  5164.1  5177.6  5190.9  5232.9    5237  5241.1  5249.4
  5258.4  5358.6  5408.6  5483.6  5487.8  5498.6  5507.8  5513.6  5543.6  5597.8
  5603.6  5627.8  5651.7  5715.2  5755.1
   33.25   30.43   29.16   28.51   28.51    28.5    28.5   28.51   28.53   28.82
   28.93   29.69   29.74   29.98   29.76   29.82   30.31   30.76   30.51   30.47
   34.07   34.07   34.07   34.07   34.02   34.02   34.02   30.42   30.43   30.35
    30.2   29.94   29.85   29.53   29.34   29.16   29.07   29.07   29.06   29.05
   29.04   28.91   29.46   28.11   28.07   29.09   29.95   30.05   30.57   31.52
    31.7   32.44   32.65    32.6    32.9
   33.25   30.42   29.15   28.33   27.76   28.11   27.72    28.2   28.12   28.81
   28.92   29.68   29.73   29.97   28.84    29.4    30.3   30.75    30.5   27.99
   27.96   27.35      26   27.82   27.77   25.66   27.96   27.98   30.12   30.22
   30.04   29.93   29.53    29.3   29.34   28.69   28.15   27.85   28.16   28.16
   28.83   28.86   29.45   27.27   27.28   27.29   27.52   27.67   30.41   31.01
   31.07   31.86   32.64    32.6    32.9
  4505.1  4675.1  4686.2  4707.9    4709  4725.6  4741.5  4742.5  4744.8  4762.7
  4772.1  4809.4  4843.1  4872.3  4878.3  4882.4  4889.1  4905.5  4933.7 4942.39
  4942.5  4944.6 4950.72 4950.81 5063.05  5063.1  5073.6 5073.71  5083.5  5099.1
  5111.8  5140.6  5140.7  5164.1  5177.6  5190.9  5232.9    5237  5241.1  5249.4
  5258.4  5358.6  5408.6  5483.6  5487.8  5498.6  5507.8  5513.6  5543.6  5597.8
  5603.6  5627.8  5651.7  5715.2  5755.1
   33.25   30.43   29.16   28.51   28.51    28.5    28.5   28.51   28.53   28.82
   28.93   29.69   29.74   29.98   29.76   29.82   30.31   30.76   30.51   30.47
   34.07   34.07   34.07   34.07   34.02   34.02   34.02   30.42   30.43   30.35
    30.2   29.94   29.85   29.53   29.34   29.16   29.07   29.07   29.06   29.05
   29.04   28.91   29.46   28.11   28.07   29.09   29.95   30.05   30.57   31.52
    31.7   32.44   32.65    32.6    32.9
   32.77   29.94   28.67   27.85   27.28   27.63   27.24   27.72   27.64   28.33
   28.44    29.2   29.25   29.49   28.36   28.92   29.82   30.27   30.02   27.51
   27.48   26.87   25.52   27.34   27.29   25.18   27.48    27.5   29.64   29.74
   29.56   29.45   29.05   28.82   28.86   28.21   27.67   27.37   27.68   27.68
   28.35   28.38   28.97   26.79    26.8   26.81   27.04   27.19   29.93   30.53
   30.59   31.38   32.16   32.12   32.42
Pier Skew, UpSta & Num, DnSta & Num=  ,4977.5, 2 ,4977.5, 2 , 0 , 0 , 0 ,,
     1.3     1.3
   18.23   28.81
     1.3     1.3
   17.75   28.33
Pier Skew, UpSta & Num, DnSta & Num=  ,5011.2, 2 ,5011.2, 2 , 0 , 0 , 0 ,,
     1.3     1.3
   10.03   28.79
     1.3     1.3
    9.55   28.31
Pier Skew, UpSta & Num, DnSta & Num=  ,5037, 2 ,5037, 2 , 0 , 0 , 0 ,,
     1.3     1.3
   16.55   28.78
     1.3     1.3
   16.07    28.3
Abutment Skew #Up #Dn= , 2 , 2
 4950.61 4991.69
   27.82   12.32
 4950.61 4991.69
   27.34   11.84
Abutment Skew #Up #Dn= , 2 , 2
    5021 5063.25
   11.45   27.77
    5021 5063.25
   10.97   27.29
BR Coef= 1 , 1 , 0 ,1.25, 0 ,,,.8,-1,2,0,
WSPro=,,,, 1 ,,,, 0 ,,,, 0 ,,,,-1 ,-1 ,-1 , 0 , 0 , 0 , 0 , 0
BR U #Sta/Elev= 93
  4505.1   33.25  4546.3   32.56  4546.6   32.56  4601.3   31.65  4675.1   30.42
  4675.8   30.34  4681.6   29.68  4686.2   29.15  4707.9   28.33    4709   27.76
  4725.6   28.11    4741   27.73  4741.5   27.72  4742.5    28.2  4744.8   28.12
  4762.7   28.81  4772.1   28.92  4809.4   29.68  4812.8   29.69  4843.1   29.73
  4864.7   29.91    4872   29.97  4872.3   29.97  4878.3   28.84  4882.4    29.4
  4889.1    30.3  4905.5   30.75  4923.2   30.59  4933.7    30.5 4942.39   27.99
  4942.5   27.96 4942.61   27.93  4944.6   27.35  4950.6   26.03 4950.72      26
 4950.81   25.99  4973.7   21.18  4990.3   13.84 4991.69   12.32  4993.1   10.77
  4998.1   10.25  5002.9   10.67  5006.8   10.81  5013.1   11.17  5020.9   11.45
    5021   11.45  5024.5   14.16  5024.8   14.43  5043.2   19.39  5061.6   25.34
 5063.05   25.65  5063.1   25.66 5063.16   25.67 5073.49   27.93  5073.6   27.96
 5073.71   27.98  5083.5   30.12  5092.7   30.18  5099.1   30.22  5111.8   30.04
  5140.6   29.93  5140.7   29.53  5148.1   29.46  5164.1    29.3  5177.6   29.34
  5190.9   28.69  5193.5   28.66  5232.9   28.15    5237   27.85  5241.1   28.16
  5249.4   28.16  5258.4   28.83  5277.2   28.84  5337.8   28.85  5358.6   28.86
  5383.6   29.15  5408.6   29.45  5412.8   29.33  5483.6   27.27  5487.8   27.28
  5498.6   27.29  5507.8   27.52  5513.6   27.67  5543.6   30.41  5597.8   31.01
  5603.6   31.07  5627.8   31.86  5651.7   32.64  5682.6   32.62  5682.8   32.62
  5682.9   32.62  5715.2    32.6  5755.1    32.9
BR U #Mann= 5
  4505.1      .2  4546.6      .1  4950.6     .04  5063.1      .1  5682.6      .2
BR U Banks=4950.6,5063.1
BR D #Sta/Elev= 93
  4505.1   32.77  4546.3   32.08  4546.6   32.08  4601.3   31.17  4675.1   29.94
  4675.8   29.86  4681.6    29.2  4686.2   28.67  4707.9   27.85    4709   27.28
  4725.6   27.63    4741   27.25  4741.5   27.24  4742.5   27.72  4744.8   27.64
  4762.7   28.33  4772.1   28.44  4809.4    29.2  4812.8   29.21  4843.1   29.25
  4864.7   29.43    4872   29.49  4872.3   29.49  4878.3   28.36  4882.4   28.92
  4889.1   29.82  4905.5   30.27  4923.2   30.11  4933.7   30.02 4942.39   27.51
  4942.5   27.48 4942.61   27.45  4944.6   26.87  4950.6   25.55 4950.72   25.52
 4950.81   25.51  4973.7    20.7  4990.3   13.36 4991.69   11.84  4993.1   10.29
  4998.1    9.77  5002.9   10.19  5006.8   10.33  5013.1   10.69  5020.9   10.97
    5021   10.97  5024.5   13.68  5024.8   13.95  5043.2   18.91  5061.6   24.86
 5063.05   25.17  5063.1   25.18 5063.16   25.19 5073.49   27.45  5073.6   27.48
 5073.71    27.5  5083.5   29.64  5092.7    29.7  5099.1   29.74  5111.8   29.56
  5140.6   29.45  5140.7   29.05  5148.1   28.98  5164.1   28.82  5177.6   28.86
  5190.9   28.21  5193.5   28.18  5232.9   27.67    5237   27.37  5241.1   27.68
  5249.4   27.68  5258.4   28.35  5277.2   28.36  5337.8   28.37  5358.6   28.38
  5383.6   28.67  5408.6   28.97  5412.8   28.85  5483.6   26.79  5487.8    26.8
  5498.6   26.81  5507.8   27.04  5513.6   27.19  5543.6   29.93  5597.8   30.53
  5603.6   30.59  5627.8   31.38  5651.7   32.16  5682.6   32.14  5682.8   32.14
  5682.9   32.14  5715.2   32.12  5755.1   32.42
BR D #Mann= 5
  4505.1      .2  4546.6      .1  4950.6     .04  5063.1      .1  5682.6      .2
BR D Banks=4950.6,5063.1
BC Design=,, 0 ,, 0 ,,,,,,
BC HTab HWMax=33.24

Type RM Length L Ch R = 1 ,38934.8 ,422.5,422.5,422.5
BEGIN DESCRIPTION:
Downstream Section of Bridge/Culvert/Weir
END DESCRIPTION:
XS GIS Cut Line= 6
      3187592.26     13858048.19      3187453.56     13858147.59
      3187323.75     13858303.71      3187216.75     13858440.54
      3187142.36     13858535.03      3186580.07     13858383.46
#Sta/Elev= 30
  4505.1   32.75  4546.6   32.06  4675.1   29.92    4709   27.26  4741.5   27.22
  4809.4   29.18  4872.3   29.47  4878.3   28.34  4889.1    29.8  4933.7      30
  4950.6   25.53  4973.7   20.68  4990.3   13.34  4993.1   10.27  4998.1    9.75
    5021   10.95  5024.8   13.93  5063.1   25.16  5083.5   29.62  5140.6   29.43
    5237   27.35  5258.4   28.33  5408.6   28.95  5498.6   26.79  5513.6   27.17
  5543.6   29.91  5603.6   30.57  5651.7   32.14  5682.6   32.12  5755.1    32.4
#Mann= 5 , 1 , 0
  4505.1      .2       0  4546.6      .1       0  4950.6     .04       0
  5063.1      .1       0  5682.6      .2       0
#XS Ineff= 2 , 0
       0    4941    28.5    5073       0    28.2
Permanent Ineff=
       F       F
Bank Sta=4950.6,5063.1
XS Rating Curve= 0
Exp/Cntr=.5,.3

Type RM Length L Ch R = 1 ,38512.3 ,390.7,455.3,513.9
BEGIN DESCRIPTION:
Cross Section 38512.3 - Interpolated
END DESCRIPTION:
XS GIS Cut Line= 5
      3187664.84     13857871.43      3187159.26      13857953.5
      3186981.97     13858084.82      3186624.13     13858265.39
       3186338.5     13858314.63
#Sta/Elev= 30
  4344.9    33.8  4614.9    30.3  4684.9    29.9  4734.9    27.5  4804.9    29.6
  4907.1    30.1  4927.1    30.7  4928.3   28.24  4983.6   15.31  4988.3   10.89
  4990.5    9.81  5000.4     9.1  5009.7    9.68  5011.7   10.94    5015    14.9
  5059.6   28.52  5067.1    27.9  5077.1    29.2  5227.7    28.7  5277.7    26.6
  5297.7    26.5  5327.7    29.5  5357.7    30.8  5407.7    31.4  5447.7      33
  5518.5    32.6  5568.5    30.4  5588.5    30.5  5618.5    32.4  5768.4    32.4
#Mann= 3 , 1 , 0
  4344.9      .1       0  4928.3     .04       0  5059.6      .1       0
Bank Sta=4928.3,5059.6
XS Rating Curve= 0
Exp/Cntr=.3,.1

Type RM Length L Ch R = 1 ,38057.0 ,1155,1159,1072.3
BEGIN DESCRIPTION:
Cross Section 38057
Located At: AT SCOTTER LN
END DESCRIPTION:
XS GIS Cut Line= 5
      3187667.33     13857862.42      3187138.17     13857652.96
      3186774.37     13857605.19      3186374.61     13857512.47
      3186166.57      13857725.3
#Sta/Elev= 30
    4213   33.79  4213.1   33.79    4563   31.05    4578   30.49    4648   29.97
    4703   27.18    4728   27.16  4802.1   29.44  4928.3   27.55  4983.6   14.62
  4988.3    10.2  4990.5    9.12  5000.4    8.41  5009.7    8.99  5011.7   10.25
    5015   14.21  5059.6   27.83  5105.1   29.04  5147.1   29.07    5209   27.92
    5244   26.24    5274   26.45    5304   27.94    5519   29.75    5549    30.8
  5629.4   30.76  5654.4   29.53  5694.4   29.45  5759.4   32.39    5857   32.37
#Mann= 4 , 1 , 0
    4213      .2       0  4213.1      .1       0  4928.3     .04       0
  5059.6      .1       0
#XS Ineff= 2 , 0
       0  4802.1   29.44  5147.1       0   29.07
Permanent Ineff=
       F       F
Bank Sta=4928.3,5059.6
XS Rating Curve= 0
Exp/Cntr=.3,.1

Type RM Length L Ch R = 1 ,36898.0 ,917.5,1072,1188.6
BEGIN DESCRIPTION:
Cross Section 36899
Located At: 2ND XS US WOODFOREST AT BW8
END DESCRIPTION:
XS GIS Cut Line= 4
      3187056.14     13856491.38      3186553.96     13856639.64
      3185724.79     13856609.41      3185364.84     13856565.94
#Sta/Elev= 30
    4658   32.28    4768   30.73    4798   30.95    4858   30.05  4863.9   29.27
  4922.4   28.22  4979.9   15.93  4987.8    9.73  4999.9     8.1  5011.4    9.38
  5022.7   15.58    5033   17.13  5057.6   28.06  5130.8   28.46  5191.6   29.77
  5231.6   27.83  5276.6   27.94  5306.6   26.75  5336.6   26.43  5366.6   28.99
  5396.6   28.15  5426.6   26.48  5786.6   27.12  6086.3   29.51  6116.3   31.66
  6196.3   31.46  6253.9   30.36  6271.3   31.67  6316.3   33.13  6373.9   34.05
#Mann= 4 , 1 , 0
    4658     .14       0  4922.4     .04       0  5057.6     .14       0
  6253.9      .1       0
#XS Ineff= 2 , 0
       0                  5191.6       0   29.77
Permanent Ineff=
       F       F
Bank Sta=4922.4,5057.6
XS Rating Curve= 0
Exp/Cntr=.3,.1

Type RM Length L Ch R = 1 ,35826.0 ,595,580,531.9
BEGIN DESCRIPTION:
Cross Section 35826
Located At: 1ST XS US WOODFOREST AT BW8
END DESCRIPTION:
XS GIS Cut Line= 5
      3187068.35     13856282.28      3186535.51      13856076.5
      3186370.15     13856010.35      3186098.22     13855808.24
       3185580.7     13855754.85
#Sta/Elev= 30
  4054.7   33.67  4054.9   33.67  4114.7   33.59  4149.7   29.24  4184.7   32.41
  4239.7   32.65  4274.7   31.05  4389.7   31.93  4414.7   28.99  4439.7   31.94
  4549.7   31.23  4635.9   29.25  4685.9   25.69  4772.8   28.88    4884   25.08
    4893   23.21  4946.6   23.14  4977.4   16.09  4991.4    8.12  4998.6    7.13
  5009.1    8.04  5012.9      13  5046.7   26.79    5104    28.4  5247.8   26.66
  5467.8   28.04  5577.8   30.28  5627.8   35.68  5662.9   36.22  5663.1   36.22
#Mann= 6 , 1 , 0
  4054.7      .2       0  4054.9      .1       0  4772.8     .07       0
  4946.6     .04       0  5046.7      .1       0  5662.9      .2       0
Bank Sta=4946.6,5046.7
XS Rating Curve= 0
Exp/Cntr=.3,.1

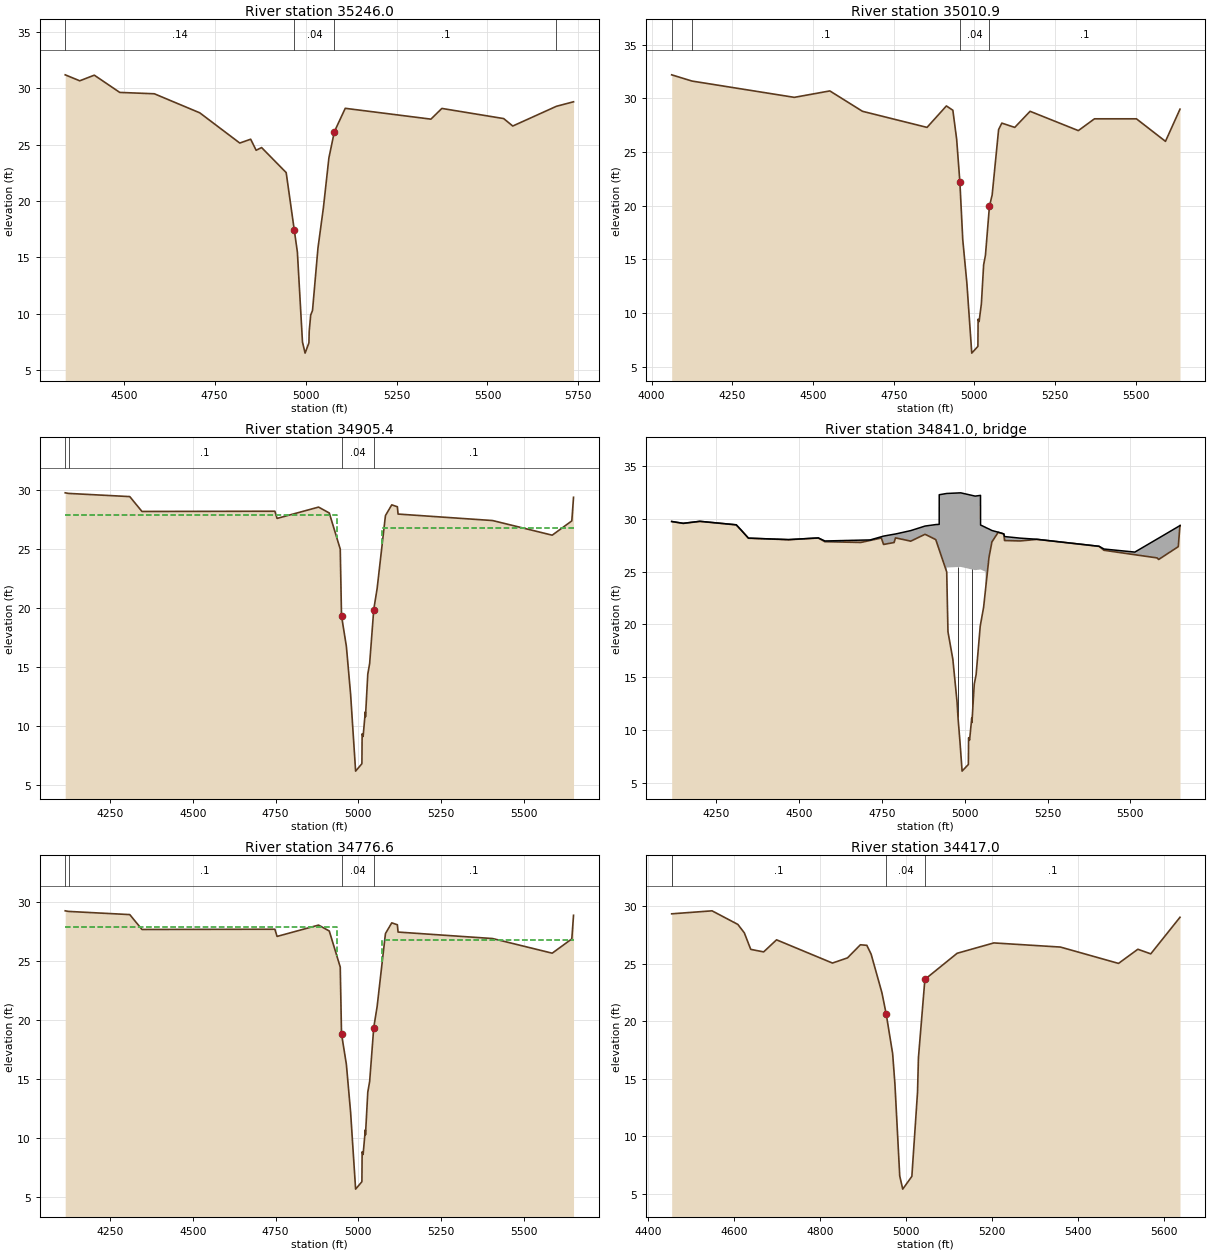
Type RM Length L Ch R = 1 ,35246.0 ,226,235.1,246.3
BEGIN DESCRIPTION:
Cross Section 35246-Interpolated
END DESCRIPTION:
XS GIS Cut Line= 4
      3187114.99     13855562.07      3186219.18      13855329.2
        3185834.     13855218.82      3185774.41     13855179.39
#Sta/Elev= 30
    4339   31.19    4379   30.66    4419   31.16    4489   29.63    4584   29.51
    4709   27.82    4819   25.14    4849   25.48    4864    24.5    4879   24.74
  4946.6   22.52    4969   17.39  4977.4   15.47  4991.4     7.5  4998.6    6.51
  5009.1    7.42  5009.9    8.44    5014    9.89    5019   10.29    5034   15.83
    5049   19.42    5064   23.81    5079   26.14    5109   28.22  5344.6   27.26
  5374.6   28.21  5544.6   27.31  5569.6   26.65  5689.7    28.4  5736.7    28.8
#Mann= 4 , 1 , 0
    4339     .14       0    4969     .04       0    5079      .1       0
  5689.7      .2       0
Bank Sta=4969,5079
XS Rating Curve= 0
Exp/Cntr=.3,.1

Type RM Length L Ch R = 1 ,35010.9 ,174.1,105.5,93.1
BEGIN DESCRIPTION:
Cross Section 35010.9 - Interpolated
END DESCRIPTION:
XS GIS Cut Line= 6
      3187369.37       13855616.       3186899.9     13855346.79
      3186604.43     13855195.77      3186420.58     13855123.55
      3186361.49     13855116.98      3185916.95     13855137.05
#Sta/Elev= 30
    4062    32.2  4124.8   31.62    4442    30.1    4552    30.7  4653.2    28.8
  4853.2    27.3  4913.2    29.3  4933.2    28.9    4945    26.2    4955    22.2
  4963.9   16.84  4976.7   12.77  4991.8    6.26  5010.8    6.89  5011.5    9.42
  5014.5     9.2  5021.6   10.86  5028.6   14.49  5034.2   15.38  5046.6   19.96
    5055      21    5075    27.1    5085    27.7    5125    27.3  5172.5    28.8
    5322      27    5372    28.1    5502    28.1    5592      26    5637      29
#Mann= 4 , 1 , 0
    4062      .2       0  4124.8      .1       0    4955     .04       0
  5046.6      .1       0
Bank Sta=4955,5046.6
XS Rating Curve= 0
Exp/Cntr=.5,.3

Type RM Length L Ch R = 1 ,34905.4 ,128.8,128.8,128.8
BEGIN DESCRIPTION:
Upstream Section of Bridge/Culvert/Weir
END DESCRIPTION:
XS GIS Cut Line= 6
      3187420.23     13854795.92      3187091.77     13854944.81
      3186807.12     13855038.28      3186573.46     13855076.52
      3186072.14     13855068.02       3185935.9     13855074.83
#Sta/Elev= 30
  4114.8   29.74  4124.8   29.69  4309.8   29.42  4346.6   28.16    4748   28.18
  4754.6   27.57  4879.9   28.53  4912.3   28.03  4945.4   24.97  4949.2   19.32
  4963.9   16.73  4976.7   12.66  4991.8    6.15  5010.8    6.78  5011.5    9.31
  5014.5    9.09    5021   11.17  5021.6   10.75  5028.6   14.38  5034.2   15.27
  5046.6   19.85  5056.8   21.63  5081.9   27.81  5100.9   28.72  5117.9   28.56
    5120   27.94  5405.5   27.39  5585.5   26.15  5644.7   27.36  5649.9   29.36
#Mann= 4 , 1 , 0
  4114.8      .2       0  4124.8      .1       0  4949.2     .04       0
  5046.6      .1       0
#XS Ineff= 2 , 0
       0    4935    27.9    5072       0    26.8
Permanent Ineff=
       F       F
Bank Sta=4949.2,5046.6
XS Rating Curve= 0
Exp/Cntr=.5,.3

Type RM Length L Ch R = 3 ,34841.0 ,,,
BEGIN DESCRIPTION:
WOODFOREST ROAD
Structure ID: N00-26
END DESCRIPTION:
Bridge Culvert--1,0,-1,-1, 0
Deck Dist Width WeirC Skew NumUp NumDn MinLoCord MaxHiCord MaxSubmerge Is_Ogee
10,108.8,2.6,0, 42, 42, , , .95, 0, 1,1,,
  4114.8  4149.8  4199.8  4309.8  4346.6  4467.6  4557.6  4577.6  4686.2  4714.2
    4748  4754.6  4786.5  4790.8  4836.7  4879.9  4912.3 4922.69  4922.8  4945.4
 4945.51  4945.6  4987.7  5031.4  5047.5 5047.61 5062.49  5062.6  5073.1  5081.9
  5100.9  5117.9    5120  5166.7  5217.7  5405.5  5420.5  5513.5  5580.5  5585.5
  5644.7  5649.9
   29.73   29.56   29.75   29.42   28.16   28.02   28.18   27.89   27.97   27.99
   28.29   28.35   28.53   28.55   28.87    29.3   29.44   29.46   32.26   32.38
   32.38   32.38   32.44   32.13    32.2    29.4   29.18   29.17   29.02   28.88
   28.72   28.56   28.31   28.16   28.05   27.39   27.13   26.84   28.07   28.16
   29.25   29.35
   29.73   29.55   29.74   29.41   28.15   28.01   28.17   27.82   27.75   27.94
   28.17   27.56   27.74   28.18   27.87   28.52   28.02   27.06   27.05   24.96
    24.8   25.38   25.44   25.13    25.2    25.2   24.98    23.3   26.33    27.8
   28.71   28.55   27.93   27.89   28.04   27.38   27.01   26.59   26.29   26.14
   27.35   29.35
  4114.8  4149.8  4199.8  4309.8  4346.6  4467.6  4557.6  4577.6  4686.2  4714.2
    4748  4754.6  4786.5  4790.8  4836.7  4879.9  4912.3 4922.69  4922.8  4945.4
 4945.51  4945.6  4987.7  5031.4  5047.5 5047.61 5062.49  5062.6  5073.1  5081.9
  5100.9  5117.9    5120  5166.7  5217.7  5405.5  5420.5  5513.5  5580.5  5585.5
  5644.7  5649.9
   29.73   29.56   29.75   29.42   28.16   28.02   28.18   27.89   27.97   27.99
   28.29   28.35   28.53   28.55   28.87    29.3   29.44   29.46   32.26   32.38
   32.38   32.38   32.44   32.13    32.2    29.4   29.18   29.17   29.02   28.88
   28.72   28.56   28.31   28.16   28.05   27.39   27.13   26.84   28.07   28.16
   29.25   29.35
   29.26   29.08   29.27   28.94   27.68   27.54    27.7   27.35   27.28   27.47
    27.7   27.09   27.27   27.71    27.4   28.05   27.55   26.59   26.58   24.49
   24.33   24.91   24.97   24.66   24.73   24.73   24.51   22.83   25.86   27.33
   28.24   28.08   27.46   27.42   27.57   26.91   26.54   26.12   25.82   25.67
   26.88   28.88
Pier Skew, UpSta & Num, DnSta & Num=  ,4979.5, 2 ,4979.5, 2 , 0 , 0 , 0 ,,
     1.2     1.2
    9.99   26.43
     1.2     1.2
    9.52   25.96
Pier Skew, UpSta & Num, DnSta & Num=  ,5021, 2 ,5021, 2 , 0 , 0 , 0 ,,
     1.3     1.3
    9.77    26.2
     1.3     1.3
     9.3   25.73
BR Coef= 1 , 1 , 0 ,1.25, 0 ,,,.8,0,2,0,
WSPro=,,,, 1 ,,,, 0 ,,,, 0 ,,,,-1 ,-1 ,-1 , 0 , 0 , 0 , 0 , 0
BR U #Sta/Elev= 76
  4114.8   29.73  4124.8   29.68  4125.6   29.67  4149.8   29.55  4199.8   29.74
  4309.8   29.41  4326.6   28.86  4346.6   28.15  4467.6   28.01  4475.4   28.02
  4557.6   28.17  4577.6   27.82  4686.2   27.75  4714.2   27.94    4748   28.17
  4753.7   27.64  4754.6   27.56  4786.3   27.74  4786.5   27.74  4790.8   28.18
  4822.6   27.97  4836.7   27.87  4879.9   28.52  4883.9   28.46  4909.1   28.07
  4912.3   28.02 4922.69   27.06  4922.8   27.05 4922.91   27.04  4945.4   24.96
 4945.51    24.8  4945.6   24.66  4945.9   24.22  4946.3   23.62  4949.2   19.31
  4963.9   16.72  4976.7   12.65  4979.5   11.22  4985.6    8.85  4987.7    7.94
    4991    6.52  4991.8    6.14  5010.8    6.77  5011.5     9.3  5014.5    9.08
    5021   11.16  5021.6   10.74  5028.6   14.37  5031.4   14.81  5034.2   15.26
  5046.6   19.84 5047.39   19.98  5047.5      20 5047.61   20.02  5056.8   21.62
  5062.4   23.24 5062.49   23.26  5062.6    23.3  5073.1   26.33  5081.9    27.8
  5100.9   28.71  5117.9   28.55    5120   27.93    5122   27.93  5166.7   27.89
  5193.8   27.97  5217.7   28.04  5258.3    27.9  5405.5   27.38  5420.5   27.01
  5513.5   26.59  5580.5   26.29  5585.5   26.14  5644.7   27.35  5649.8   29.35
  5649.9   29.35
BR U #Mann= 4
  4114.8      .2  4124.8      .1  4949.2     .04  5046.6      .1
BR U Banks=4949.2,5046.6
BR D #Sta/Elev= 76
  4114.8   29.26  4124.8   29.21  4125.6    29.2  4149.8   29.08  4199.8   29.27
  4309.8   28.94  4326.6   28.39  4346.6   27.68  4467.6   27.54  4475.4   27.55
  4557.6    27.7  4577.6   27.35  4686.2   27.28  4714.2   27.47    4748    27.7
  4753.7   27.17  4754.6   27.09  4786.3   27.27  4786.5   27.27  4790.8   27.71
  4822.6    27.5  4836.7    27.4  4879.9   28.05  4883.9   27.99  4909.1    27.6
  4912.3   27.55 4922.69   26.59  4922.8   26.58 4922.91   26.57  4945.4   24.49
 4945.51   24.33  4945.6   24.19  4945.9   23.75  4946.3   23.15  4949.2   18.84
  4963.9   16.25  4976.7   12.18  4979.5   10.75  4985.6    8.38  4987.7    7.47
    4991    6.05  4991.8    5.67  5010.8     6.3  5011.5    8.83  5014.5    8.61
    5021   10.69  5021.6   10.27  5028.6    13.9  5031.4   14.34  5034.2   14.79
  5046.6   19.37 5047.39   19.51  5047.5   19.53 5047.61   19.55  5056.8   21.15
  5062.4   22.77 5062.49   22.79  5062.6   22.83  5073.1   25.86  5081.9   27.33
  5100.9   28.24  5117.9   28.08    5120   27.46    5122   27.46  5166.7   27.42
  5193.8    27.5  5217.7   27.57  5258.3   27.43  5405.5   26.91  5420.5   26.54
  5513.5   26.12  5580.5   25.82  5585.5   25.67  5644.7   26.88  5649.8   28.88
  5649.9   28.88
BR D #Mann= 4
  4114.8      .2  4124.8      .1  4949.2     .04  5046.6      .1
BR D Banks=4949.2,5046.6
BC Design=,, 0 ,, 0 ,,,,,,
BC HTab HWMax=29.75

Type RM Length L Ch R = 1 ,34776.6 ,359.6,359.6,359.6
BEGIN DESCRIPTION:
Downstream Section of Bridge/Culvert/Weir
END DESCRIPTION:
XS GIS Cut Line= 6
      3187450.03     13854670.61      3187121.57     13854819.51
      3186836.92     13854912.98      3186603.26     13854951.22
      3186101.94     13854942.72       3185965.7     13854949.53
#Sta/Elev= 30
  4114.8   29.25  4124.8    29.2  4309.8   28.93  4346.6   27.67    4748   27.69
  4754.6   27.08  4879.9   28.04  4912.3   27.54  4945.4   24.48  4949.2   18.83
  4963.9   16.24  4976.7   12.17  4991.8    5.66  5010.8    6.29  5011.5    8.82
  5014.5     8.6    5021   10.68  5021.6   10.26  5028.6   13.89  5034.2   14.78
  5046.6   19.36  5056.8   21.14  5081.9   27.32  5100.9   28.23  5117.9   28.07
    5120   27.45  5405.5    26.9  5585.5   25.66  5644.7   26.87  5649.9   28.87
#Mann= 4 , 1 , 0
  4114.8      .2       0  4124.8      .1       0  4949.2     .04       0
  5046.6      .1       0
#XS Ineff= 2 , 0
       0    4935    27.9    5072       0    26.8
Permanent Ineff=
       F       F
Bank Sta=4949.2,5046.6
XS Rating Curve= 0
Exp/Cntr=.5,.3

Type RM Length L Ch R = 1 ,34417.0 ,499,550,687.8
BEGIN DESCRIPTION:
Cross Section 34417-Interpolated
END DESCRIPTION:
XS GIS Cut Line= 4
      3187285.11      13854648.5      3187221.51     13854642.01
      3186537.37     13854601.76      3186104.54     13854609.71
#Sta/Elev= 30
  4455.7   29.32  4455.9   29.32  4549.6   29.58  4609.6    28.4  4624.6   27.67
  4639.6   26.23  4669.6   26.01  4699.6   27.06  4829.6   25.04  4864.6   25.49
  4894.6   26.63  4909.6   26.58  4919.6   25.81  4944.6   22.47  4954.6   20.62
  4969.6   17.17  4974.9   14.54  4986.1    6.53  4993.1    5.39  5014.3     6.5
  5027.5   13.83  5029.6   16.81  5044.6   23.62  5119.6   25.89  5204.9   26.79
  5359.9   26.43  5494.9   25.01  5539.9   26.24  5569.9   25.84  5637.9   29.02
#Mann= 4 , 1 , 0
  4455.7      .2       0  4455.9      .1       0  4954.6     .04       0
  5044.6      .1       0
Bank Sta=4954.6,5044.6
XS Rating Curve= 0
Exp/Cntr=.3,.1

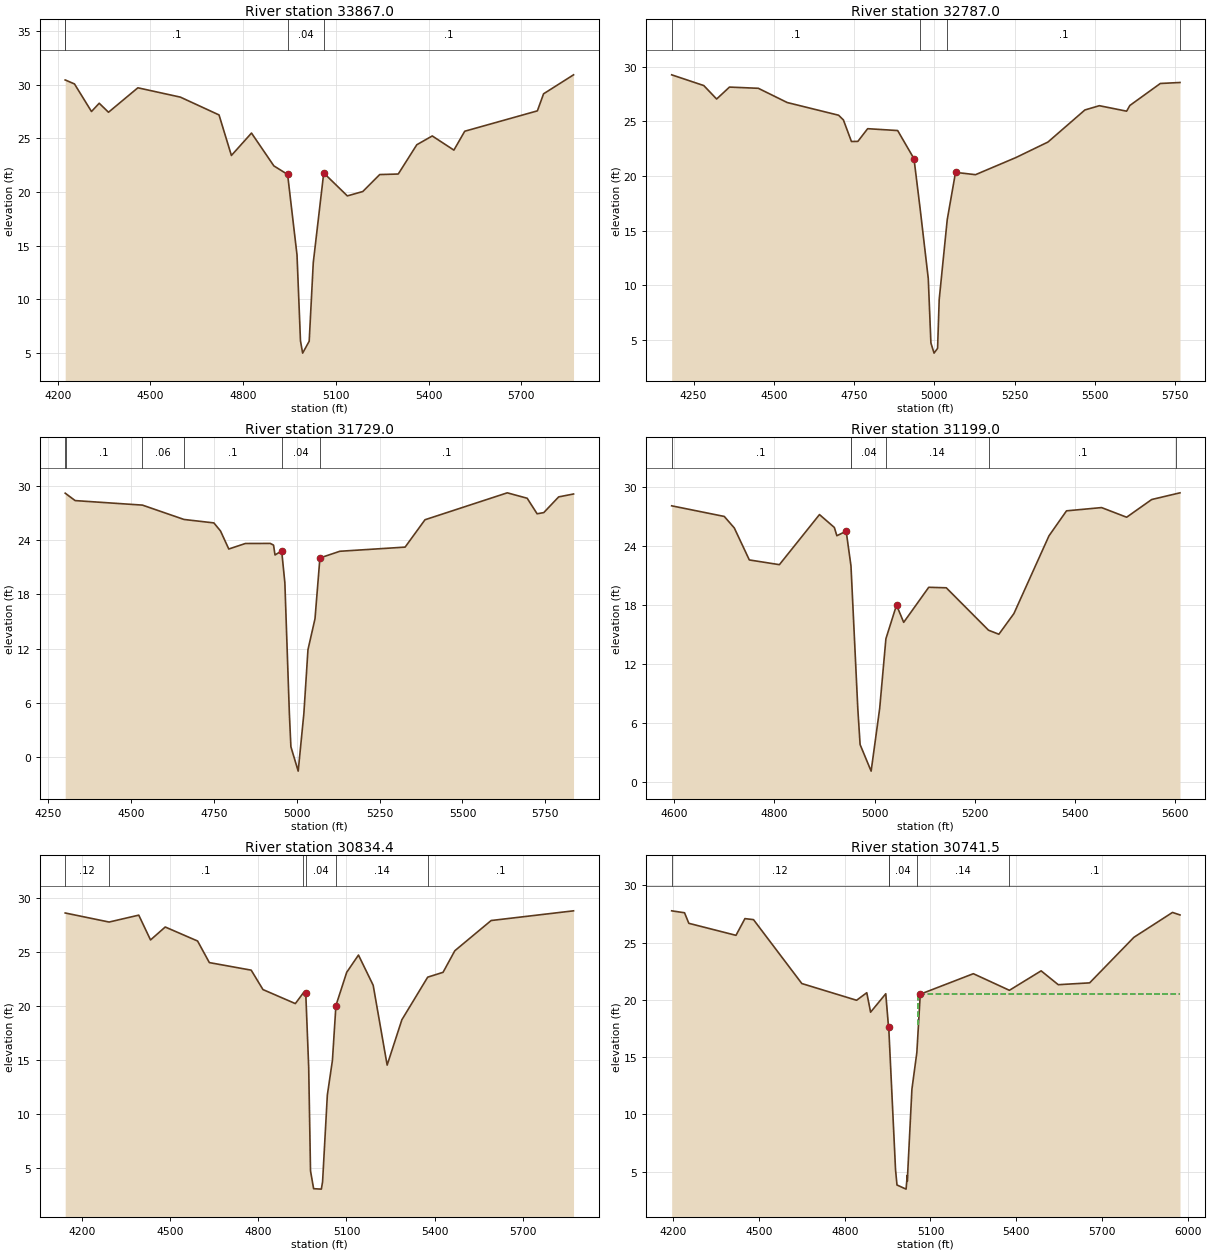
Type RM Length L Ch R = 1 ,33867.0 ,1075,1080,1087
BEGIN DESCRIPTION:
Cross Section 33867
Located At: 1ST XS DS WOODFOREST ALONG OVERBLUFF
END DESCRIPTION:
XS GIS Cut Line= 4
      3187578.25     13854758.96      3187472.04     13854546.53
      3186928.23     13854045.21      3186414.17     13853620.37
#Sta/Elev= 30
  4224.5   30.45  4224.7   30.45  4254.5   30.08  4309.5   27.51  4334.5   28.28
  4364.5   27.44  4459.5   29.72    4597   28.85    4722   27.19    4762   23.41
    4827    25.5  4899.3   22.44  4943.8   21.64  4974.2   14.13  4985.4    6.12
  4992.4    4.98  5013.6    6.09  5026.8   13.42  5060.6   21.78    5137   19.64
    5187   20.05  5241.6   21.63  5301.6   21.68  5361.6   24.41  5411.6   25.23
  5481.6   23.91  5516.6   25.67  5751.6   27.57  5771.6   29.16  5868.5   30.93
#Mann= 4 , 1 , 0
  4224.5      .2       0  4224.7      .1       0  4943.8     .04       0
  5060.6      .1       0
Bank Sta=4943.8,5060.6
XS Rating Curve= 0
Exp/Cntr=.3,.1

Type RM Length L Ch R = 1 ,32787.0 ,1157.2,1058,944.9
BEGIN DESCRIPTION:
Cross Section 32787
Located At: 2ND XS DS WOODFOREST ALONG OVERBLUFF
END DESCRIPTION:
XS GIS Cut Line= 5
      3188300.44     13853957.75      3188135.13     13853744.57
       3187908.9     13853490.07      3187576.09     13853170.32
      3187232.41     13852791.83
#Sta/Elev= 30
  4181.9   29.24  4281.9   28.26  4321.9   27.03  4361.9   28.12  4451.7   28.01
  4541.7   26.71  4701.7   25.55  4716.7   25.12  4741.7   23.15  4761.7   23.16
  4792.2   24.32  4885.7   24.15  4936.5   21.58  4955.7      17    4981   10.63
  4989.2    4.75    4999    3.82    5010    4.26    5015    8.71    5040      16
  5065.9   20.33  5128.1   20.12  5253.7   21.68  5353.7    23.1  5468.7   26.03
  5513.7   26.42  5598.7   25.92  5608.7   26.44  5703.7   28.45  5764.9   28.54
#Mann= 4 , 1 , 0
  4181.9      .1       0  4955.7     .04       0    5040      .1       0
  5764.9      .2       0
Bank Sta=4936.5,5065.9
XS Rating Curve= 0
Exp/Cntr=.3,.1

Type RM Length L Ch R = 1 ,31729.0 ,496.4,530,376.3
BEGIN DESCRIPTION:
Cross Section 31729
Located At: 1ST XS US WOODFORD
END DESCRIPTION:
XS GIS Cut Line= 6
      3189068.29     13852511.22        3188655.     13852509.05
      3188178.63     13852526.45      3187928.48     13852591.71
      3187789.76     13852576.48      3187554.43     13852508.77
#Sta/Elev= 30
  4302.1    29.2  4304.3   29.14  4332.1   28.38    4535   27.88  4660.4   26.29
  4750.4   25.91  4770.4   25.02  4795.4   23.02  4845.4   23.63  4920.4   23.64
  4930.4   23.45  4934.8   22.36  4954.9   22.81  4964.5   19.28  4978.1    4.79
  4982.7    1.13  5004.7   -1.57  5021.8    4.81  5034.2   11.88  5055.4    15.3
  5070.2   22.03  5130.4   22.77  5327.1   23.23  5387.1   26.26  5635.2   29.24
  5695.2   28.64  5725.2   26.92  5745.2   27.05  5790.2   28.79    5835   29.11
#Mann= 6 , 1 , 0
  4302.1      .2       0  4304.3      .1       0    4535     .06       0
  4660.4      .1       0  4954.9     .04       0  5070.2      .1       0
Bank Sta=4954.9,5070.2
XS Rating Curve= 0
Exp/Cntr=.3,.1

Type RM Length L Ch R = 1 ,31199.0 ,339.8,364.6,363.3
BEGIN DESCRIPTION:
Cross Section 31199-Interpolated
END DESCRIPTION:
XS GIS Cut Line= 4
      3188482.54      13852046.6      3188194.63     13852129.95
      3188067.69     13852184.94      3187565.22     13852467.72
#Sta/Elev= 30
  4594.8   28.11  4699.8   27.03  4719.8   25.86  4749.8   22.61  4809.8   22.13
  4889.8   27.22  4919.5   25.91  4924.5   25.07  4943.1   25.53  4952.1   22.22
  4952.7      22  4966.3    7.51  4970.9    3.85  4992.9    1.15    5010    7.53
  5022.4    14.6  5043.6   18.02  5057.9   16.27  5107.9   19.83  5142.9   19.78
  5227.2   15.47  5247.9   15.06  5277.9   17.16  5347.9   25.06  5382.9    27.6
  5452.9   27.93  5502.9   26.95  5552.9   28.75  5601.8   29.34  5609.4   29.43
#Mann= 6 , 1 , 0
  4594.8      .1       0  4952.1     .14       0  4952.7     .04       0
  5022.4     .14       0  5227.2      .1       0  5601.8      .2       0
Bank Sta=4943.1,5043.6
XS Rating Curve= 0
Exp/Cntr=.3,.1

Type RM Length L Ch R = 1 ,30834.4 ,91,92.9,114.9
BEGIN DESCRIPTION:
Cross Section 30834.4 - Interpolated
END DESCRIPTION:
XS GIS Cut Line= 6
      3188905.82     13851765.02      3188393.67     13851755.18
      3188121.18     13851794.57      3187960.31      13851847.1
       3187595.9     13852057.21      3187474.43     13852385.51
#Sta/Elev= 30
    4144    28.6  4293.2   27.76    4394    28.4    4434    26.1    4484    27.3
    4594      26    4634      24  4776.2    23.3  4816.2    21.5  4926.2    20.2
  4953.6    21.2  4961.6    21.2  4971.6    14.3  4977.8    4.69  4988.4    3.04
  5014.6       3  5018.8    3.68    5035   11.72  5052.3   14.94  5064.2   20.02
  5100.8    23.1  5140.8    24.7  5190.8    21.9  5238.3    14.5  5288.3    18.7
  5376.1   22.65  5428.3    23.1  5468.3    25.1  5591.7    27.9  5871.8    28.8
#Mann= 6 , 1 , 0
    4144     .12       0  4293.2      .1       0  4953.6     .14       0
  4961.6     .04       0  5064.2     .14       0  5376.1      .1       0
Bank Sta=4961.6,5064.2
XS Rating Curve= 0
Exp/Cntr=.5,.3

Type RM Length L Ch R = 1 ,30741.5 ,59,59,59
BEGIN DESCRIPTION:
Upstream Section of Bridge/Culvert/Weir
END DESCRIPTION:
XS GIS Cut Line= 6
      3188826.63      13851592.1      3188360.96     13851655.59
      3188130.59     13851701.66      3187849.02      13851763.1
      3187450.28     13851990.28      3187210.23     13852211.34
#Sta/Elev= 30
  4194.5   27.77  4239.5    27.6  4254.5   26.68  4419.5   25.63  4450.8   27.09
  4480.8      27  4649.9   21.42  4841.4   19.96  4877.1   20.62  4890.4   18.92
  4943.5   20.53  4953.2   17.61  4953.6    17.6  4953.9    17.6  4977.7    5.16
  4982.8    3.83  5014.6    3.47  5018.7    4.68  5018.8    4.15    5035   12.19
  5052.3   15.41  5064.2   20.49  5249.9   22.28  5376.1   20.83    5487   22.53
    5547   21.32  5656.8   21.48  5811.8   25.46  5946.7   27.63  5972.9   27.41
#Mann= 6 , 1 , 0
  4194.5     .12       0  4953.2      .1       0  4953.6     .14       0
  4953.9     .04       0  5052.3     .14       0  5376.1      .1       0
#XS Ineff= 2 , 0
       0    4943      20    5058       0    20.5
Permanent Ineff=
       F       F
Bank Sta=4953.2,5064.2
XS Rating Curve= 0
Exp/Cntr=.5,.3