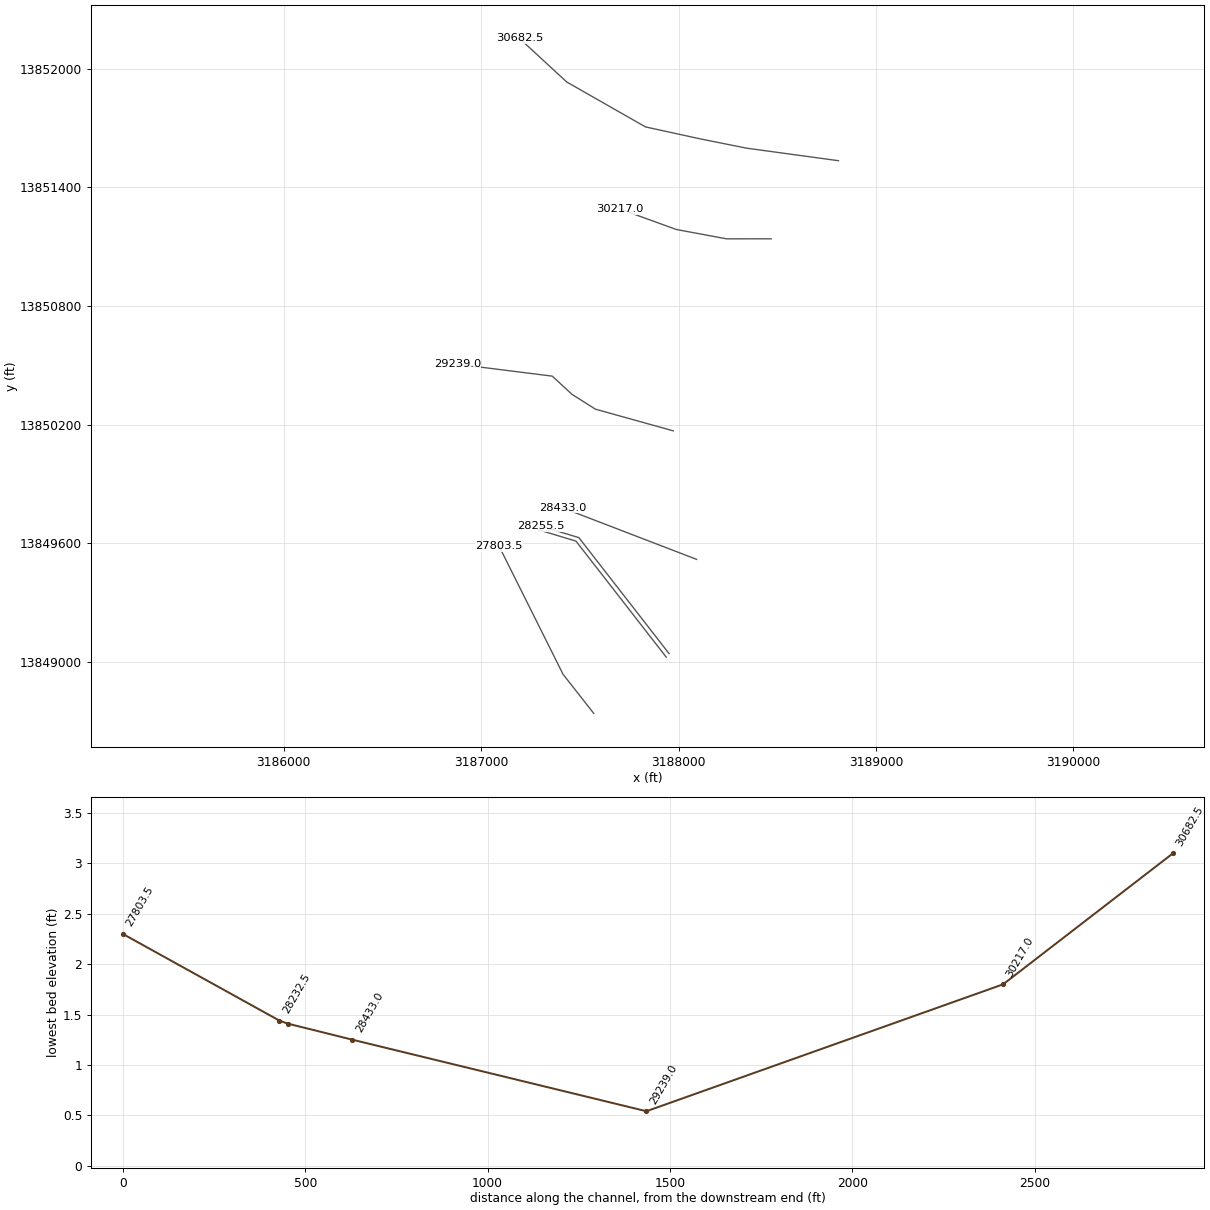
HEC-RAS study N100-00-00.prj: N100-00-00

--- N100-00-00.g01 (geometry) --- (continued)

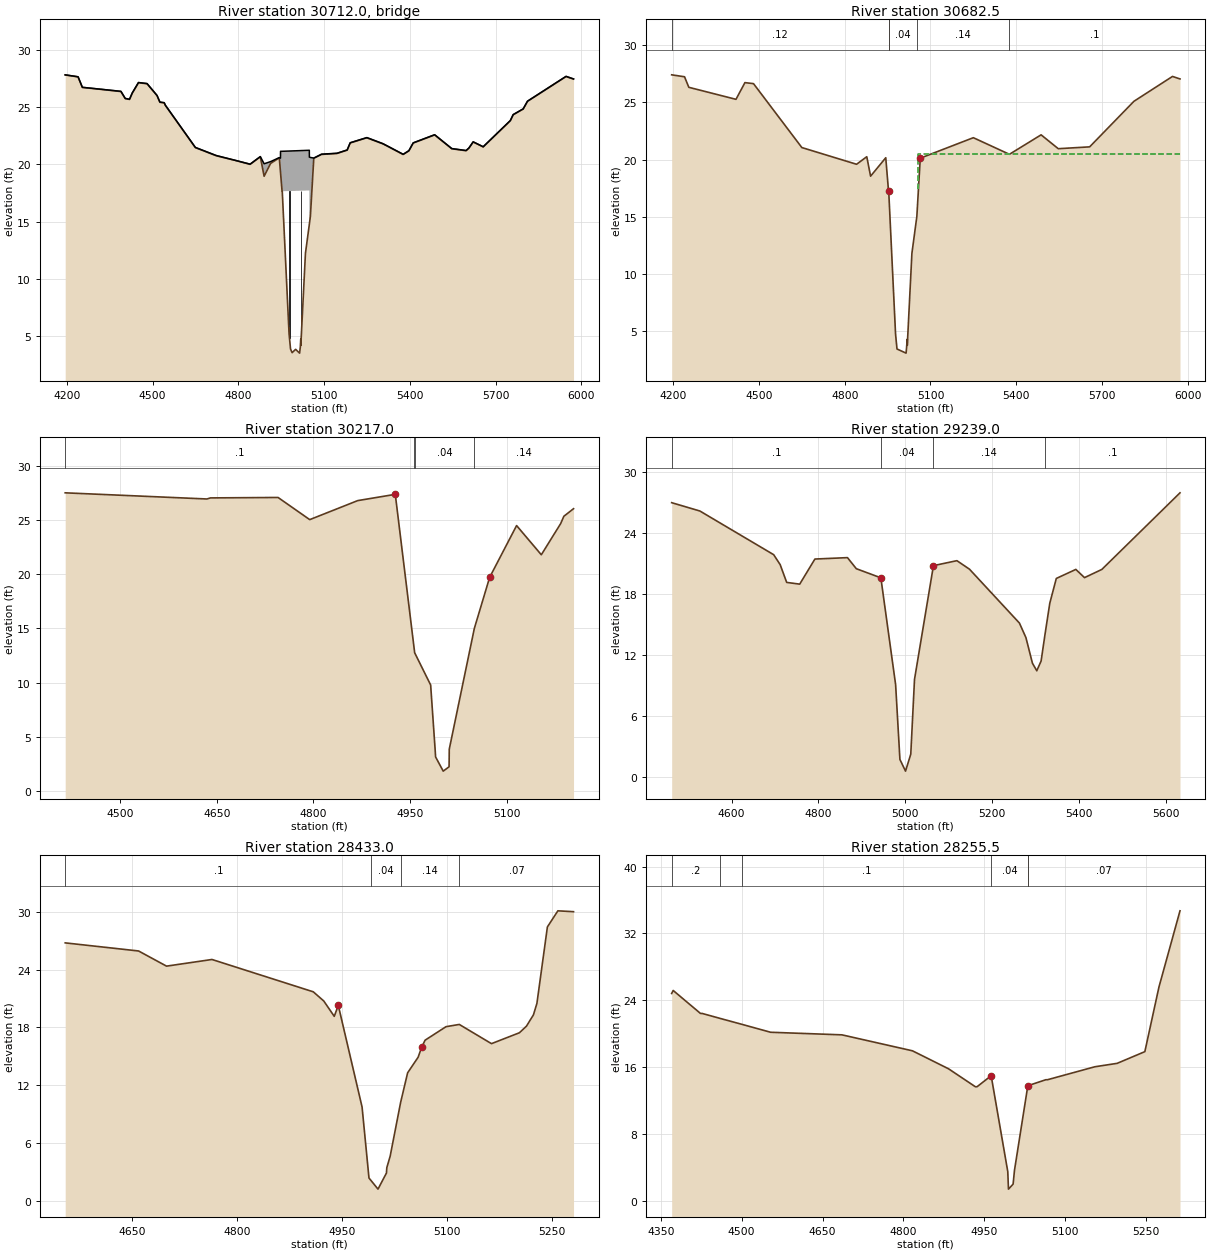
Type RM Length L Ch R = 3 ,30712.0 ,,,
BEGIN DESCRIPTION:
WOODFORD DRIVE
Structure ID: N00-24
END DESCRIPTION:
Bridge Culvert--1,0,-1,-1, 0
Deck Dist Width WeirC Skew NumUp NumDn MinLoCord MaxHiCord MaxSubmerge Is_Ogee
10,39,2.6,0, 50, 50, , , .95, 0, 1,1,,
  4194.5  4239.5  4254.5  4389.5  4404.5  4419.5  4429.5  4450.8  4480.8  4515.8
  4525.8  4540.8  4544.9  4649.9  4723.3  4841.4  4877.1  4890.4  4913.1  4943.5
 4947.67 4947.78  4953.2 5048.57 5048.68 5048.79  5048.9  5052.3  5064.2  5091.3
  5145.3    5181  5191.6  5249.9    5306    5377    5397    5412    5487    5547
    5597  5606.8  5621.8  5656.8  5751.8  5761.8  5796.8  5811.8  5946.7  5972.9
   27.82   27.65   26.73   26.38   25.76   25.69   26.26   27.15   27.06   26.02
   25.44   25.39   25.17   21.48   20.77   20.02   20.68   20.05   20.24   20.59
   20.54   21.14   21.14   21.23   20.63   20.63   20.63    20.6   20.55   20.89
   20.97   21.26   21.89   22.34   21.81   20.88    21.2   21.88   22.59   21.38
   21.21   21.43   21.97   21.54   23.83   24.35   24.85   25.52   27.69   27.46
   27.81   27.64   26.72   26.36   25.74   25.67   26.24   27.13   27.04      26
   25.42   25.37   25.15   21.46   20.75      20   20.66   18.96   20.08   20.57
   19.31   19.28   17.65   17.72   17.72   17.72   14.82   15.45   20.53   20.87
   20.95   21.24   21.87   22.32   21.79   20.86   21.18   21.86   22.57   21.36
   21.19   21.41   21.95   21.52   23.81   24.33   24.83    25.5   27.67   27.45
  4194.5  4239.5  4254.5  4389.5  4404.5  4419.5  4429.5  4450.8  4480.8  4515.8
  4525.8  4540.8  4544.9  4649.9  4723.3  4841.4  4877.1  4890.4  4913.1  4943.5
 4947.67 4947.78  4953.2 5048.57 5048.68 5048.79  5048.9  5052.3  5064.2  5091.3
  5145.3    5181  5191.6  5249.9    5306    5377    5397    5412    5487    5547
    5597  5606.8  5621.8  5656.8  5751.8  5761.8  5796.8  5811.8  5946.7  5972.9
   27.82   27.65   26.73   26.38   25.76   25.69   26.26   27.15   27.06   26.02
   25.44   25.39   25.17   21.48   20.77   20.02   20.68   20.05   20.24   20.59
   20.54   21.14   21.14   21.23   20.63   20.63   20.63    20.6   20.55   20.89
   20.97   21.26   21.89   22.34   21.81   20.88    21.2   21.88   22.59   21.38
   21.21   21.43   21.97   21.54   23.83   24.35   24.85   25.52   27.69   27.46
   27.43   27.26   26.34   25.98   25.36   25.29   25.86   26.75   26.66   25.62
   25.04   24.99   24.77   21.08   20.37   19.62   20.28   18.58    19.7   20.19
   18.93    18.9   17.27   17.34   17.34   17.34   14.44   15.07   20.15   20.49
   20.57   20.86   21.49   21.94   21.41   20.48    20.8   21.48   22.19   20.98
   20.81   21.03   21.57   21.14   23.43   23.95   24.45   25.12   27.29   27.07
Pier Skew, UpSta & Num, DnSta & Num=  ,4979, 2 ,4979, 2 , 0 , 0 , 0 ,,
     1.2     1.2
     3.7   18.66
     1.2     1.2
    3.32   18.28
Pier Skew, UpSta & Num, DnSta & Num=  ,5018.8, 2 ,5018.8, 2 , 0 , 0 , 0 ,,
     1.2     1.2
    3.49   18.69
     1.2     1.2
    3.11   18.31
Abutment Skew #Up #Dn= , 2 , 2
  4947.9  4977.8
   19.19    5.17
  4947.9  4977.8
   18.81    4.79
BR Coef= 1 , 1 , 0 ,1.25, 0 ,,,.8,0,2,0,
WSPro=,,,, 1 ,,,, 0 ,,,, 0 ,,,,-1 ,-1 ,-1 , 0 , 0 , 0 , 0 , 0
BR U #Sta/Elev= 94
  4194.5   27.81  4239.5   27.64  4254.5   26.72  4293.2   26.62  4323.5   26.54
  4389.5   26.36  4404.5   25.74  4419.5   25.67  4429.5   26.24  4430.8   26.28
  4450.8   27.13  4473.5   27.06  4480.8   27.04  4503.5   26.37  4515.8      26
  4525.8   25.42  4540.8   25.37  4544.9   25.15  4649.9   21.46  4664.5   21.32
  4718.9   20.79  4723.3   20.75  4778.6   20.41  4785.7   20.37  4839.6   20.01
  4841.4      20  4877.1   20.66  4890.4   18.96    4903   19.58  4913.1   20.08
  4943.5   20.57  4947.6   19.34 4947.67   19.31 4947.78   19.28 4947.89   19.25
 4948.01   19.21  4948.1   19.19  4953.2   17.65  4953.6   17.64  4953.9   17.64
  4977.7     5.2  4977.8    5.17    4979    4.85  4982.8    3.87  4988.4    3.55
  5000.6    3.84  5014.6    3.51  5017.1    4.06  5018.7    4.72  5018.8    4.19
    5035   12.23  5048.4   14.72 5048.46   14.74 5048.57   14.76 5048.68   14.78
 5048.79    14.8  5048.9   14.82    5049   14.84  5052.3   15.45  5064.2   20.53
  5091.3   20.87  5093.3   20.87    5145   20.95  5145.3   20.95    5181   21.24
  5191.6   21.87  5200.8   21.94  5249.9   22.32  5258.2   22.24    5306   21.79
  5323.8   21.56  5376.1   20.87    5377   20.86    5397   21.18    5412   21.86
    5487   22.57    5547   21.36    5597   21.19  5606.8   21.41  5621.8   21.95
  5646.6   21.65  5656.8   21.52  5711.6   22.84  5726.6    23.2  5741.6   23.56
  5751.8   23.81  5761.8   24.33  5796.8   24.83  5811.8    25.5  5821.6   25.66
  5846.6   26.06  5943.2   27.61  5946.7   27.67  5972.9   27.45
BR U #Mann= 6
  4194.5     .12  4953.2      .1  4953.6     .14  4953.9     .04  5052.3     .14
  5376.1      .1
BR U Banks=4953.2,5064.2
BR D #Sta/Elev= 94
  4194.5   27.43  4239.5   27.26  4254.5   26.34  4293.2   26.24  4323.5   26.16
  4389.5   25.98  4404.5   25.36  4419.5   25.29  4429.5   25.86  4430.8    25.9
  4450.8   26.75  4473.5   26.68  4480.8   26.66  4503.5   25.99  4515.8   25.62
  4525.8   25.04  4540.8   24.99  4544.9   24.77  4649.9   21.08  4664.5   20.94
  4718.9   20.41  4723.3   20.37  4778.6   20.03  4785.7   19.99  4839.6   19.63
  4841.4   19.62  4877.1   20.28  4890.4   18.58    4903    19.2  4913.1    19.7
  4943.5   20.19  4947.6   18.96 4947.67   18.93 4947.78    18.9 4947.89   18.87
 4948.01   18.83  4948.1   18.81  4953.2   17.27  4953.6   17.26  4953.9   17.26
  4977.7    4.82  4977.8    4.79    4979    4.47  4982.8    3.49  4988.4    3.17
  5000.6    3.46  5014.6    3.13  5017.1    3.68  5018.7    4.34  5018.8    3.81
    5035   11.85  5048.4   14.34 5048.46   14.36 5048.57   14.38 5048.68    14.4
 5048.79   14.42  5048.9   14.44    5049   14.46  5052.3   15.07  5064.2   20.15
  5091.3   20.49  5093.3   20.49    5145   20.57  5145.3   20.57    5181   20.86
  5191.6   21.49  5200.8   21.56  5249.9   21.94  5258.2   21.86    5306   21.41
  5323.8   21.18  5376.1   20.49    5377   20.48    5397    20.8    5412   21.48
    5487   22.19    5547   20.98    5597   20.81  5606.8   21.03  5621.8   21.57
  5646.6   21.27  5656.8   21.14  5711.6   22.46  5726.6   22.82  5741.6   23.18
  5751.8   23.43  5761.8   23.95  5796.8   24.45  5811.8   25.12  5821.6   25.28
  5846.6   25.68  5943.2   27.23  5946.7   27.29  5972.9   27.07
BR D #Mann= 6
  4194.5     .12  4953.2      .1  4953.6     .14  4953.9     .04  5052.3     .14
  5376.1      .1
BR D Banks=4953.2,5064.2
BC Design=,, 0 ,, 0 ,,,,,,
BC HTab HWMax=27.77

Type RM Length L Ch R = 1 ,30682.5 ,465.5,465.5,465.5
BEGIN DESCRIPTION:
Downstream Section of Bridge/Culvert/Weir
END DESCRIPTION:
XS GIS Cut Line= 6
      3188810.41     13851535.37      3188344.74     13851598.87
      3188114.37     13851644.94       3187832.8     13851706.38
      3187434.06     13851933.56      3187194.01     13852154.62
#Sta/Elev= 30
  4194.5    27.4  4239.5   27.23  4254.5   26.31  4419.5   25.26  4450.8   26.72
  4480.8   26.63  4649.9   21.05  4841.4   19.59  4877.1   20.25  4890.4   18.55
  4943.5   20.16  4953.2   17.24  4953.6   17.23  4953.9   17.23  4977.7    4.79
  4982.8    3.46  5014.6     3.1  5018.7    4.31  5018.8    3.78    5035   11.82
  5052.3   15.04  5064.2   20.12  5249.9   21.91  5376.1   20.46    5487   22.16
    5547   20.95  5656.8   21.11  5811.8   25.09  5946.7   27.26  5972.9   27.04
#Mann= 6 , 1 , 0
  4194.5     .12       0  4953.2      .1       0  4953.6     .14       0
  4953.9     .04       0  5052.3     .14       0  5376.1      .1       0
#XS Ineff= 2 , 0
       0    4943    19.9    5058       0    20.5
Permanent Ineff=
       F       F
Bank Sta=4953.2,5064.2
XS Rating Curve= 0
Exp/Cntr=.5,.3

Type RM Length L Ch R = 1 ,30217.0 ,998.3,978,935.6
BEGIN DESCRIPTION:
Cross Section 30217
Located At: 2ND XS DS WOODFORD
END DESCRIPTION:
XS GIS Cut Line= 5
      3188469.01     13851140.23      3188243.62     13851139.99
      3188111.67     13851164.52      3187989.23     13851187.27
      3187702.49     13851290.99
#Sta/Elev= 22
  4414.8   27.55  4634.8   26.98  4640.2   27.08  4745.2   27.12  4794.4   25.07
  4868.9   26.83  4927.2   27.41  4956.5   13.14  4957.3   12.75  4982.1    9.77
    4989    3.84  4989.8    3.11  5001.6     1.8  5010.7     2.2    5011    3.83
  5049.9      15  5073.7   19.73  5115.5   24.52  5153.9   21.82  5183.9    24.7
  5188.9   25.38  5203.9   26.08
#Mann= 4 , 1 , 0
  4414.8      .1       0  4956.5     .11       0  4957.3     .04       0
  5049.9     .14       0
Bank Sta=4927.2,5073.7
XS Rating Curve= 0
Exp/Cntr=.3,.1

Type RM Length L Ch R = 1 ,29239.0 ,705,806,818
BEGIN DESCRIPTION:
Cross Section 29239
Located At: 1ST XS US BROOKVIEW
END DESCRIPTION:
XS GIS Cut Line= 5
      3187974.02     13850168.21       3187578.6     13850278.29
      3187460.07     13850353.55      3187360.53     13850445.22
      3186879.33     13850505.63
#Sta/Elev= 30
  4462.1   26.97  4527.1   26.15  4697.1   21.85  4712.1   20.87  4727.1   19.12
  4757.1   18.95  4792.1   21.42  4867.1   21.56  4887.5   20.47  4944.1   19.57
  4978.1    9.05    4988    1.69  5000.9     .54    5013    2.21  5021.6    9.57
  5065.2   20.77  5119.3   21.26  5148.3   20.42  5263.3   15.12  5278.3   13.69
  5293.3   11.17  5303.3   10.42  5313.3   11.38  5322.3   14.01  5333.3   17.07
  5348.3   19.51  5393.3    20.4  5413.3   19.59  5453.3    20.4  5633.3   27.94
#Mann= 4 , 1 , 0
  4462.1      .1       0  4944.1     .04       0  5065.2     .14       0
  5322.3      .1       0
Bank Sta=4944.1,5065.2
XS Rating Curve= 0
Exp/Cntr=.3,.1

Type RM Length L Ch R = 1 ,28433.0 ,267.6,177.5,124.8
BEGIN DESCRIPTION:
Cross Section 28433-Interpolated
END DESCRIPTION:
XS GIS Cut Line= 2
      3188091.76     13849518.06      3187412.67     13849778.78
#Sta/Elev= 30
  4553.8   26.76  4658.8   25.92  4698.8   24.35  4763.8   25.04  4908.8   21.69
  4923.8   20.74  4938.8   19.15  4944.6   20.28  4978.6    9.76  4988.5     2.4
    4992    2.09  5001.4    1.25  5013.5    2.92    5014    3.47  5018.8    4.66
  5033.8   10.24  5043.8    13.3  5058.8   14.91  5063.8   15.93  5068.8   16.68
  5098.8   18.08  5117.7   18.31  5163.8   16.32  5203.8   17.45  5213.8   18.13
  5223.8    19.3  5228.8   20.49  5243.8   28.41  5258.8   30.08  5281.2   29.99
#Mann= 4 , 1 , 0
  4553.8      .1       0    4992     .04       0  5033.8     .14       0
  5117.7     .07       0
Bank Sta=4944.6,5063.8
XS Rating Curve= 0
Exp/Cntr=.5,.3

Type RM Length L Ch R = 1 ,28255.5 ,23,23,23
BEGIN DESCRIPTION:
Upstream Section of Bridge/Culvert/Weir
END DESCRIPTION:
XS GIS Cut Line= 4
      3187952.24     13849041.23      3187565.49      13849537.9
      3187495.23     13849628.12      3187304.55     13849685.77
#Sta/Elev= 26
  4370.2   24.82    4373   25.18  4423.7   22.43  4426.8   22.43  4460.5   21.83
  4500.4   21.13  4553.7   20.18  4686.1   19.87  4816.9   17.96  4883.8   15.81
  4933.6   13.66  4936.7   13.66  4962.9   14.98  4993.7    3.51    4995    1.41
  5003.6    2.01  5006.2    3.68  5030.9   13.78  5031.3   13.79  5064.3    14.5
  5067.4    14.5  5155.2   16.05  5196.6   16.46    5248   17.86  5274.2    25.6
  5313.2   34.71
#Mann= 6 , 1 , 0
  4370.2      .2       0  4460.5     .07       0  4500.4      .1       0
  4962.9     .04       0  5030.9      .1       0  5031.3     .07       0
#XS Ineff= 2 , 0
       0    4935    13.6    5065       0    14.4
Permanent Ineff=
       F       F
Bank Sta=4962.9,5030.9
XS Rating Curve= 0
Exp/Cntr=.5,.3

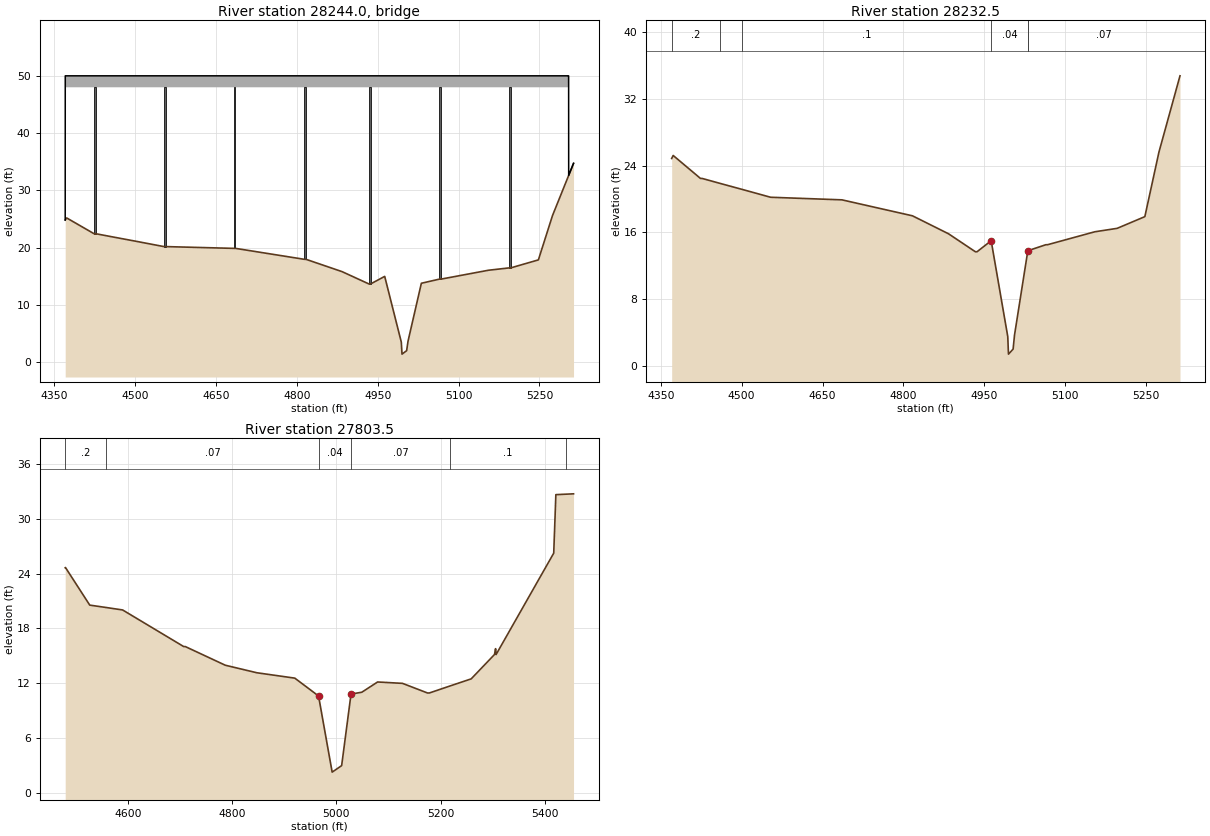
Type RM Length L Ch R = 3 ,28244.0 ,,,
BEGIN DESCRIPTION:
Cross Section 28244-Flyover Piers
Located At: FRONTAGE ROAD EAST
END DESCRIPTION:
Bridge Culvert--1,0,-1,-1, 0
Deck Dist Width WeirC Skew NumUp NumDn MinLoCord MaxHiCord MaxSubmerge Is_Ogee
10,3,2.6,0, 40, 40, , , .95, 0, 1,1,,
  4370.2  4370.3 4370.41  4370.5  4370.6    4373  4423.7  4426.8  4460.5  4500.4
    4545  4553.7  4556.8    4683  4686.1  4813.8  4816.9  4883.8  4933.6  4936.7
  4962.9  4993.7    4995  5003.6  5006.2  5030.9  5031.3  5064.3  5067.4  5073.5
  5155.2  5193.5  5196.6    5248  5274.2  5303.9 5303.99  5304.1  5304.2  5313.2
   24.83      50      50      50      50      50      50      50      50      50
      50      50      50      50      50      50      50      50      50      50
      50      50      50      50      50      50      50      50      50      50
      50      50      50      50      50      50      50      50   32.62   34.72
   24.83   24.84   24.86      48      48      48      48      48      48      48
      48      48      48      48      48      48      48      48      48      48
      48      48      48      48      48      48      48      48      48      48
      48      48      48      48      48      48      48   32.59   32.62   34.72
  4370.2  4370.3 4370.41  4370.5  4370.6    4373  4423.7  4426.8  4460.5  4500.4
    4545  4553.7  4556.8    4683  4686.1  4813.8  4816.9  4883.8  4933.6  4936.7
  4962.9  4993.7    4995  5003.6  5006.2  5030.9  5031.3  5064.3  5067.4  5073.5
  5155.2  5193.5  5196.6    5248  5274.2  5303.9 5303.99  5304.1  5304.2  5313.2
   24.83      50      50      50      50      50      50      50      50      50
      50      50      50      50      50      50      50      50      50      50
      50      50      50      50      50      50      50      50      50      50
      50      50      50      50      50      50      50      50   32.62   34.72
   24.83   24.84   24.86      48      48      48      48      48      48      48
      48      48      48      48      48      48      48      48      48      48
      48      48      48      48      48      48      48      48      48      48
      48      48      48      48      48      48      48   32.59   32.62   34.72
Pier Skew, UpSta & Num, DnSta & Num=  ,4425.2, 2 ,4425.2, 2 , 0 , 0 , 0 ,,
       3       3
   21.44      49
       3       3
   21.44      49
Pier Skew, UpSta & Num, DnSta & Num=  ,4555.2, 2 ,4555.2, 2 , 0 , 0 , 0 ,,
       3       3
   19.19      49
       3       3
   19.19      49
Pier Skew, UpSta & Num, DnSta & Num=  ,4684.5, 2 ,4684.5, 2 , 0 , 0 , 0 ,,
       3       3
   18.88      49
       3       3
   18.88      49
Pier Skew, UpSta & Num, DnSta & Num=  ,4815.3, 2 ,4815.3, 2 , 0 , 0 , 0 ,,
       3       3
   16.97      49
       3       3
   16.97      49
Pier Skew, UpSta & Num, DnSta & Num=  ,4935.1, 2 ,4935.1, 2 , 0 , 0 , 0 ,,
       3       3
   12.67      49
       3       3
   12.67      49
Pier Skew, UpSta & Num, DnSta & Num=  ,5065.8, 2 ,5065.8, 2 , 0 , 0 , 0 ,,
       3       3
   13.51      49
       3       3
   13.51      49
Pier Skew, UpSta & Num, DnSta & Num=  ,5195, 2 ,5195, 2 , 0 , 0 , 0 ,,
       3       3
   15.47      49
       3       3
   15.47      49
BR Coef= 1 , 1 , 0 ,1.25, 0 ,,,.8,0,2,0,
WSPro=,,,, 1 ,,,, 0 ,,,, 0 ,,,,-1 ,-1 ,-1 , 0 , 0 , 0 , 0 , 0
BR U #Sta/Elev= 40
  4370.2   24.83  4370.3   24.84 4370.41   24.86  4370.5   24.87  4370.6   24.88
    4373   25.19  4423.7   22.44  4426.8   22.44  4460.5   21.84  4500.4   21.14
    4545   20.34  4553.7   20.19  4556.8   20.19    4683   19.88  4686.1   19.88
  4813.8   17.97  4816.9   17.97  4883.8   15.82  4933.6   13.67  4936.7   13.67
  4962.9   14.99  4993.7    3.52    4995    1.42  5003.6    2.02  5006.2    3.69
  5030.9   13.79  5031.3    13.8  5064.3   14.51  5067.4   14.51  5073.5   14.62
  5155.2   16.06  5193.5   16.47  5196.6   16.47    5248   17.87  5274.2   25.61
  5303.9   32.55 5303.99   32.57  5304.1   32.59  5304.2   32.62  5313.2   34.72
BR U #Mann= 6
  4370.2      .2  4460.5     .07  4500.4      .1  4962.9     .04  5030.9      .1
  5031.3     .07
BR U Banks=4962.9,5030.9
BR D #Sta/Elev= 40
  4370.2   24.83  4370.3   24.84 4370.41   24.86  4370.5   24.87  4370.6   24.88
    4373   25.19  4423.7   22.44  4426.8   22.44  4460.5   21.84  4500.4   21.14
    4545   20.34  4553.7   20.19  4556.8   20.19    4683   19.88  4686.1   19.88
  4813.8   17.97  4816.9   17.97  4883.8   15.82  4933.6   13.67  4936.7   13.67
  4962.9   14.99  4993.7    3.52    4995    1.42  5003.6    2.02  5006.2    3.69
  5030.9   13.79  5031.3    13.8  5064.3   14.51  5067.4   14.51  5073.5   14.62
  5155.2   16.06  5193.5   16.47  5196.6   16.47    5248   17.87  5274.2   25.61
  5303.9   32.55 5303.99   32.57  5304.1   32.59  5304.2   32.62  5313.2   34.72
BR D #Mann= 6
  4370.2      .2  4460.5     .07  4500.4      .1  4962.9     .04  5030.9      .1
  5031.3     .07
BR D Banks=4962.9,5030.9
BC Design=,, 0 ,, 0 ,,,,,,
BC HTab HWMax=34.71

Type RM Length L Ch R = 1 ,28232.5 ,429,429,429
BEGIN DESCRIPTION:
Downstream Section of Bridge/Culvert/Weir
END DESCRIPTION:
XS GIS Cut Line= 4
      3187937.87     13849023.27      3187551.13     13849519.94
      3187480.87     13849610.16      3187290.19     13849667.81
#Sta/Elev= 26
  4370.2   24.85    4373   25.21  4423.7   22.46  4426.8   22.46  4460.5   21.86
  4500.4   21.16  4553.7   20.21  4686.1    19.9  4816.9   17.99  4883.8   15.84
  4933.6   13.69  4936.7   13.69  4962.9   15.01  4993.7    3.54    4995    1.44
  5003.6    2.04  5006.2    3.71  5030.9   13.81  5031.3   13.82  5064.3   14.53
  5067.4   14.53  5155.2   16.08  5196.6   16.49    5248   17.89  5274.2   25.63
  5313.2   34.74
#Mann= 6 , 1 , 0
  4370.2      .2       0  4460.5     .07       0  4500.4      .1       0
  4962.9     .04       0  5030.9      .1       0  5031.3     .07       0
#XS Ineff= 2 , 0
       0    4935    13.6    5065       0    14.4
Permanent Ineff=
       F       F
Bank Sta=4962.9,5030.9
XS Rating Curve= 0
Exp/Cntr=.5,.3

Type RM Length L Ch R = 1 ,27803.5 ,23,23,23
BEGIN DESCRIPTION:
Upstream Section of Bridge/Culvert/Weir
END DESCRIPTION:
XS GIS Cut Line= 4
      3187570.56     13848738.72      3187415.11     13848936.56
      3187294.65     13849177.48      3187091.39       13849584.
#Sta/Elev= 28
  4479.7   24.63  4480.2   24.66  4526.8   20.55  4558.1   20.29  4589.9   20.02
  4707.1   16.02  4710.2   16.02    4787   13.98  4847.3   13.16  4920.3   12.57
  4965.9   10.62    4992     2.3  5010.2    3.01  5028.2   10.83  5048.9   11.03
  5079.2   12.15  5126.9      12  5174.9   10.95  5178.6   10.95    5219   11.73
  5258.8   12.49  5303.5   15.15  5305.6   15.79  5306.6   15.15  5417.2   26.23
  5421.3   32.62  5440.1   32.67  5455.2   32.71
#Mann= 6 , 1 , 0
  4479.7      .2       0  4558.1     .07       0  4965.9     .04       0
  5028.2     .07       0    5219      .1       0  5440.1      .2       0
#XS Ineff= 2 , 0
       0    4918    12.5  5047.7       0    10.9
Permanent Ineff=
       F       F
Bank Sta=4965.9,5028.2
XS Rating Curve= 0
Exp/Cntr=.5,.3