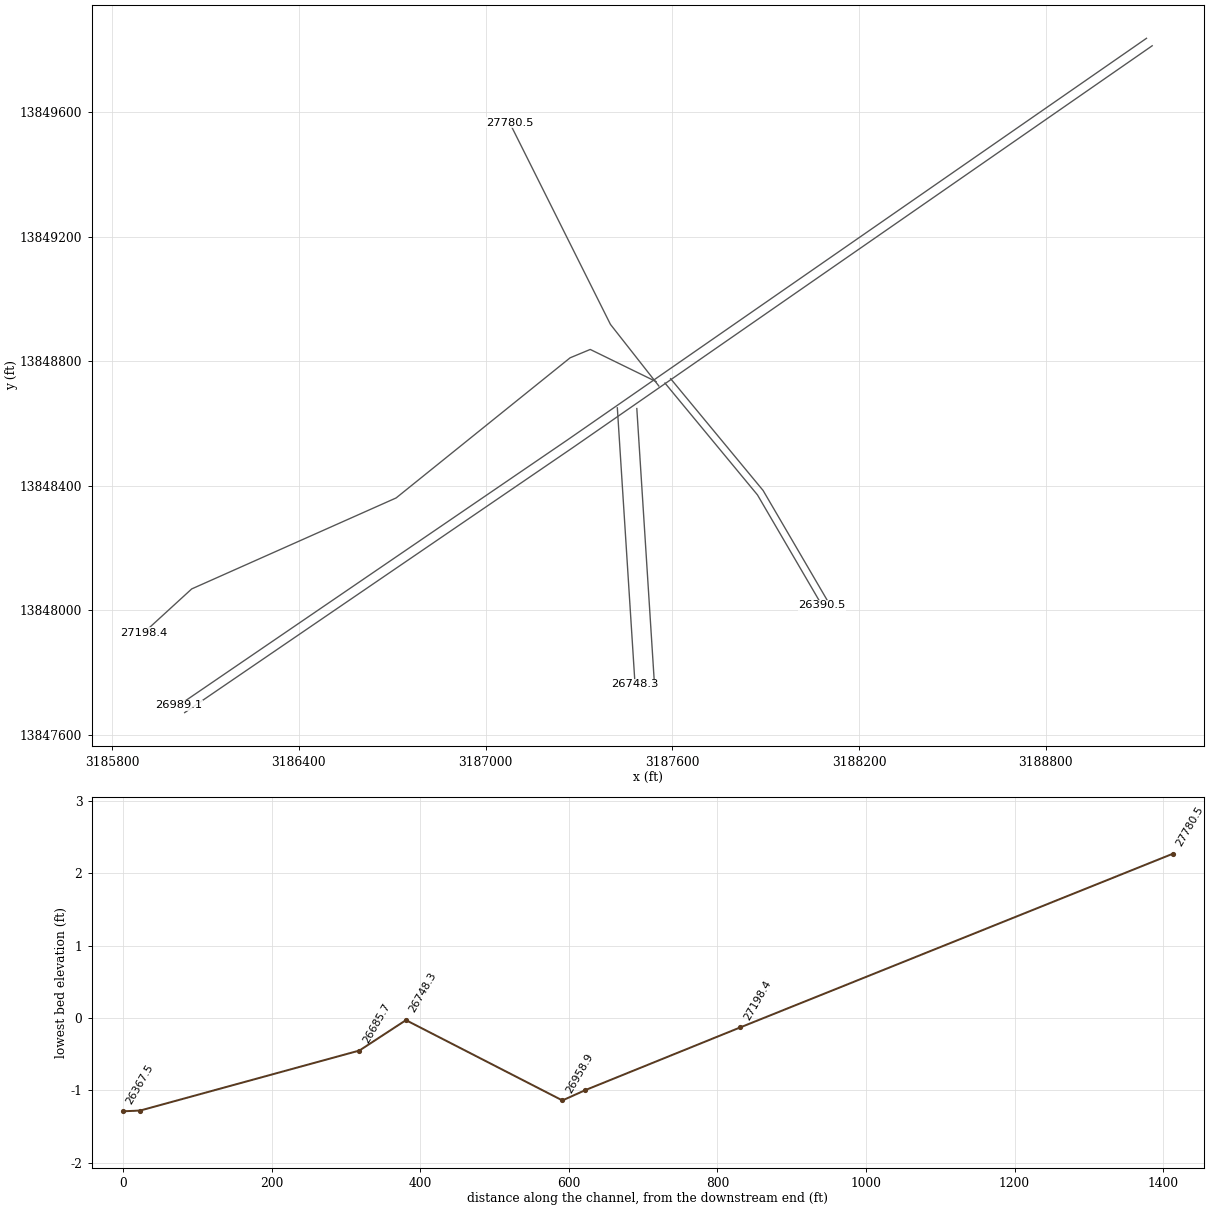
HEC-RAS study N100-00-00.prj: N100-00-00

--- N100-00-00.g01 (geometry) --- (continued)

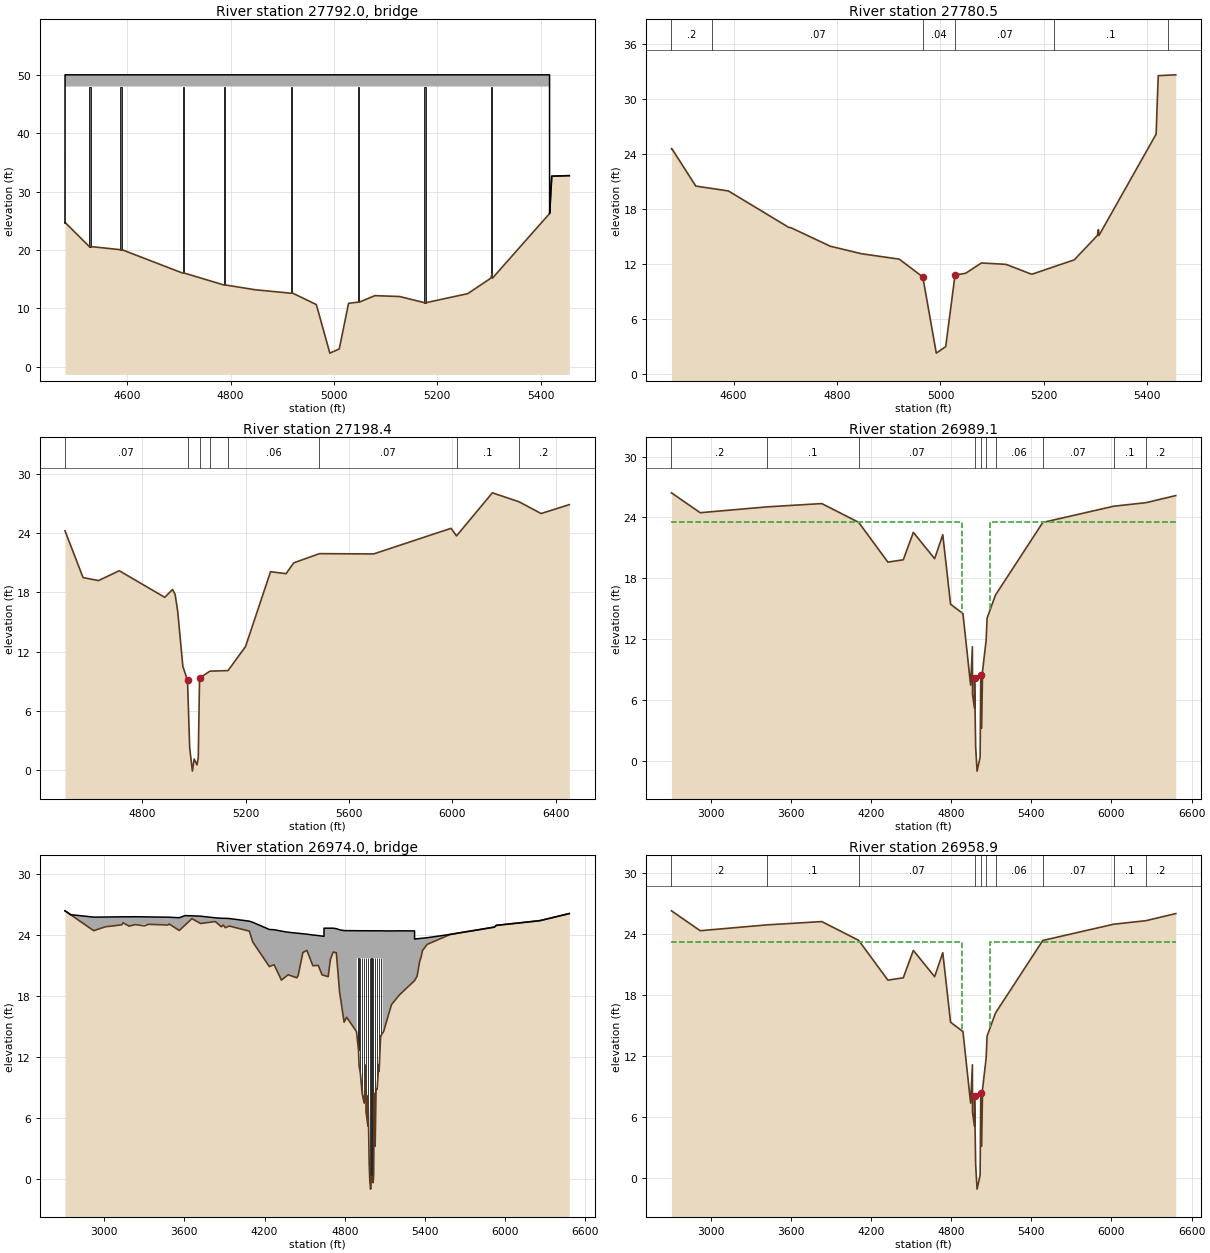
Type RM Length L Ch R = 3 ,27792.0 ,,,
BEGIN DESCRIPTION:
Cross Section 27792-Flyover Piers
Located At: FRONTAGE WEST N00-20
END DESCRIPTION:
Bridge Culvert--1,0,-1,-1, 0
Deck Dist Width WeirC Skew NumUp NumDn MinLoCord MaxHiCord MaxSubmerge Is_Ogee
10,3,2.6,0, 45, 45, , , .95, 0, 1,1,,
  4479.7  4479.8 4479.91    4480  4480.1  4480.2  4526.8  4529.9  4558.1  4586.8
  4589.9  4648.1  4707.1  4710.2    4787  4790.1  4847.3  4916.2  4920.3  4965.9
  4989.7    4992  5010.2  5028.2  5045.8  5048.9  5079.2  5126.9  5174.9  5176.6
    5178  5178.6    5219  5258.8  5303.5  5305.6  5306.6    5417  5417.1  5417.2
 5417.29  5417.4  5421.3  5440.1  5455.2
   24.65      50      50      50      50      50      50      50      50      50
      50      50      50      50      50      50      50      50      50      50
      50      50      50      50      50      50      50      50      50      50
      50      50      50      50      50      50      50      50   26.24   26.25
   26.39   26.56   32.64   32.69   32.73
   24.65   24.66   24.66   24.67      48      48      48      48      48      48
      48      48      48      48      48      48      48      48      48      48
      48      48      48      48      48      48      48      48      48      48
      48      48      48      48      48      48      48      48   26.24   26.25
   26.39   26.56   32.64   32.69   32.73
  4479.7  4479.8 4479.91    4480  4480.1  4480.2  4526.8  4529.9  4558.1  4586.8
  4589.9  4648.1  4707.1  4710.2    4787  4790.1  4847.3  4916.2  4920.3  4965.9
  4989.7    4992  5010.2  5028.2  5045.8  5048.9  5079.2  5126.9  5174.9  5176.6
    5178  5178.6    5219  5258.8  5303.5  5305.6  5306.6    5417  5417.1  5417.2
 5417.29  5417.4  5421.3  5440.1  5455.2
   24.65      50      50      50      50      50      50      50      50      50
      50      50      50      50      50      50      50      50      50      50
      50      50      50      50      50      50      50      50      50      50
      50      50      50      50      50      50      50      50   26.24   26.25
   26.39   26.56   32.64   32.69   32.73
   24.64   24.65   24.65   24.66   47.99   47.99   47.99   47.99   47.99   47.99
   47.99   47.99   47.99   47.99   47.99   47.99   47.99   47.99   47.99   47.99
   47.99   47.99   47.99   47.99   47.99   47.99   47.99   47.99   47.99   47.99
   47.99   47.99   47.99   47.99   47.99   47.99   47.99   47.99   26.23   26.24
   26.38   26.55   32.63   32.68   32.72
Pier Skew, UpSta & Num, DnSta & Num=  ,4528.3, 2 ,4528.3, 2 , 0 , 0 , 0 ,,
       3       3
   19.57      49
       3       3
   19.56   48.99
Pier Skew, UpSta & Num, DnSta & Num=  ,4588.3, 2 ,4588.3, 2 , 0 , 0 , 0 ,,
       3       3
   19.04      49
       3       3
   19.03   48.99
Pier Skew, UpSta & Num, DnSta & Num=  ,4708.6, 2 ,4708.6, 2 , 0 , 0 , 0 ,,
       3       3
   15.04      49
       3       3
   15.03   48.99
Pier Skew, UpSta & Num, DnSta & Num=  ,4788.5, 2 ,4788.5, 2 , 0 , 0 , 0 ,,
       3       3
      13      49
       3       3
   12.99   48.99
Pier Skew, UpSta & Num, DnSta & Num=  ,4917.7, 2 ,4917.7, 2 , 0 , 0 , 0 ,,
       3       3
   11.59      49
       3       3
   11.58   48.99
Pier Skew, UpSta & Num, DnSta & Num=  ,5047.3, 2 ,5047.3, 2 , 0 , 0 , 0 ,,
       3       3
   10.05      49
       3       3
   10.04   48.99
Pier Skew, UpSta & Num, DnSta & Num=  ,5176.4, 2 ,5176.4, 2 , 0 , 0 , 0 ,,
       3       3
    9.97      49
       3       3
    9.96   48.99
Pier Skew, UpSta & Num, DnSta & Num=  ,5305, 2 ,5305, 2 , 0 , 0 , 0 ,,
       3       3
   14.17      49
       3       3
   14.16   48.99
BR Coef= 1 , 1 , 0 ,1.25, 0 ,,,.8,0,2,0,
WSPro=,,,, 1 ,,,, 0 ,,,, 0 ,,,,-1 ,-1 ,-1 , 0 , 0 , 0 , 0 , 0
BR U #Sta/Elev= 45
  4479.7   24.65  4479.8   24.66 4479.91   24.66    4480   24.67  4480.1   24.67
  4480.2   24.68  4526.8   20.57  4529.9   20.57  4558.1   20.31  4586.8   20.04
  4589.9   20.04  4648.1   18.05  4707.1   16.04  4710.2   16.04    4787      14
  4790.1      14  4847.3   13.18  4916.2   12.59  4920.3   12.59  4965.9   10.64
  4989.7    3.06    4992    2.32  5010.2    3.03  5028.2   10.85  5045.8   11.05
  5048.9   11.05  5079.2   12.17  5126.9   12.02  5174.9   10.97  5176.6   10.97
    5178   10.97  5178.6   10.97    5219   11.75  5258.8   12.51  5303.5   15.17
  5305.6   15.81  5306.6   15.17    5417   26.23  5417.1   26.24  5417.2   26.25
 5417.29   26.39  5417.4   26.56  5421.3   32.64  5440.1   32.69  5455.2   32.73
BR U #Mann= 6
  4479.7      .2  4558.1     .07  4965.9     .04  5028.2     .07    5219      .1
  5440.1      .2
BR U Banks=4965.9,5028.2
BR D #Sta/Elev= 45
  4479.7   24.64  4479.8   24.65 4479.91   24.65    4480   24.66  4480.1   24.66
  4480.2   24.67  4526.8   20.56  4529.9   20.56  4558.1    20.3  4586.8   20.03
  4589.9   20.03  4648.1   18.04  4707.1   16.03  4710.2   16.03    4787   13.99
  4790.1   13.99  4847.3   13.17  4916.2   12.58  4920.3   12.58  4965.9   10.63
  4989.7    3.05    4992    2.31  5010.2    3.02  5028.2   10.84  5045.8   11.04
  5048.9   11.04  5079.2   12.16  5126.9   12.01  5174.9   10.96  5176.6   10.96
    5178   10.96  5178.6   10.96    5219   11.74  5258.8    12.5  5303.5   15.16
  5305.6    15.8  5306.6   15.16    5417   26.22  5417.1   26.23  5417.2   26.24
 5417.29   26.38  5417.4   26.55  5421.3   32.63  5440.1   32.68  5455.2   32.72
BR D #Mann= 6
  4479.7      .2  4558.1     .07  4965.9     .04  5028.2     .07    5219      .1
  5440.1      .2
BR D Banks=4965.9,5028.2
BC Design=,, 0 ,, 0 ,,,,,,
BC HTab HWMax=32.71

Type RM Length L Ch R = 1 ,27780.5 ,582.1,582.1,582.1
BEGIN DESCRIPTION:
Downstream Section of Bridge/Culvert/Weir
END DESCRIPTION:
XS GIS Cut Line= 4
      3187556.79     13848720.29      3187401.35     13848918.14
      3187280.89     13849159.06      3187077.63     13849565.58
#Sta/Elev= 28
  4479.7    24.6  4480.2   24.63  4526.8   20.52  4558.1   20.26  4589.9   19.99
  4707.1   15.99  4710.2   15.99    4787   13.95  4847.3   13.13  4920.3   12.54
  4965.9   10.59    4992    2.27  5010.2    2.98  5028.2    10.8  5048.9      11
  5079.2   12.12  5126.9   11.97  5174.9   10.92  5178.6   10.92    5219    11.7
  5258.8   12.46  5303.5   15.12  5305.6   15.76  5306.6   15.12  5417.2    26.2
  5421.3   32.59  5440.1   32.64  5455.2   32.68
#Mann= 6 , 1 , 0
  4479.7      .2       0  4558.1     .07       0  4965.9     .04       0
  5028.2     .07       0    5219      .1       0  5440.1      .2       0
#XS Ineff= 2 , 0
       0    4918    12.5  5047.7       0    10.9
Permanent Ineff=
       F       F
Bank Sta=4965.9,5028.2
XS Rating Curve= 0
Exp/Cntr=.5,.3

Type RM Length L Ch R = 1 ,27198.4 ,159.5,209.3,155.1
BEGIN DESCRIPTION:
Cross Section 27198.4 - Interpolated
END DESCRIPTION:
XS GIS Cut Line= 6
      3187548.11      13848734.3      3187336.47      13848837.6
       3187271.8     13848810.74      3186712.77     13848360.54
      3186056.17     13848068.35      3185901.86     13847927.18
#Sta/Elev= 30
  4500.6   24.25  4570.6    19.5  4630.6    19.2  4710.6    20.2  4886.9    17.5
  4916.9    18.3  4926.9    17.8  4936.9    16.1  4956.9    10.5    4975    9.08
  4983.3    2.27  4993.8    -.13  5000.7     1.1  5011.7      .5  5016.6    1.24
  5021.6    9.31  5061.6   10.01  5131.9   10.07  5199.5    12.5  5296.5    20.1
  5356.5    19.9  5386.5      21  5485.9   21.93  5695.4    21.9  5995.4    24.5
  6016.5   23.73  6155.4    28.1  6258.7   27.19    6344      26  6453.2    26.9
#Mann= 8 , 1 , 0
  4500.6     .07       0    4975     .04       0  5021.6     .13       0
  5061.6     .07       0  5131.9     .06       0  5485.9     .07       0
  6016.5      .1       0  6258.7      .2       0
Bank Sta=4975,5021.6
XS Rating Curve= 0
Exp/Cntr=.5,.3

Type RM Length L Ch R = 1 ,26989.1 ,30.2,30.2,30.2
BEGIN DESCRIPTION:
Upstream Section of Bridge/Culvert/Weir
END DESCRIPTION:
XS GIS Cut Line= 3
      3189123.46     13849837.12      3187263.51     13848547.14
      3186015.18     13847694.92
#Sta/Elev= 30
  2706.2   26.43  2921.2   24.47  3424.7   25.05  3831.4   25.37  4107.6   23.52
  4326.4    19.6  4441.4   19.83  4516.9   22.53  4676.2   19.94  4737.2    22.3
  4795.5   15.45  4888.2   14.53  4945.6    7.48  4958.9   11.25  4959.8    6.59
    4974    5.22    4975    8.21  4983.3     1.4  4993.8      -1  5016.6     .37
  5021.6    8.44  5027.9    3.24  5034.9    8.85  5061.6    11.9  5068.9   14.08
  5131.9   16.36  5485.9   23.51  6016.5   25.11  6258.7   25.46  6481.2   26.16
#Mann= 10 , 1 , 0
  2706.2      .2       0  3424.7      .1       0  4107.6     .07       0
    4975     .04       0  5021.6     .13       0  5061.6     .07       0
  5131.9     .06       0  5485.9     .07       0  6016.5      .1       0
  6258.7      .2       0
#XS Ineff= 2 , 0
       0    4880    23.6    5093       0    23.6
Permanent Ineff=
       F       F
Bank Sta=4975,5021.6
XS Rating Curve= 0
Exp/Cntr=.5,.3

Type RM Length L Ch R = 3 ,26974.0 ,,,
BEGIN DESCRIPTION:
Missouri Pacific Railroad
Structure ID: N00-19
END DESCRIPTION:
Bridge Culvert--1,0,-1,-1, 0
Deck Dist Width WeirC Skew NumUp NumDn MinLoCord MaxHiCord MaxSubmerge Is_Ogee
10,10.2,2.6,0, 60, 60, , , .95, 0, 1,1,,
  2706.2  2749.3  2921.2  3006.2  3131.2  3141.2  3186.2  3231.4  3486.4  3561.4
  3604.7  3656.4  3721.4  3831.4  3876.4  3891.4  3906.4  3936.4  4086.4  4111.4
  4236.4  4271.4  4326.4  4376.4  4441.4  4451.4  4486.9  4516.9  4561.9  4601.9
  4630.6 4645.09  4645.2  4676.2  4692.9  4713.8  4737.2  4761.6  4795.5  4814.4
  4888.2 4890.91    4891 5083.39  5083.5  5091.7    5150  5209.4  5322.9 5323.01
  5341.9  5361.9  5371.9  5381.9  5416.9  5590.1  5920.1  5935.1  6260.8  6481.2
   26.39   26.01   25.77   25.78    25.8    25.8    25.8   25.81   25.76   25.71
   25.92    25.9   25.86    25.7   25.66   25.65   25.65   25.63   25.37   25.26
   24.55   24.53   24.39   24.28   24.19   24.18   24.13   24.09   24.01   23.95
    23.9   23.88   24.68   24.68   24.68   24.68   24.63   24.52   24.44   24.44
   24.43   24.43   24.43   24.42   24.42   24.41   24.41   24.42   24.41   23.61
   23.64   23.66   23.68   23.69   23.74   24.07   24.79   24.96   25.42   26.12
   26.39      26   24.43   24.81   25.01   25.21   24.88   25.03   25.09   24.45
   24.98   25.62   25.14   25.33   24.82   24.99   24.73   24.89   24.39   23.32
   20.89   21.08   19.56   20.09   19.79      20   22.28   22.49   20.98   21.01
   20.07   20.02   20.02    19.9    21.6   22.33   22.26   18.39   15.41    15.9
   14.49   14.16   21.73   21.72   14.33    14.5   17.14    18.1   19.52   19.52
   19.93   21.45   21.83   22.46   23.08   24.06   24.78   24.95   25.42   26.12
  2706.2  2749.3  2921.2  3006.2  3131.2  3141.2  3186.2  3231.4  3486.4  3561.4
  3604.7  3656.4  3721.4  3831.4  3876.4  3891.4  3906.4  3936.4  4086.4  4111.4
  4236.4  4271.4  4326.4  4376.4  4441.4  4451.4  4486.9  4516.9  4561.9  4601.9
  4630.6 4645.09  4645.2  4676.2  4692.9  4713.8  4737.2  4761.6  4795.5  4814.4
  4888.2 4890.91    4891 5083.39  5083.5  5091.7    5150  5209.4  5322.9 5323.01
  5341.9  5361.9  5371.9  5381.9  5416.9  5590.1  5920.1  5935.1  6260.8  6481.2
   26.39   26.01   25.77   25.78    25.8    25.8    25.8   25.81   25.76   25.71
   25.92    25.9   25.86    25.7   25.66   25.65   25.65   25.63   25.37   25.26
   24.55   24.53   24.39   24.28   24.19   24.18   24.13   24.09   24.01   23.95
    23.9   23.88   24.68   24.68   24.68   24.68   24.63   24.52   24.44   24.44
   24.43   24.43   24.43   24.42   24.42   24.41   24.41   24.42   24.41   23.61
   23.64   23.66   23.68   23.69   23.74   24.07   24.79   24.96   25.42   26.12
   26.25   25.86   24.29   24.67   24.87   25.07   24.74   24.89   24.95   24.31
   24.84   25.48      25   25.19   24.68   24.85   24.59   24.75   24.25   23.18
   20.75   20.94   19.42   19.95   19.65   19.86   22.14   22.35   20.84   20.87
   19.93   19.88   19.88   19.76   21.46   22.19   22.12   18.25   15.27   15.76
   14.35   14.02   21.59   21.58   14.19   14.36      17   17.96   19.38   19.38
   19.79   21.31   21.69   22.32   22.94   23.92   24.64   24.81   25.28   25.98
Pier Skew, UpSta & Num, DnSta & Num=  ,4903.6, 2 ,4903.6, 2 , 0 , 0 , 0 ,,
     1.1     1.1
   11.42   22.73
     1.1     1.1
   11.28   22.59
Pier Skew, UpSta & Num, DnSta & Num=  ,4917.2, 2 ,4917.2, 2 , 0 , 0 , 0 ,,
     1.1     1.1
    9.29   22.73
     1.1     1.1
    9.15   22.59
Pier Skew, UpSta & Num, DnSta & Num=  ,4931, 2 ,4931, 2 , 0 , 0 , 0 ,,
     1.1     1.1
    7.33   22.73
     1.1     1.1
    7.19   22.59
Pier Skew, UpSta & Num, DnSta & Num=  ,4945.6, 2 ,4945.6, 2 , 0 , 0 , 0 ,,
     1.1     1.1
    6.47   22.73
     1.1     1.1
    6.33   22.59
Pier Skew, UpSta & Num, DnSta & Num=  ,4959.8, 2 ,4959.8, 2 , 0 , 0 , 0 ,,
     1.1     1.1
     5.5   22.73
     1.1     1.1
    5.36   22.59
Pier Skew, UpSta & Num, DnSta & Num=  ,4974, 2 ,4974, 2 , 0 , 0 , 0 ,,
     1.1     1.1
    4.23   22.72
     1.1     1.1
    4.09   22.58
Pier Skew, UpSta & Num, DnSta & Num=  ,4987.9, 2 ,4987.9, 2 , 0 , 0 , 0 ,,
     1.1     1.1
   -1.25   22.72
     1.1     1.1
   -1.39   22.58
Pier Skew, UpSta & Num, DnSta & Num=  ,5000.7, 2 ,5000.7, 2 , 0 , 0 , 0 ,,
     1.1     1.1
    -.91   22.72
     1.1     1.1
   -1.05   22.58
Pier Skew, UpSta & Num, DnSta & Num=  ,5014.2, 2 ,5014.2, 2 , 0 , 0 , 0 ,,
     1.1     1.1
   -1.22   22.72
     1.1     1.1
   -1.36   22.58
Pier Skew, UpSta & Num, DnSta & Num=  ,5027.9, 2 ,5027.9, 2 , 0 , 0 , 0 ,,
     1.1     1.1
    2.64   22.72
     1.1     1.1
     2.5   22.58
Pier Skew, UpSta & Num, DnSta & Num=  ,5042.5, 2 ,5042.5, 2 , 0 , 0 , 0 ,,
     1.1     1.1
     7.8   22.72
     1.1     1.1
    7.66   22.58
Pier Skew, UpSta & Num, DnSta & Num=  ,5055.3, 2 ,5055.3, 2 , 0 , 0 , 0 ,,
     1.1     1.1
   10.05   22.72
     1.1     1.1
    9.91   22.58
Pier Skew, UpSta & Num, DnSta & Num=  ,5068.9, 2 ,5068.9, 2 , 0 , 0 , 0 ,,
     1.1     1.1
   12.88   22.72
     1.1     1.1
   12.74   22.58
Abutment Skew #Up #Dn= , 2 , 2
  4890.8  4907.7
   21.73    11.1
  4890.8  4907.7
   21.59   10.96
Abutment Skew #Up #Dn= , 2 , 2
  5057.3 5083.59
   10.57   21.72
  5057.3 5083.59
   10.43   21.58
BR Coef= 1 , 1 , 0 ,1.25, 0 ,,,.8,0,2,0,
WSPro=,,,, 1 ,,,, 0 ,,,, 0 ,,,,-1 ,-1 ,-1 , 0 , 0 , 0 , 0 , 0
BR U #Sta/Elev= 133
  2706.2   26.39  2749.3      26  2921.2   24.43  3006.2   24.81  3066.2   24.91
  3131.2   25.01  3141.2   25.21  3186.2   24.88  3231.4   25.03  3301.4   24.91
  3331.4   25.06  3424.7   25.01  3459.7      25  3464.7      25  3476.4   24.99
  3479.7   25.02  3486.4   25.09  3534.7   24.68  3561.4   24.45  3564.7   24.49
  3589.7    24.8  3604.7   24.98  3629.7   25.29  3654.7    25.6  3656.4   25.62
  3704.7   25.26  3721.4   25.14  3759.7   25.21  3804.7   25.28  3831.4   25.33
  3844.7   25.18  3876.4   24.82  3891.4   24.99  3906.4   24.73  3936.4   24.89
  3944.7   24.86  4044.7   24.53  4086.4   24.39  4099.7   23.82  4107.6   23.48
  4111.4   23.32  4199.7    21.6  4236.4   20.89  4244.7   20.94  4264.7   21.04
  4271.4   21.08  4284.7   20.71  4326.4   19.56  4376.4   20.09  4389.7   20.03
  4441.4   19.79  4451.4      20  4464.7   20.85  4486.9   22.28  4516.9   22.49
  4561.9   20.98  4601.9   21.01  4630.6   20.07 4645.09   20.02  4645.2   20.02
 4645.31   20.02  4676.2    19.9  4692.9    21.6  4713.8   22.33  4724.9    22.3
  4737.2   22.26  4761.6   18.39    4781   16.68  4795.5   15.41  4814.4    15.9
  4888.2   14.49 4890.91   14.16    4891   14.15  4903.6   12.63  4907.6   11.11
  4907.7    11.1  4917.2   10.37    4931    8.36  4945.6    7.44  4958.9   11.21
  4959.8    6.55    4974    5.18    4975    8.17  4983.3    1.36  4987.9    -.17
  4993.8   -1.04  5000.7     .19  5003.3     .11  5011.7    -.41  5014.2    -.16
  5016.6     .33  5021.6     8.4  5027.9     3.2  5034.9    8.81  5042.5     8.8
  5055.3   11.23  5057.2    10.6  5057.3   10.57  5061.6   11.86  5068.9   14.04
 5083.39   14.33  5083.5   14.33  5091.7    14.5  5131.9   16.32  5147.4   17.02
    5150   17.14  5205.4   18.04  5209.4    18.1  5262.2   18.76  5265.8    18.8
  5321.1   19.48 5322.79   19.52  5322.9   19.52 5323.01   19.52  5341.9   19.93
  5361.9   21.45  5371.9   21.83  5381.9   22.46  5416.9   23.08  5485.9   23.47
  5590.1   24.06  5629.8   24.15  5684.8   24.27  5709.8   24.32  5784.8   24.48
  5909.8   24.76  5920.1   24.78  5935.1   24.95  6016.5   25.07  6258.7   25.42
  6259.1   25.42  6260.8   25.42  6481.2   26.12
BR U #Mann= 10
  2706.2      .2  3424.7      .1  4107.6     .07    4975     .04  5021.6     .13
  5061.6     .07  5131.9     .06  5485.9     .07  6016.5      .1  6258.7      .2
BR U Banks=4975,5021.6
BR D #Sta/Elev= 133
  2706.2   26.25  2749.3   25.86  2921.2   24.29  3006.2   24.67  3066.2   24.77
  3131.2   24.87  3141.2   25.07  3186.2   24.74  3231.4   24.89  3301.4   24.77
  3331.4   24.92  3424.7   24.87  3459.7   24.86  3464.7   24.86  3476.4   24.85
  3479.7   24.88  3486.4   24.95  3534.7   24.54  3561.4   24.31  3564.7   24.35
  3589.7   24.66  3604.7   24.84  3629.7   25.15  3654.7   25.46  3656.4   25.48
  3704.7   25.12  3721.4      25  3759.7   25.07  3804.7   25.14  3831.4   25.19
  3844.7   25.04  3876.4   24.68  3891.4   24.85  3906.4   24.59  3936.4   24.75
  3944.7   24.72  4044.7   24.39  4086.4   24.25  4099.7   23.68  4107.6   23.34
  4111.4   23.18  4199.7   21.46  4236.4   20.75  4244.7    20.8  4264.7    20.9
  4271.4   20.94  4284.7   20.57  4326.4   19.42  4376.4   19.95  4389.7   19.89
  4441.4   19.65  4451.4   19.86  4464.7   20.71  4486.9   22.14  4516.9   22.35
  4561.9   20.84  4601.9   20.87  4630.6   19.93 4645.09   19.88  4645.2   19.88
 4645.31   19.88  4676.2   19.76  4692.9   21.46  4713.8   22.19  4724.9   22.16
  4737.2   22.12  4761.6   18.25    4781   16.54  4795.5   15.27  4814.4   15.76
  4888.2   14.35 4890.91   14.02    4891   14.01  4903.6   12.49  4907.6   10.97
  4907.7   10.96  4917.2   10.23    4931    8.22  4945.6     7.3  4958.9   11.07
  4959.8    6.41    4974    5.04    4975    8.03  4983.3    1.22  4987.9    -.31
  4993.8   -1.18  5000.7     .05  5003.3    -.03  5011.7    -.55  5014.2     -.3
  5016.6     .19  5021.6    8.26  5027.9    3.06  5034.9    8.67  5042.5    8.66
  5055.3   11.09  5057.2   10.46  5057.3   10.43  5061.6   11.72  5068.9    13.9
 5083.39   14.19  5083.5   14.19  5091.7   14.36  5131.9   16.18  5147.4   16.88
    5150      17  5205.4    17.9  5209.4   17.96  5262.2   18.62  5265.8   18.66
  5321.1   19.34 5322.79   19.38  5322.9   19.38 5323.01   19.38  5341.9   19.79
  5361.9   21.31  5371.9   21.69  5381.9   22.32  5416.9   22.94  5485.9   23.33
  5590.1   23.92  5629.8   24.01  5684.8   24.13  5709.8   24.18  5784.8   24.34
  5909.8   24.62  5920.1   24.64  5935.1   24.81  6016.5   24.93  6258.7   25.28
  6259.1   25.28  6260.8   25.28  6481.2   25.98
BR D #Mann= 10
  2706.2      .2  3424.7      .1  4107.6     .07    4975     .04  5021.6     .13
  5061.6     .07  5131.9     .06  5485.9     .07  6016.5      .1  6258.7      .2
BR D Banks=4975,5021.6
BC Design=,, 0 ,, 0 ,,,,,,
BC HTab HWMax=26.43

Type RM Length L Ch R = 1 ,26958.9 ,210.6,210.6,210.6
BEGIN DESCRIPTION:
Downstream Section of Bridge/Culvert/Weir
END DESCRIPTION:
XS GIS Cut Line= 3
      3189141.79     13849813.12      3187281.83     13848523.14
      3186033.51     13847670.92
#Sta/Elev= 30
  2706.2   26.29  2921.2   24.33  3424.7   24.91  3831.4   25.23  4107.6   23.38
  4326.4   19.46  4441.4   19.69  4516.9   22.39  4676.2    19.8  4737.2   22.16
  4795.5   15.31  4888.2   14.39  4945.6    7.34  4958.9   11.11  4959.8    6.45
    4974    5.08    4975    8.07  4983.3    1.26  4993.8   -1.14  5016.6     .23
  5021.6     8.3  5027.9     3.1  5034.9    8.71  5061.6   11.76  5068.9   13.94
  5131.9   16.22  5485.9   23.37  6016.5   24.97  6258.7   25.32  6481.2   26.02
#Mann= 10 , 1 , 0
  2706.2      .2       0  3424.7      .1       0  4107.6     .07       0
    4975     .04       0  5021.6     .13       0  5061.6     .07       0
  5131.9     .06       0  5485.9     .07       0  6016.5      .1       0
  6258.7      .2       0
#XS Ineff= 2 , 0
       0    4880    23.2    5093       0    23.2
Permanent Ineff=
       F       F
Bank Sta=4975,5021.6
XS Rating Curve= 0
Exp/Cntr=.5,.3

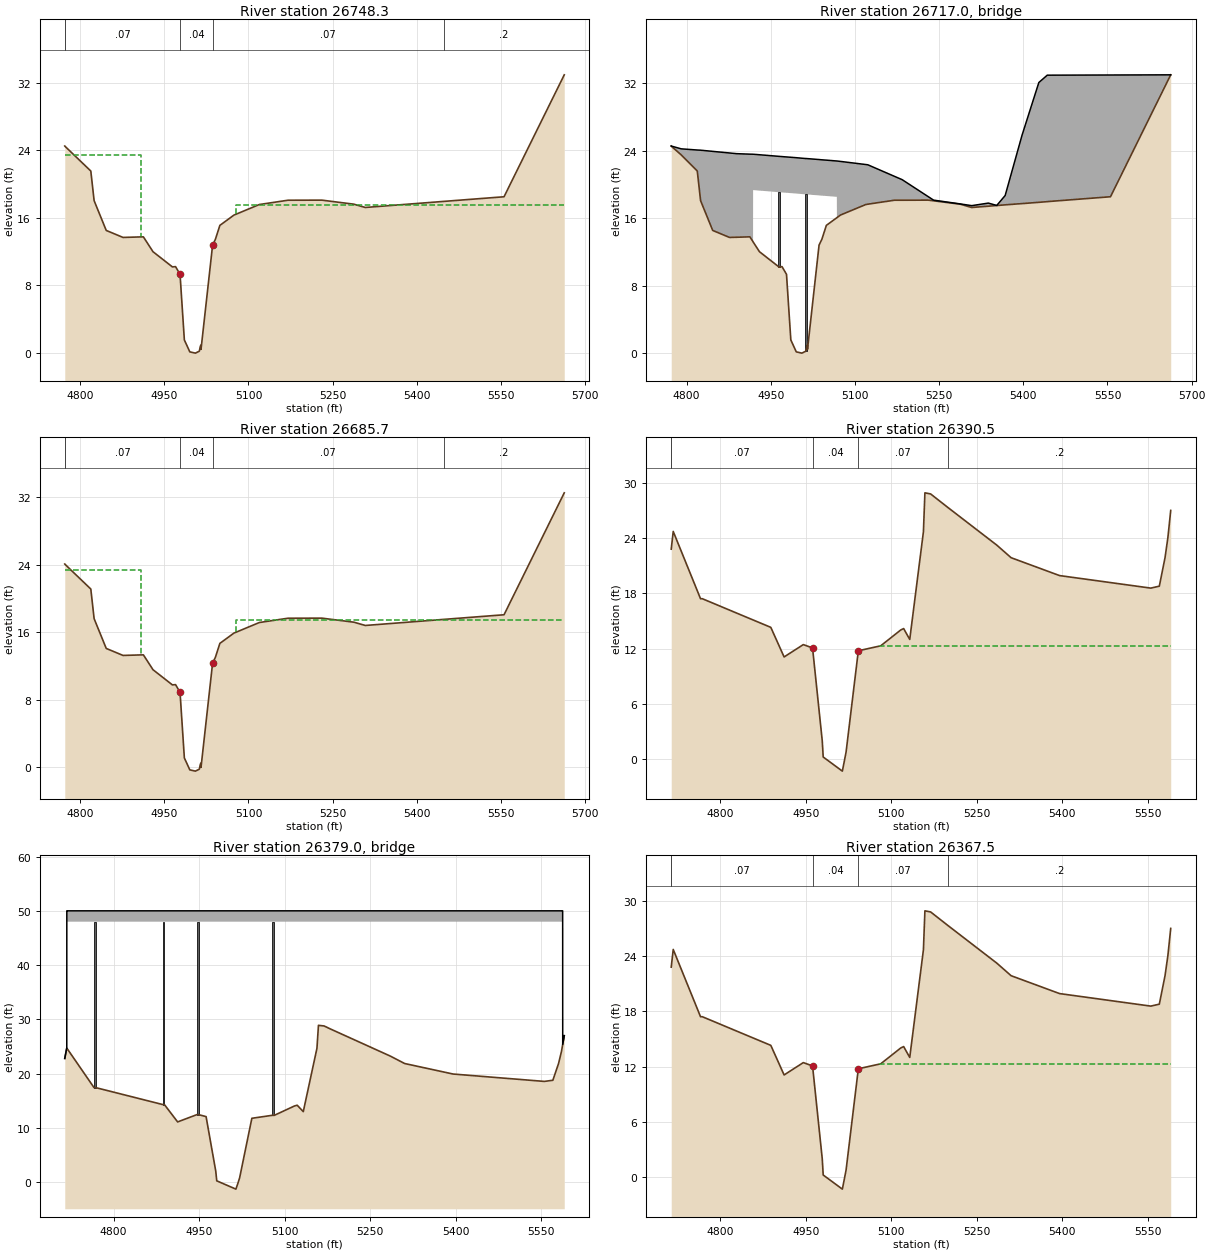
Type RM Length L Ch R = 1 ,26748.3 ,62.6,62.6,62.6
BEGIN DESCRIPTION:
Upstream Section of Bridge/Culvert/Weir
END DESCRIPTION:
XS GIS Cut Line= 3
      3187423.53     13848650.03      3187438.14     13848421.63
      3187480.36     13847761.86
#Sta/Elev= 30
  4772.7   24.51  4772.8    24.5  4819.1   21.55    4825   18.04  4846.6   14.51
  4876.5   13.68  4912.8   13.75  4929.9   11.99  4964.5   10.19  4970.1   10.22
  4978.1    9.31  4985.8    1.53  4995.5     .12  5005.5    -.03  5012.5      .2
  5014.1     .73  5015.1     .91  5015.5     .42  5036.1   12.77  5041.1   13.46
  5049.1   15.11  5074.2   16.33  5119.4   17.58  5170.5   18.09  5230.7    18.1
  5287.8   17.62  5308.3   17.23  5447.8   17.95  5555.4    18.5  5662.7   32.95
#Mann= 5 , 1 , 0
  4772.7      .2       0  4772.8     .07       0  4978.1     .04       0
  5036.1     .07       0  5447.8      .2       0
#XS Ineff= 2 , 0
       0    4908    23.5    5078       0    17.5
Permanent Ineff=
       F       F
Bank Sta=4978.1,5036.1
XS Rating Curve= 0
Exp/Cntr=.5,.3

Type RM Length L Ch R = 3 ,26717.0 ,,,
BEGIN DESCRIPTION:
Ramp from Belt to I-10W
Structure ID: N00-18
END DESCRIPTION:
Bridge Culvert--1,0,-1,-1, 0
Deck Dist Width WeirC Skew NumUp NumDn MinLoCord MaxHiCord MaxSubmerge Is_Ogee
10,42.6,2.6,0, 57, 57, , , .95, 0, 1,1,,
  4772.7  4772.8  4774.3    4790  4790.4  4819.1    4825  4826.5  4846.6  4876.5
  4888.6  4912.8 4918.17 4918.28 4918.39 4918.51  4918.6  4929.9  4964.5  4970.1
  4978.1  4985.7  4985.8  4995.5  5005.5  5012.5  5014.1    5015  5015.1  5015.5
  5036.1  5041.1  5049.1 5067.46 5067.57 5067.68 5067.79  5067.9  5074.2  5119.4
    5123  5170.5  5184.1  5230.7  5240.2  5287.8  5307.9  5308.3  5337.7  5352.7
  5367.7  5397.7  5427.7  5442.7  5447.8  5555.4  5662.7
   24.56   24.56   24.53   24.24   24.23   24.09   24.07   24.06   23.93   23.74
   23.66    23.6   23.59   23.59   23.59   23.59   23.59   23.53   23.34   23.31
   23.27   23.23   23.23   23.18   23.12   23.08   23.08   23.07   23.07   23.07
   22.96   22.93   22.89   22.79   22.79   22.79   22.79   22.79   22.74   22.37
   22.34   20.97   20.58   18.56   18.15    17.7    17.5    17.5    17.8   17.52
    18.7   25.83   32.09   32.96   32.96   32.98      33
   24.56   24.55   24.45   23.54   23.51    21.6   18.09   17.84   14.56   13.73
   13.75    13.8   13.25   13.24   13.22   13.21   19.34   19.28   19.09   19.06
   19.02   18.98   18.98   18.93   18.87   18.83   18.83   18.82   18.82   18.82
   18.71   18.68   18.64   18.54   18.54   18.54   18.54   16.07   16.38   17.63
   17.67   18.14   18.14   18.15   18.07   17.67   17.28   17.28   17.43   17.51
   17.59   17.74   17.89   17.97      18   18.55      33
  4772.7  4772.8  4774.3    4790  4790.4  4819.1    4825  4826.5  4846.6  4876.5
  4888.6  4912.8 4918.17 4918.28 4918.39 4918.51  4918.6  4929.9  4964.5  4970.1
  4978.1  4985.7  4985.8  4995.5  5005.5  5012.5  5014.1    5015  5015.1  5015.5
  5036.1  5041.1  5049.1 5067.46 5067.57 5067.68 5067.79  5067.9  5074.2  5119.4
    5123  5170.5  5184.1  5230.7  5240.2  5287.8  5307.9  5308.3  5337.7  5352.7
  5367.7  5397.7  5427.7  5442.7  5447.8  5555.4  5662.7
   24.56   24.56   24.53   24.24   24.23   24.09   24.07   24.06   23.93   23.74
   23.66    23.6   23.59   23.59   23.59   23.59   23.59   23.53   23.34   23.31
   23.27   23.23   23.23   23.18   23.12   23.08   23.08   23.07   23.07   23.07
   22.96   22.93   22.89   22.79   22.79   22.79   22.79   22.79   22.74   22.37
   22.34   20.97   20.58   18.56   18.15    17.7    17.5    17.5    17.8   17.52
    18.7   25.83   32.09   32.96   32.96   32.98      33
   24.12   24.11   24.01    23.1   23.07   21.16   17.65    17.4   14.12   13.29
   13.31   13.36   12.81    12.8   12.78   12.77    18.9   18.84   18.65   18.62
   18.58   18.54   18.54   18.49   18.43   18.39   18.39   18.38   18.38   18.38
   18.27   18.24    18.2    18.1    18.1    18.1    18.1   15.63   15.94   17.19
   17.23    17.7    17.7   17.71   17.63   17.23   16.84   16.84   16.99   17.07
   17.15    17.3   17.45   17.53   17.56   18.11   32.56
Pier Skew, UpSta & Num, DnSta & Num=  ,4964.5, 2 ,4964.5, 2 , 0 , 0 , 0 ,,
     2.5     2.5
    9.25    20.1
     2.5     2.5
    8.81   19.66
Pier Skew, UpSta & Num, DnSta & Num=  ,5012.5, 2 ,5012.5, 2 , 0 , 0 , 0 ,,
     2.5     2.5
    -.79   19.84
     2.5     2.5
   -1.23    19.4
Abutment Skew #Up #Dn= , 2 , 2
  4918.4  4985.8
   19.34    1.58
  4918.4  4985.8
    18.9    1.14
Abutment Skew #Up #Dn= , 2 , 2
  5015.1 5067.99
     .96   18.54
  5015.1 5067.99
     .52    18.1
BR Coef= 1 , 1 , 0 ,1.25, 0 ,,,.8,0,2,0,
WSPro=,,,, 1 ,,,, 0 ,,,, 0 ,,,,-1 ,-1 ,-1 , 0 , 0 , 0 , 0 , 0
BR U #Sta/Elev= 57
  4772.7   24.56  4772.8   24.55  4774.3   24.45    4790   23.54  4790.4   23.51
  4819.1    21.6    4825   18.09  4826.5   17.84  4846.6   14.56  4876.5   13.73
  4888.6   13.75  4912.8    13.8 4918.17   13.25 4918.28   13.24 4918.39   13.22
 4918.51   13.21  4918.6    13.2  4929.9   12.04  4964.5   10.24  4970.1   10.27
  4978.1    9.36  4985.7    1.68  4985.8    1.58  4995.5     .17  5005.5     .02
  5012.5     .25  5014.1     .78    5015     .94  5015.1     .96  5015.5     .47
  5036.1   12.82  5041.1   13.51  5049.1   15.16 5067.46   16.05 5067.57   16.06
 5067.68   16.06 5067.79   16.07  5067.9   16.07  5074.2   16.38  5119.4   17.63
    5123   17.67  5170.5   18.14  5184.1   18.14  5230.7   18.15  5240.2   18.07
  5287.8   17.67  5307.9   17.28  5308.3   17.28  5337.7   17.43  5352.7   17.51
  5367.7   17.59  5397.7   17.74  5427.7   17.89  5442.7   17.97  5447.8      18
  5555.4   18.55  5662.7      33
BR U #Mann= 5
  4772.7      .2  4772.8     .07  4978.1     .04  5036.1     .07  5447.8      .2
BR U Banks=4978.1,5036.1
BR D #Sta/Elev= 57
  4772.7   24.12  4772.8   24.11  4774.3   24.01    4790    23.1  4790.4   23.07
  4819.1   21.16    4825   17.65  4826.5    17.4  4846.6   14.12  4876.5   13.29
  4888.6   13.31  4912.8   13.36 4918.17   12.81 4918.28    12.8 4918.39   12.78
 4918.51   12.77  4918.6   12.76  4929.9    11.6  4964.5     9.8  4970.1    9.83
  4978.1    8.92  4985.7    1.24  4985.8    1.14  4995.5    -.27  5005.5    -.42
  5012.5    -.19  5014.1     .34    5015      .5  5015.1     .52  5015.5     .03
  5036.1   12.38  5041.1   13.07  5049.1   14.72 5067.46   15.61 5067.57   15.62
 5067.68   15.62 5067.79   15.63  5067.9   15.63  5074.2   15.94  5119.4   17.19
    5123   17.23  5170.5    17.7  5184.1    17.7  5230.7   17.71  5240.2   17.63
  5287.8   17.23  5307.9   16.84  5308.3   16.84  5337.7   16.99  5352.7   17.07
  5367.7   17.15  5397.7    17.3  5427.7   17.45  5442.7   17.53  5447.8   17.56
  5555.4   18.11  5662.7   32.56
BR D #Mann= 5
  4772.7      .2  4772.8     .07  4978.1     .04  5036.1     .07  5447.8      .2
BR D Banks=4978.1,5036.1
BC Design=,, 0 ,, 0 ,,,,,,
BC HTab HWMax=32.95

Type RM Length L Ch R = 1 ,26685.7 ,295.2,295.2,295.2
BEGIN DESCRIPTION:
Downstream Section of Bridge/Culvert/Weir
END DESCRIPTION:
XS GIS Cut Line= 3
      3187486.09     13848647.71       3187500.7     13848419.31
      3187542.91     13847759.54
#Sta/Elev= 30
  4772.7   24.09  4772.8   24.08  4819.1   21.13    4825   17.62  4846.6   14.09
  4876.5   13.26  4912.8   13.33  4929.9   11.57  4964.5    9.77  4970.1     9.8
  4978.1    8.89  4985.8    1.11  4995.5     -.3  5005.5    -.45  5012.5    -.22
  5014.1     .31  5015.1     .49  5015.5       0  5036.1   12.35  5041.1   13.04
  5049.1   14.69  5074.2   15.91  5119.4   17.16  5170.5   17.67  5230.7   17.68
  5287.8    17.2  5308.3   16.81  5447.8   17.53  5555.4   18.08  5662.7   32.53
#Mann= 5 , 1 , 0
  4772.7      .2       0  4772.8     .07       0  4978.1     .04       0
  5036.1     .07       0  5447.8      .2       0
#XS Ineff= 2 , 0
       0    4908    23.4    5078       0    17.5
Permanent Ineff=
       F       F
Bank Sta=4978.1,5036.1
XS Rating Curve= 0
Exp/Cntr=.5,.3

Type RM Length L Ch R = 1 ,26390.5 ,23,23,23
BEGIN DESCRIPTION:
Upstream Section of Bridge/Culvert/Weir
END DESCRIPTION:
XS GIS Cut Line= 4
      3187576.53      13848729.6      3187758.73     13848509.33
      3187873.65      13848370.4      3188080.47     13848016.36
#Sta/Elev= 30
  4714.2   22.81  4714.3   22.86  4717.7   24.73  4765.6   17.43  4768.7   17.43
  4888.9   14.32  4912.2   11.11  4945.9   12.45  4962.1   12.09  4979.1    2.02
  4980.8     .25  5014.4   -1.28  5020.9     .78  5042.4   11.78  5081.7   12.32
  5116.9   14.04  5121.9   14.19  5132.6   13.01  5156.6    24.7  5159.2   28.92
  5169.2    28.8  5199.3   27.34  5285.4   23.24  5310.4   21.88  5395.4   19.94
  5555.4   18.58  5570.4   18.79  5580.4   21.88  5585.4   24.05  5590.4   27.01
#Mann= 5 , 1 , 0
  4714.2      .2       0  4714.3     .07       0  4962.1     .04       0
  5042.4     .07       0  5199.3      .2       0
#XS Ineff= 2 , 0
       0    4947    12.4    5079       0    12.3
Permanent Ineff=
       F       F
Bank Sta=4962.1,5042.4
XS Rating Curve= 0
Exp/Cntr=.5,.3

Type RM Length L Ch R = 3 ,26379.0 ,,,
BEGIN DESCRIPTION:
Cross Section 26379-Flyover Piers
Located At: FRONTAGE WEST N00-14
END DESCRIPTION:
Bridge Culvert--1,0,-1,-1, 0
Deck Dist Width WeirC Skew NumUp NumDn MinLoCord MaxHiCord MaxSubmerge Is_Ogee
10,3,2.6,0, 45, 45, , , .95, 0, 1,1,,
  4714.2  4714.3  4717.7  4717.8 4717.91    4718  4718.1  4765.6  4768.7  4885.8
  4886.9  4888.9  4912.2  4945.9    4949  4962.1  4979.1  4980.8  5014.4  5017.9
  5020.9  5042.4  5077.6  5081.7  5116.9  5121.9  5132.6  5156.6  5159.2  5169.2
  5180.4  5199.3  5285.4  5310.4  5395.4  5415.4  5555.4  5570.4  5580.4  5585.4
  5587.4 5587.49  5587.6  5587.7  5590.4
   22.78   22.83    24.7      50      50      50      50      50      50      50
      50      50      50      50      50      50      50      50      50      50
      50      50      50      50      50      50      50      50      50      50
      50      50      50      50      50      50      50      50      50      50
      50      50      50   25.38   26.98
   22.78   22.83    24.7   24.68   24.67      48      48      48      48      48
      48      48      48      48      48      48      48      48      48      48
      48      48      48      48      48      48      48      48      48      48
      48      48      48      48      48      48      48      48      48      48
      48      48   25.32   25.38   26.98
  4714.2  4714.3  4717.7  4717.8 4717.91    4718  4718.1  4765.6  4768.7  4885.8
  4886.9  4888.9  4912.2  4945.9    4949  4962.1  4979.1  4980.8  5014.4  5017.9
  5020.9  5042.4  5077.6  5081.7  5116.9  5121.9  5132.6  5156.6  5159.2  5169.2
  5180.4  5199.3  5285.4  5310.4  5395.4  5415.4  5555.4  5570.4  5580.4  5585.4
  5587.4 5587.49  5587.6  5587.7  5590.4
   22.78   22.83    24.7      50      50      50      50      50      50      50
      50      50      50      50      50      50      50      50      50      50
      50      50      50      50      50      50      50      50      50      50
      50      50      50      50      50      50      50      50      50      50
      50      50      50   25.38   26.98
   22.78   22.83    24.7   24.68   24.67      48      48      48      48      48
      48      48      48      48      48      48      48      48      48      48
      48      48      48      48      48      48      48      48      48      48
      48      48      48      48      48      48      48      48      48      48
      48      48   25.32   25.38   26.98
Pier Skew, UpSta & Num, DnSta & Num=  ,4767.1, 2 ,4767.1, 2 , 0 , 0 , 0 ,,
       3       3
    16.4      49
       3       3
    16.4      49
Pier Skew, UpSta & Num, DnSta & Num=  ,4887.3, 2 ,4887.3, 2 , 0 , 0 , 0 ,,
       3       3
   13.29      49
       3       3
   13.29      49
Pier Skew, UpSta & Num, DnSta & Num=  ,4947.4, 2 ,4947.4, 2 , 0 , 0 , 0 ,,
       3       3
   11.42      49
       3       3
   11.42      49
Pier Skew, UpSta & Num, DnSta & Num=  ,5079.1, 2 ,5079.1, 2 , 0 , 0 , 0 ,,
       3       3
   11.29      49
       3       3
   11.29      49
BR Coef= 1 , 1 , 0 ,1.25, 0 ,,,.8,0,2,0,
WSPro=,,,, 1 ,,,, 0 ,,,, 0 ,,,,-1 ,-1 ,-1 , 0 , 0 , 0 , 0 , 0
BR U #Sta/Elev= 45
  4714.2   22.78  4714.3   22.83  4717.7    24.7  4717.8   24.68 4717.91   24.67
    4718   24.65  4718.1   24.64  4765.6    17.4  4768.7    17.4  4885.8   14.29
  4886.9   14.29  4888.9   14.29  4912.2   11.08  4945.9   12.42    4949   12.42
  4962.1   12.06  4979.1    1.99  4980.8     .22  5014.4   -1.31  5017.9    -.24
  5020.9     .75  5042.4   11.75  5077.6   12.29  5081.7   12.29  5116.9   14.01
  5121.9   14.16  5132.6   12.98  5156.6   24.67  5159.2   28.89  5169.2   28.77
  5180.4   28.21  5199.3   27.31  5285.4   23.21  5310.4   21.85  5395.4   19.91
  5415.4   19.74  5555.4   18.55  5570.4   18.76  5580.4   21.85  5585.4   24.02
  5587.4    25.2 5587.49   25.26  5587.6   25.32  5587.7   25.38  5590.4   26.98
BR U #Mann= 5
  4714.2      .2  4714.3     .07  4962.1     .04  5042.4     .07  5199.3      .2
BR U Banks=4962.1,5042.4
BR D #Sta/Elev= 45
  4714.2   22.78  4714.3   22.83  4717.7    24.7  4717.8   24.68 4717.91   24.67
    4718   24.65  4718.1   24.64  4765.6    17.4  4768.7    17.4  4885.8   14.29
  4886.9   14.29  4888.9   14.29  4912.2   11.08  4945.9   12.42    4949   12.42
  4962.1   12.06  4979.1    1.99  4980.8     .22  5014.4   -1.31  5017.9    -.24
  5020.9     .75  5042.4   11.75  5077.6   12.29  5081.7   12.29  5116.9   14.01
  5121.9   14.16  5132.6   12.98  5156.6   24.67  5159.2   28.89  5169.2   28.77
  5180.4   28.21  5199.3   27.31  5285.4   23.21  5310.4   21.85  5395.4   19.91
  5415.4   19.74  5555.4   18.55  5570.4   18.76  5580.4   21.85  5585.4   24.02
  5587.4    25.2 5587.49   25.26  5587.6   25.32  5587.7   25.38  5590.4   26.98
BR D #Mann= 5
  4714.2      .2  4714.3     .07  4962.1     .04  5042.4     .07  5199.3      .2
BR D Banks=4962.1,5042.4
BC Design=,, 0 ,, 0 ,,,,,,
BC HTab HWMax=28.92

Type RM Length L Ch R = 1 ,26367.5 ,448,448,448
BEGIN DESCRIPTION:
Downstream Section of Bridge/Culvert/Weir
END DESCRIPTION:
XS GIS Cut Line= 4
      3187594.69     13848743.72      3187776.89     13848523.45
      3187891.81     13848384.52      3188098.62     13848030.48
#Sta/Elev= 30
  4714.2    22.8  4714.3   22.85  4717.7   24.72  4765.6   17.42  4768.7   17.42
  4888.9   14.31  4912.2    11.1  4945.9   12.44  4962.1   12.08  4979.1    2.01
  4980.8     .24  5014.4   -1.29  5020.9     .77  5042.4   11.77  5081.7   12.31
  5116.9   14.03  5121.9   14.18  5132.6      13  5156.6   24.69  5159.2   28.91
  5169.2   28.79  5199.3   27.33  5285.4   23.23  5310.4   21.87  5395.4   19.93
  5555.4   18.57  5570.4   18.78  5580.4   21.87  5585.4   24.04  5590.4      27
#Mann= 5 , 1 , 0
  4714.2      .2       0  4714.3     .07       0  4962.1     .04       0
  5042.4     .07       0  5199.3      .2       0
#XS Ineff= 2 , 0
       0    4947    12.4    5079       0    12.3
Permanent Ineff=
       F       F
Bank Sta=4962.1,5042.4
XS Rating Curve= 0
Exp/Cntr=.5,.3