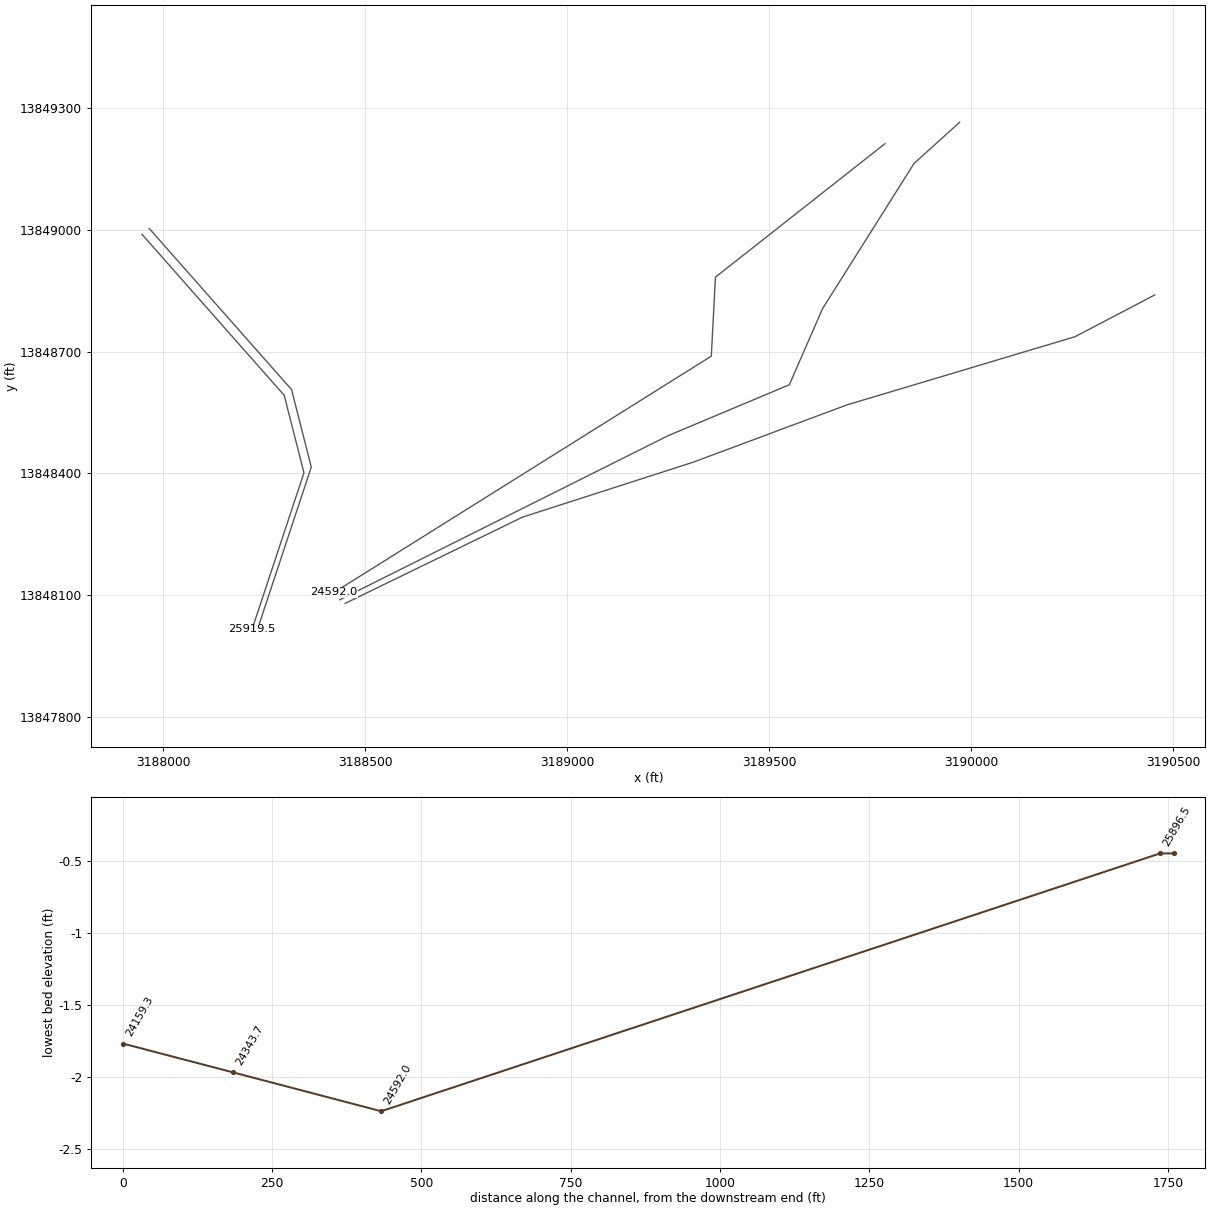
HEC-RAS study N100-00-00.prj: N100-00-00

--- N100-00-00.g01 (geometry) --- (continued)

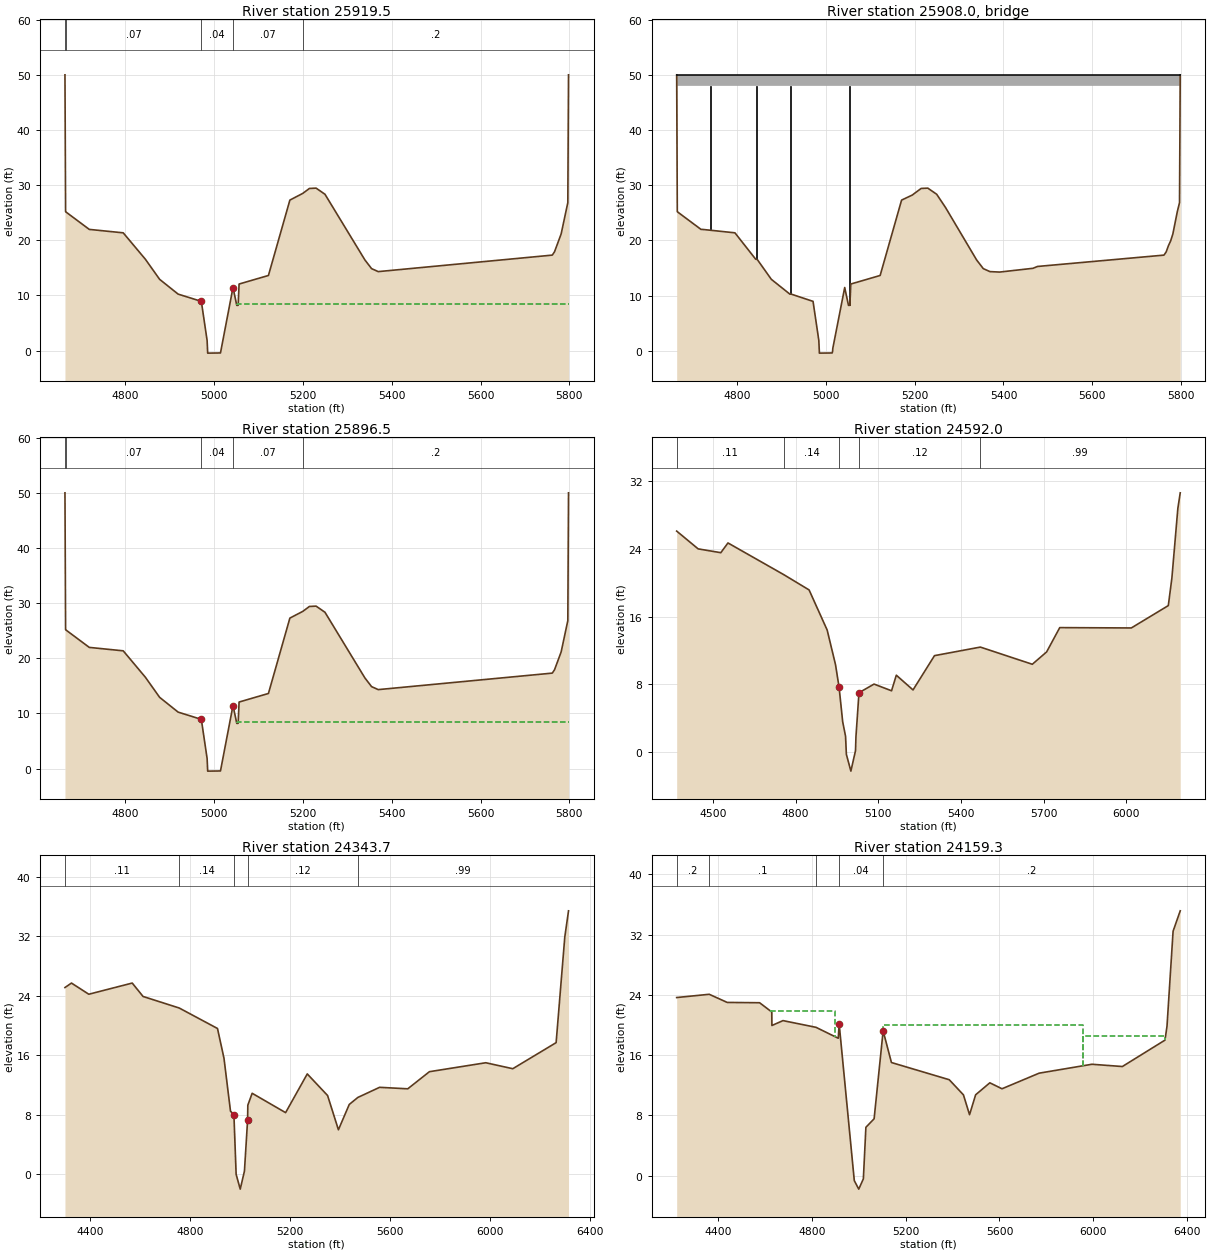
Type RM Length L Ch R = 1 ,25919.5 ,23,23,23
BEGIN DESCRIPTION:
Upstream Section of Bridge/Culvert/Weir
END DESCRIPTION:
XS GIS Cut Line= 5
      3187947.19     13848988.89      3188171.16     13848736.57
      3188299.38     13848592.12      3188348.16     13848401.44
      3188219.57     13848015.66
#Sta/Elev= 30
  4664.1   49.98  4665.5   25.17  4666.7    25.1  4718.9   21.97  4795.3   21.35
  4845.2   16.56  4877.3   12.92    4919   10.24  4971.2    8.93  4984.2    1.85
  4985.5    -.45  5014.3    -.42  5042.5   11.44    5051    8.21  5054.1    8.21
  5056.2   12.07  5122.3   13.62  5170.6   27.28  5199.7    28.5  5214.6   29.39
  5229.6   29.45  5249.6   28.34  5339.6   16.43  5354.6   14.86  5369.6   14.32
  5761.5   17.31  5766.5    17.9  5781.5   21.15  5796.5   26.82  5798.1   49.98
#Mann= 5 , 1 , 0
  4664.1      .2       0  4666.7     .07       0  4971.2     .04       0
  5042.5     .07       0  5199.7      .2       0
#XS Ineff= 2 , 0
       0    4920      10    5052       0     8.4
Permanent Ineff=
       F       F
Bank Sta=4971.2,5042.5
XS Rating Curve= 0
Exp/Cntr=.5,.3

Type RM Length L Ch R = 3 ,25908.0 ,,,
BEGIN DESCRIPTION:
Cross Section 25908-Flyover Piers
Located At: FRONTAGE EAST N00-10
END DESCRIPTION:
Bridge Culvert--1,0,-1,-1, 0
Deck Dist Width WeirC Skew NumUp NumDn MinLoCord MaxHiCord MaxSubmerge Is_Ogee
10,3,2.6,0, 51, 51, , , .95, 0, 1,1,,
  4664.1  4665.5 4666.01  4666.1  4666.2  4666.7  4718.9    4722  4795.3  4842.1
  4845.2  4877.3    4919  4922.1  4961.4  4971.2  4984.2  4985.5  5014.3  5015.2
  5015.7  5042.5    5051  5054.1  5056.2  5122.3  5170.6  5194.6  5199.7  5214.6
  5229.6  5249.6  5269.6  5339.6  5354.6  5369.6  5391.5  5466.5  5476.5  5489.9
  5761.5  5766.5  5771.5  5776.5  5781.5  5791.5  5796.5    5797 5797.09  5797.2
  5798.1
      50      50      50      50      50      50      50      50      50      50
      50      50      50      50      50      50      50      50      50      50
      50      50      50      50      50      50      50      50      50      50
      50      50      50      50      50      50      50      50      50      50
      50      50      50      50      50      50      50      50      50      50
      50
      50   25.19   25.16      48      48      48      48      48      48      48
      48      48      48      48      48      48      48      48      48      48
      48      48      48      48      48      48      48      48      48      48
      48      48      48      48      48      48      48      48      48      48
      48      48      48      48      48      48      48      48      48   36.97
      50
  4664.1  4665.5 4666.01  4666.1  4666.2  4666.7  4718.9    4722  4795.3  4842.1
  4845.2  4877.3    4919  4922.1  4961.4  4971.2  4984.2  4985.5  5014.3  5015.2
  5015.7  5042.5    5051  5054.1  5056.2  5122.3  5170.6  5194.6  5199.7  5214.6
  5229.6  5249.6  5269.6  5339.6  5354.6  5369.6  5391.5  5466.5  5476.5  5489.9
  5761.5  5766.5  5771.5  5776.5  5781.5  5791.5  5796.5    5797 5797.09  5797.2
  5798.1
      50      50      50      50      50      50      50      50      50      50
      50      50      50      50      50      50      50      50      50      50
      50      50      50      50      50      50      50      50      50      50
      50      50      50      50      50      50      50      50      50      50
      50      50      50      50      50      50      50      50      50      50
      50
      50   25.19   25.16      48      48      48      48      48      48      48
      48      48      48      48      48      48      48      48      48      48
      48      48      48      48      48      48      48      48      48      48
      48      48      48      48      48      48      48      48      48      48
      48      48      48      48      48      48      48      48      48   36.97
      50
Pier Skew, UpSta & Num, DnSta & Num=  ,4740.4, 2 ,4740.4, 2 , 0 , 0 , 0 ,,
       3       3
   20.82      49
       3       3
   20.82      49
Pier Skew, UpSta & Num, DnSta & Num=  ,4843.6, 2 ,4843.6, 2 , 0 , 0 , 0 ,,
       3       3
   15.58      49
       3       3
   15.58      49
Pier Skew, UpSta & Num, DnSta & Num=  ,4920.6, 2 ,4920.6, 2 , 0 , 0 , 0 ,,
       3       3
    9.26      49
       3       3
    9.26      49
Pier Skew, UpSta & Num, DnSta & Num=  ,5052.6, 2 ,5052.6, 2 , 0 , 0 , 0 ,,
       3       3
    7.23      49
       3       3
    7.23      49
BR Coef= 1 , 1 , 0 ,1.25, 0 ,,,.8,0,2,1,
WSPro=,,,, 1 ,,,, 0 ,,,, 0 ,,,,-1 ,-1 ,-1 , 0 , 0 , 0 , 0 , 0
BR U #Sta/Elev= 51
  4664.1      50  4665.5   25.19 4666.01   25.16  4666.1   25.15  4666.2   25.15
  4666.7   25.12  4718.9   21.99    4722   21.99  4795.3   21.37  4842.1   16.58
  4845.2   16.58  4877.3   12.94    4919   10.26  4922.1   10.26  4961.4    9.21
  4971.2    8.95  4984.2    1.87  4985.5    -.43  5014.3     -.4  5015.2    -.11
  5015.7     .43  5042.5   11.46    5051    8.23  5054.1    8.23  5056.2   12.09
  5122.3   13.64  5170.6    27.3  5194.6   28.21  5199.7   28.52  5214.6   29.41
  5229.6   29.47  5249.6   28.36  5269.6   25.95  5339.6   16.45  5354.6   14.88
  5369.6   14.34  5391.5   14.26  5466.5   14.94  5476.5   15.27  5489.9   15.37
  5761.5   17.33  5766.5   17.92  5771.5   19.03  5776.5    19.9  5781.5   21.17
  5791.5    25.2  5796.5   26.84    5797   34.08 5797.09   35.38  5797.2   36.97
  5798.1      50
BR U #Mann= 5
  4664.1      .2  4666.7     .07  4971.2     .04  5042.5     .07  5199.7      .2
BR U Banks=4971.2,5042.5
BR D #Sta/Elev= 51
  4664.1      50  4665.5   25.19 4666.01   25.16  4666.1   25.15  4666.2   25.15
  4666.7   25.12  4718.9   21.99    4722   21.99  4795.3   21.37  4842.1   16.58
  4845.2   16.58  4877.3   12.94    4919   10.26  4922.1   10.26  4961.4    9.21
  4971.2    8.95  4984.2    1.87  4985.5    -.43  5014.3     -.4  5015.2    -.11
  5015.7     .43  5042.5   11.46    5051    8.23  5054.1    8.23  5056.2   12.09
  5122.3   13.64  5170.6    27.3  5194.6   28.21  5199.7   28.52  5214.6   29.41
  5229.6   29.47  5249.6   28.36  5269.6   25.95  5339.6   16.45  5354.6   14.88
  5369.6   14.34  5391.5   14.26  5466.5   14.94  5476.5   15.27  5489.9   15.37
  5761.5   17.33  5766.5   17.92  5771.5   19.03  5776.5    19.9  5781.5   21.17
  5791.5    25.2  5796.5   26.84    5797   34.08 5797.09   35.38  5797.2   36.97
  5798.1      50
BR D #Mann= 5
  4664.1      .2  4666.7     .07  4971.2     .04  5042.5     .07  5199.7      .2
BR D Banks=4971.2,5042.5
BC Design=,, 0 ,, 0 ,,,,,,
BC HTab HWMax=49.98

Type RM Length L Ch R = 1 ,25896.5 ,1304.5,1304.5,1304.5
BEGIN DESCRIPTION:
Downstream Section of Bridge/Culvert/Weir
END DESCRIPTION:
XS GIS Cut Line= 5
      3187965.33     13849003.04       3188189.3     13848750.71
      3188317.52     13848606.26       3188366.3     13848415.58
      3188237.71      13848029.8
#Sta/Elev= 30
  4664.1   49.98  4665.5   25.17  4666.7    25.1  4718.9   21.97  4795.3   21.35
  4845.2   16.56  4877.3   12.92    4919   10.24  4971.2    8.93  4984.2    1.85
  4985.5    -.45  5014.3    -.42  5042.5   11.44    5051    8.21  5054.1    8.21
  5056.2   12.07  5122.3   13.62  5170.6   27.28  5199.7    28.5  5214.6   29.39
  5229.6   29.45  5249.6   28.34  5339.6   16.43  5354.6   14.86  5369.6   14.32
  5761.5   17.31  5766.5    17.9  5781.5   21.15  5796.5   26.82  5798.1   49.98
#Mann= 5 , 1 , 0
  4664.1      .2       0  4666.7     .07       0  4971.2     .04       0
  5042.5     .07       0  5199.7      .2       0
#XS Ineff= 2 , 0
       0    4920      10    5052       0     8.4
Permanent Ineff=
       F       F
Bank Sta=4971.2,5042.5
XS Rating Curve= 0
Exp/Cntr=.5,.3

Type RM Length L Ch R = 1 ,24592.0 ,275.4,248.3,115.8
BEGIN DESCRIPTION:
Cross Section 24592 - Skewed 30 Degrees
Located At: 1ST XS US IH-10
END DESCRIPTION:
XS GIS Cut Line= 4
      3189786.09     13849212.02      3189366.48     13848883.26
      3189356.24     13848688.72      3188422.77     13848106.97
#Sta/Elev= 30
 4368.08   26.11 4446.02   24.01 4528.29   23.56 4554.27   24.71  4756.6   20.97
 4848.71   19.16 4914.35   14.42 4944.66   10.33 4957.65    7.65 4970.64    3.59
  4981.1    1.87    4984    -.25  5000.4   -2.24  5017.2     .18  5018.8    1.83
  5029.8    7.02  5084.5    8.04    5148    7.25 5165.32    9.09 5225.94    7.35
 5303.88    11.4  5470.4   12.41 5658.94   10.38  5710.9   11.84 5758.53   14.71
 6018.33   14.67 6152.56   17.31 6165.55   20.56  6187.2   28.79 6195.86   30.63
#Mann= 5 , 1 , 0
 4368.08     .11       0  4756.6     .14       0 4957.65     .04       0
  5029.8     .12       0  5470.4     .99       0
Bank Sta=4957.65,5029.8
XS Rating Curve= 0
Exp/Cntr=.3,.1

Type RM Length L Ch R = 1 ,24343.7 ,179.6,184.4,219.6
BEGIN DESCRIPTION:
Cross Section 24343.7 - Interpolated  Skewed 30 Degrees
END DESCRIPTION:
XS GIS Cut Line= 6
      3189970.96     13849264.81      3189857.89     13849163.24
      3189631.37     13848805.39      3189549.29     13848618.26
      3189250.54      13848493.5      3188436.95     13848088.83
#Sta/Elev= 30
 4299.93    25.1 4325.91    25.7 4395.19    24.2 4568.73    25.7 4612.03    23.9
  4756.6   22.35  4909.5    19.6 4935.48    15.6 4961.46     8.5  4975.1    8.04
    4984     .02  5000.4   -1.97  5017.2     .45  5029.8    7.29 5030.74     9.3
 5048.06    10.9 5181.69     8.3 5268.29    13.5 5349.52    10.6 5392.82       6
 5436.12     9.4  5470.4   10.34 5557.36    11.7 5669.94    11.5 5756.54    13.8
  5981.7      15 6089.69    14.2 6262.89    17.7 6297.53    31.9 6312.42    35.4
#Mann= 5 , 1 , 0
 4299.93     .11       0  4756.6     .14       0  4975.1     .04       0
  5029.8     .12       0  5470.4     .99       0
Bank Sta=4975.1,5029.8
XS Rating Curve= 0
Exp/Cntr=.5,.3

Type RM Length L Ch R = 1 ,24159.3 ,66.6,66.6,66.6
BEGIN DESCRIPTION:
Upstream Section of Bridge/Culvert/Weir
END DESCRIPTION:
XS GIS Cut Line= 6
      3190453.69     13848839.52      3190256.24     13848736.59
      3189691.01      13848568.4      3189312.51     13848427.99
      3188889.16     13848292.39      3188450.17      13848079.9
#Sta/Elev= 30
 4222.51   23.64  4361.3   24.07 4438.31   22.99 4576.44   22.95  4628.4   21.72
  4628.9   19.93  4676.2   20.58    4817   19.69  4912.2   18.24  4915.8   20.18
  4980.5    -.64  4999.5   -1.77  5019.2    -.41    5030    6.43  5065.1    7.56
  5103.6   19.22    5139   15.02 5385.72   12.74 5446.34   10.73 5472.32     8.1
  5498.3   10.74 5558.92   12.33 5610.88   11.54 5769.44   13.61  5994.6   14.79
  6124.5   14.49 6306.36   17.99 6315.02   19.84    6341   32.44 6371.48   35.14
#Mann= 5 , 1 , 0
 4222.51      .2       0  4361.3      .1       0    4817     .07       0
  4915.8     .04       0  5103.6      .2       0
#XS Ineff= 3 ,-1
    4620    4897    21.8    5103    5956      20    5957    6305    18.5
Permanent Ineff=
       F       F       F
Bank Sta=4915.8,5103.6
XS Rating Curve= 0
Exp/Cntr=.5,.3