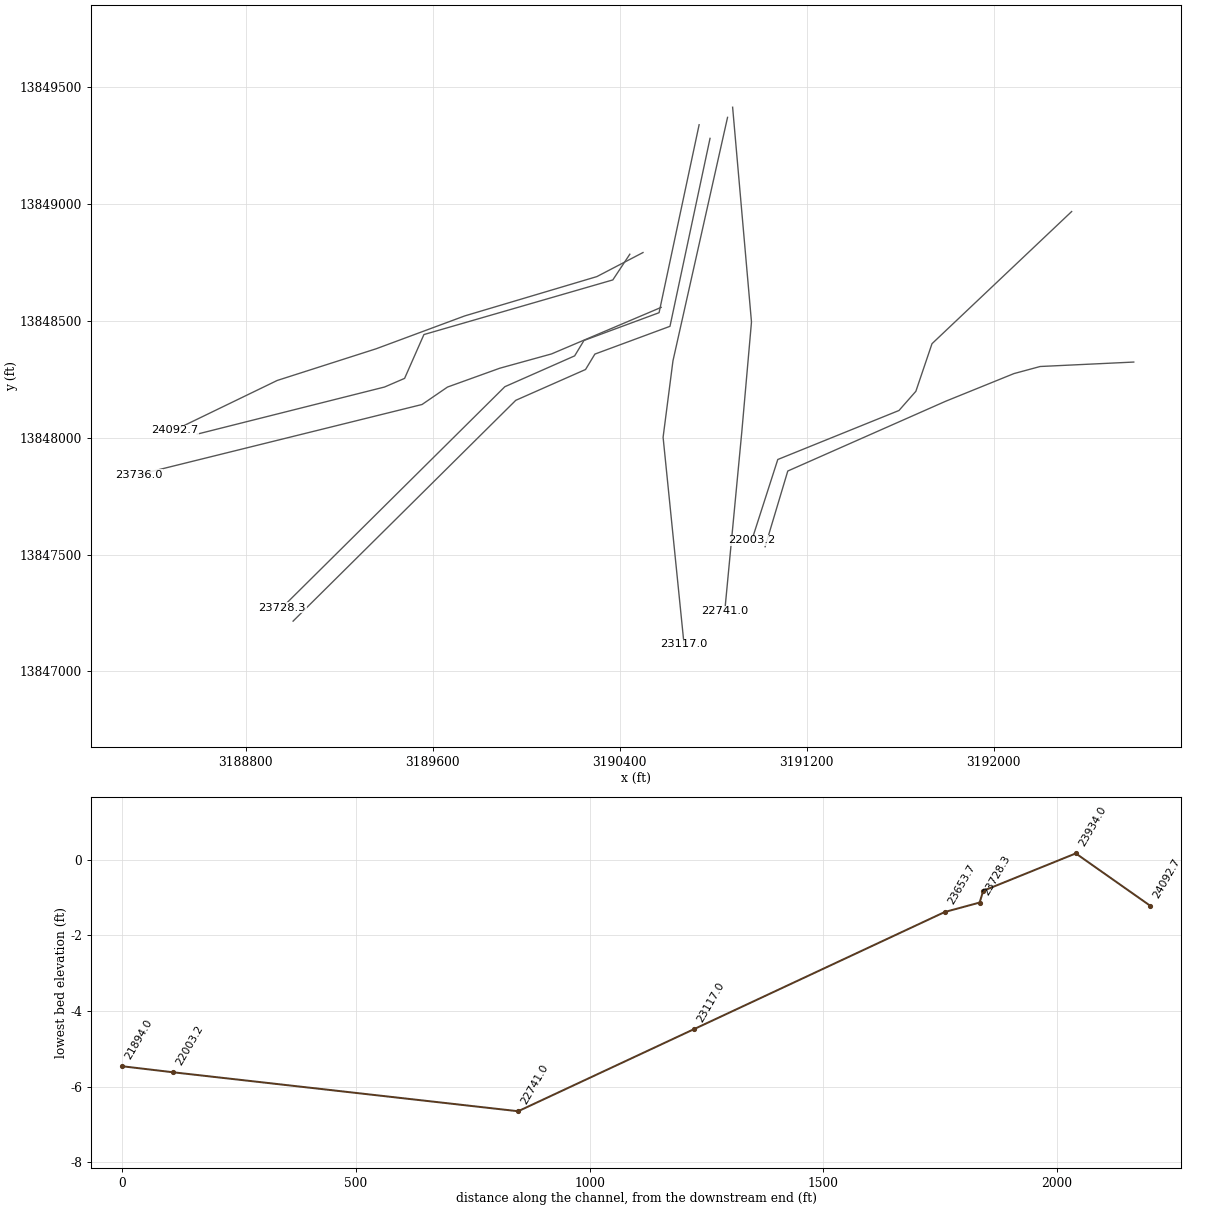
HEC-RAS study N100-00-00.prj: N100-00-00

--- N100-00-00.g01 (geometry) --- (continued)

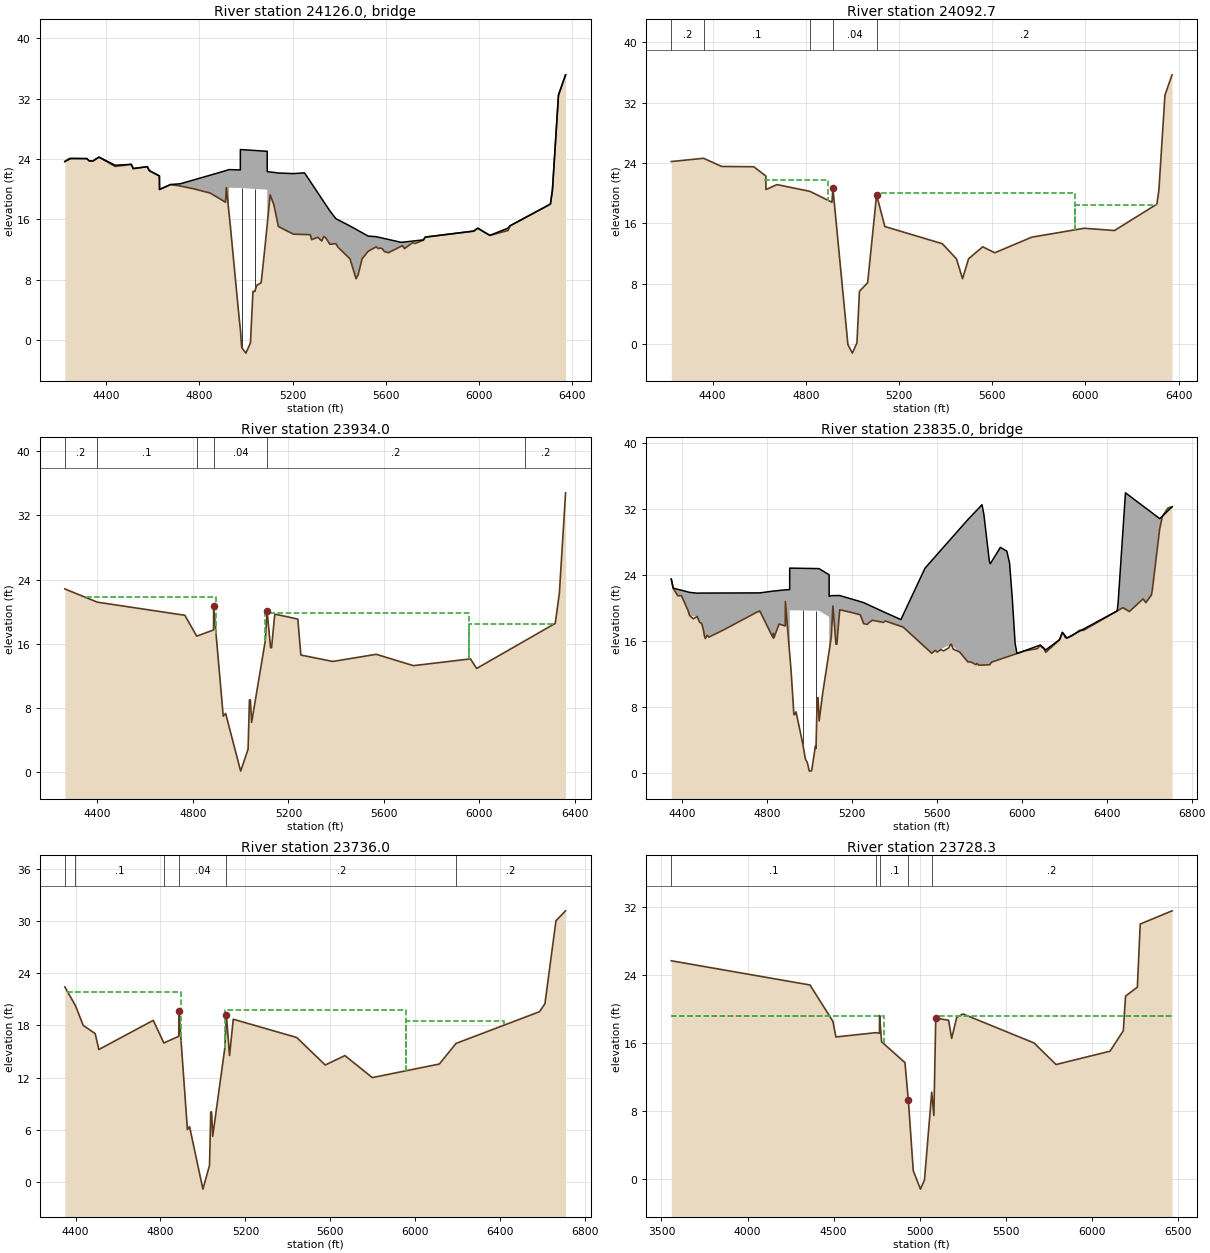
Type RM Length L Ch R = 3 ,24126.0 ,,,
BEGIN DESCRIPTION:
ACCESS ROAD WEST TO BELTWAY 8 - Skewed 30 Degrees
Structure ID: N00-9
END DESCRIPTION:
Bridge Culvert--1,0,-1,-1, 0
Deck Dist Width WeirC Skew NumUp NumDn MinLoCord MaxHiCord MaxSubmerge Is_Ogee
10,46.6,2.6,0, 60, 60, , , .95, 0, 1,1,,
 4222.51 4248.92 4317.77 4326.43 4343.05 4369.03 4438.31 4507.59 4516.25 4576.44
  4585.1  4628.4  4628.9  4676.2  4718.2  4846.2  4912.2  4915.8 4927.31  4927.4
 4975.69  4975.8 5090.97 5091.08 5091.19  5091.3  5103.6  5119.4    5139  5203.4
  5251.2  5275.6  5281.8 5307.78  5325.1 5333.76 5359.74 5385.72 5446.34 5472.32
 5480.98  5498.3 5524.28 5558.92 5610.88 5666.13  5671.5 5680.16  5714.8 5760.78
 5769.44 5977.28  5994.6 6046.56  6124.5 6133.16 6306.36 6315.02    6341 6371.48
   23.65   24.06   24.04   23.75   23.72   24.24   23.16   23.28   22.72   22.97
   22.45   21.74   19.95    20.6    20.7   21.84   22.43   22.47   22.58   22.58
   22.54   25.24   25.01   22.31   22.31   22.31   22.26   22.21   22.13   22.05
   22.15   21.02   20.73   19.53   18.72   18.32   17.12   16.07    15.1   14.66
   14.51   14.21   13.76   13.68   13.32   12.93   12.95   12.98    13.1   13.26
   13.63   14.43   14.81   13.86   14.82   15.13   18.01   19.86   32.46   35.15
   23.65   24.05   24.03   23.74   23.71   24.23      23   23.27   22.71   22.96
   22.44   21.73   19.94   20.59    20.4   19.47   18.25   20.19   16.76   20.18
   20.14   20.14   19.91   19.91   19.91   15.38   19.23   17.93   15.03   14.02
   13.97   13.95   13.29    13.6   13.11   13.71   12.68   12.75   10.74    8.11
    8.58   10.75   11.74   12.34   11.55   12.41   12.49    12.1   12.88   13.22
   13.62   14.42    14.8   13.85    14.5   15.12      18   19.85   32.45   35.15
 4222.51 4239.83 4317.77 4343.05 4369.03 4438.31 4507.59 4516.25 4576.44  4585.1
  4628.4  4628.9  4676.2  4718.2  4846.2  4912.2  4915.8 4927.31  4927.4 4975.69
  4975.8 5090.97 5091.08 5091.19  5091.3  5103.6  5119.4    5139  5203.4  5251.2
  5275.6  5281.8 5307.78  5325.1 5333.76 5359.74 5385.72 5446.34 5472.32 5480.98
  5498.3 5524.28 5558.92 5610.88 5666.13  5671.5 5680.16  5714.8 5726.14 5760.78
 5769.44 5977.28  5994.6 6046.56  6124.5 6133.16 6306.36 6315.02    6341 6371.48
   24.11   24.51   24.49   24.17   24.69   23.46   23.73   23.17   23.42    22.9
   22.19    20.4   21.05   20.86   21.84   22.43   22.47   22.58   22.58   22.54
   25.24   25.01   22.31   22.31   22.31   22.26   22.21   22.13   22.05   22.15
   21.02   20.73   19.53   18.72   18.32   17.12   16.07    15.1   14.66   14.51
   14.21   13.76   13.68   13.32   12.93   12.95   12.98   13.34   13.25   13.68
   14.08   14.88   15.26   14.31   14.96   15.58   18.46   20.31   32.91   35.61
   24.11   24.51   24.49   24.17   24.69   23.46   23.73   23.17   23.42    22.9
   22.19    20.4   21.05   20.86   19.93   18.71   20.65   17.22   20.64    20.6
    20.6   20.37   20.37   20.37   15.84   19.69   18.39   15.49   14.48   14.43
   14.41   13.75   14.06   13.57   14.17   13.14   13.21    11.2    8.57    9.04
   11.21    12.2    12.8   12.01   12.87   12.95   12.56   13.34   13.25   13.68
   14.08   14.88   15.26   14.31   14.96   15.58   18.46   20.31   32.91   35.61
Pier Skew, UpSta & Num, DnSta & Num=  ,4982.5, 2 ,4982.5, 2 , 0 , 0 , 0 ,,
     1.4     1.4
    -2.1   21.12
     1.4     1.4
   -1.64   21.58
Pier Skew, UpSta & Num, DnSta & Num=  ,5037.5, 2 ,5037.5, 2 , 0 , 0 , 0 ,,
     1.4     1.4
    5.42   20.96
     1.4     1.4
    5.88   21.42
Abutment Skew #Up #Dn= , 2 , 2
  4927.2  4955.3
   20.18    7.83
  4927.2  4955.3
   20.64    8.29
Abutment Skew #Up #Dn= , 2 , 2
  5065.2 5091.39
     7.6   19.91
  5065.2 5091.39
    8.06   20.37
BR Coef= 1 , 1 , 0 ,1.25, 0 ,,,.8,0,2,0,
WSPro=,,,, 1 ,,,, 0 ,,,, 0 ,,,,-1 ,-1 ,-1 , 0 , 0 , 0 , 0 , 0
BR U #Sta/Elev= 126
 4222.51   23.65 4239.83   24.05 4248.92   24.05 4283.56   24.04 4317.77   24.03
 4326.43   23.74 4343.05   23.71 4344.18   23.73 4352.84   23.91  4361.3   24.08
 4369.03   24.23 4370.16   24.21 4378.82   24.06 4438.31      23 4482.74   23.17
 4500.06   23.24 4507.59   23.27 4516.25   22.71 4519.46   22.72 4536.78    22.8
 4545.44   22.83  4554.1   22.87 4576.44   22.96  4585.1   22.44 4588.74   22.38
 4614.72   21.95  4628.4   21.73  4628.9   19.94 4632.04   19.98  4676.2   20.59
 4689.37   20.53  4718.2    20.4  4722.7   20.37  4778.9   20.01    4817    19.7
  4846.2   19.47  4873.9   18.96  4912.2   18.25  4915.8   20.19  4927.2   16.79
 4927.31   16.76  4927.4   16.73  4932.9   15.09  4955.2    7.86  4955.3    7.83
    4970    3.09 4975.69    1.41  4975.8    1.38 4975.91    1.34  4976.8    1.08
  4980.5    -.63  4982.5   -1.07  4999.5   -1.76  5019.2     -.4  5023.2    2.21
    5030    6.44  5037.5    6.42  5037.6    6.43  5046.5    7.25  5065.1    7.57
  5065.2     7.6  5081.8   12.41 5090.86   15.24 5090.97   15.28 5091.08   15.31
 5091.19   15.35  5091.3   15.38  5103.6   19.23  5119.4   17.93    5139   15.03
  5175.8   14.45  5203.4   14.02  5251.2   13.97  5275.6   13.95  5281.8   13.29
 5307.78    13.6  5325.1   13.11 5333.76   13.71 5342.42   13.53 5359.74   12.68
 5380.35   12.74 5385.72   12.75 5394.38   12.31 5446.34   10.74 5458.29    9.53
 5472.32    8.11 5480.98    8.58  5498.3   10.75 5524.28   11.74 5527.57    11.8
 5536.23   11.95 5558.92   12.34 5567.58    12.1 5576.24   12.19  5584.9   12.07
 5593.56   11.73 5610.88   11.55 5666.13   12.41  5671.5   12.49 5680.16    12.1
  5714.8   12.88 5726.14   12.79 5760.78   13.22 5765.28   13.43 5769.44   13.62
  5825.9   13.84 5929.82   14.24 5938.48   14.27 5947.14    14.3 5977.28   14.42
 5990.44   14.71  5994.6    14.8 6007.76   14.56 6033.74   14.08 6046.56   13.85
  6124.5    14.5 6133.16   15.12  6172.3   15.77 6180.96   15.91 6306.36      18
 6315.02   19.85 6328.18   26.23 6336.84   30.43    6341   32.45  6345.5   32.85
 6371.48   35.15
BR U #Mann= 5
 4222.51      .2  4361.3      .1    4817     .07  4915.8     .04  5103.6      .2
BR U Banks=4915.8,5103.6
BR D #Sta/Elev= 126
 4222.51   24.11 4239.83   24.51 4248.92   24.51 4283.56    24.5 4317.77   24.49
 4326.43    24.2 4343.05   24.17 4344.18   24.19 4352.84   24.37  4361.3   24.54
 4369.03   24.69 4370.16   24.67 4378.82   24.52 4438.31   23.46 4482.74   23.63
 4500.06    23.7 4507.59   23.73 4516.25   23.17 4519.46   23.18 4536.78   23.26
 4545.44   23.29  4554.1   23.33 4576.44   23.42  4585.1    22.9 4588.74   22.84
 4614.72   22.41  4628.4   22.19  4628.9    20.4 4632.04   20.44  4676.2   21.05
 4689.37   20.99  4718.2   20.86  4722.7   20.83  4778.9   20.47    4817   20.16
  4846.2   19.93  4873.9   19.42  4912.2   18.71  4915.8   20.65  4927.2   17.25
 4927.31   17.22  4927.4   17.19  4932.9   15.55  4955.2    8.32  4955.3    8.29
    4970    3.55 4975.69    1.87  4975.8    1.84 4975.91     1.8  4976.8    1.54
  4980.5    -.17  4982.5    -.61  4999.5    -1.3  5019.2     .06  5023.2    2.67
    5030     6.9  5037.5    6.88  5037.6    6.89  5046.5    7.71  5065.1    8.03
  5065.2    8.06  5081.8   12.87 5090.86    15.7 5090.97   15.74 5091.08   15.77
 5091.19   15.81  5091.3   15.84  5103.6   19.69  5119.4   18.39    5139   15.49
  5175.8   14.91  5203.4   14.48  5251.2   14.43  5275.6   14.41  5281.8   13.75
 5307.78   14.06  5325.1   13.57 5333.76   14.17 5342.42   13.99 5359.74   13.14
 5380.35    13.2 5385.72   13.21 5394.38   12.77 5446.34    11.2 5458.29    9.99
 5472.32    8.57 5480.98    9.04  5498.3   11.21 5524.28    12.2 5527.57   12.26
 5536.23   12.41 5558.92    12.8 5567.58   12.56 5576.24   12.65  5584.9   12.53
 5593.56   12.19 5610.88   12.01 5666.13   12.87  5671.5   12.95 5680.16   12.56
  5714.8   13.34 5726.14   13.25 5760.78   13.68 5765.28   13.89 5769.44   14.08
  5825.9    14.3 5929.82    14.7 5938.48   14.73 5947.14   14.76 5977.28   14.88
 5990.44   15.17  5994.6   15.26 6007.76   15.02 6033.74   14.54 6046.56   14.31
  6124.5   14.96 6133.16   15.58  6172.3   16.23 6180.96   16.37 6306.36   18.46
 6315.02   20.31 6328.18   26.69 6336.84   30.89    6341   32.91  6345.5   33.31
 6371.48   35.61
BR D #Mann= 5
 4222.51      .2  4361.3      .1    4817     .07  4915.8     .04  5103.6      .2
BR D Banks=4915.8,5103.6
BC Design=,, 0 ,, 0 ,,,,,,
BC HTab HWMax=35.14

Type RM Length L Ch R = 1 ,24092.7 ,158.7,158.7,158.7
BEGIN DESCRIPTION:
Downstream Section of Bridge/Culvert/Weir
END DESCRIPTION:
XS GIS Cut Line= 6
      3190499.81     13848791.47      3190302.36     13848688.55
      3189737.13     13848520.36      3189358.63     13848379.95
      3188935.28     13848244.35      3188496.29     13848031.85
#Sta/Elev= 30
 4222.51    24.2  4361.3   24.63 4438.31   23.55 4576.44   23.51  4628.4   22.28
  4628.9   20.49  4676.2   21.14    4817   20.25  4912.2    18.8  4915.8   20.74
  4980.5    -.08  4999.5   -1.21  5019.2     .15    5030    6.99  5065.1    8.12
  5103.6   19.78    5139   15.58 5385.72    13.3 5446.34   11.29 5472.32    8.66
  5498.3    11.3 5558.92   12.89 5610.88    12.1 5769.44   14.17  5994.6   15.35
  6124.5   15.05 6306.36   18.55 6315.02    20.4    6341      33 6371.48    35.7
#Mann= 5 , 1 , 0
 4222.51      .2       0  4361.3      .1       0    4817     .07       0
  4915.8     .04       0  5103.6      .2       0
#XS Ineff= 3 ,-1
    4620    4897    21.8    5103    5956      20    5957    6305    18.5
Permanent Ineff=
       F       F       F
Bank Sta=4915.8,5103.6
XS Rating Curve= 0
Exp/Cntr=.5,.3

Type RM Length L Ch R = 1 ,23934.0 ,198,198,198
BEGIN DESCRIPTION:
Upstream Section of Bridge/Culvert/Weir
END DESCRIPTION:
XS GIS Cut Line= 6
      3190443.43     13848784.32      3190370.75     13848674.41
      3189562.81     13848440.69       3189480.2     13848253.31
       3189394.5     13848216.36      3188593.46     13848014.95
#Sta/Elev= 30
 4263.64   22.85  4399.9    21.2  4766.2   19.57    4816   16.97  4886.4   17.74
  4886.9   20.69    4927    7.01  4937.1    7.35    5000     .17  5031.1    2.91
  5036.7    9.04  5040.8    9.04  5045.9    6.24  5103.2    16.4  5110.6   20.15
  5125.3   15.53  5129.4   15.53  5142.9    19.7  5191.8   19.41  5239.4   19.09
 5252.18   14.62 5385.89   13.82 5567.75   14.71 5723.63    13.3 5962.39   14.14
 5988.37   12.95  6191.9   16.42 6317.45   18.56 6334.77   22.31 6360.75   34.81
#Mann= 6 , 1 , 0
 4263.64      .2       0  4399.9      .1       0    4816     .07       0
  4886.9     .04       0  5110.6      .2       0  6191.9      .2       0
#XS Ineff= 3 ,-1
    4358    4897    21.8    5103    5956    19.8    5957    6320    18.5
Permanent Ineff=
       F       F       F
Bank Sta=4886.9,5110.6
XS Rating Curve= 0
Exp/Cntr=.5,.3

Type RM Length L Ch R = 3 ,23835.0 ,,,
BEGIN DESCRIPTION:
INTERSTATE 10 - Skewed 30 Degrees
Structure ID: N00-7
END DESCRIPTION:
Bridge Culvert--1,0,-1,-1, 0
Deck Dist Width WeirC Skew NumUp NumDn MinLoCord MaxHiCord MaxSubmerge Is_Ogee
10,178,2.6,0, 60, 60, , , .95, 0, 1,1,,
 4349.72 4358.38 4380.03 4397.35 4436.32 4470.96 4492.61 4509.93  4766.2    4833
  4857.3  4886.4  4886.9 4907.17 4907.28 4907.51  4907.6  5045.3 5092.97 5093.08
 5093.19  5093.3  5103.2  5110.6  5125.3  5129.4  5142.9  5239.4 5255.56 5356.88
  5430.9 5544.37 5575.89 5668.64 5746.58 5812.83 5821.49 5847.47  5851.8 5899.43
 5929.74 5942.73 5955.72 5968.71 5977.37 6087.18 6113.16 6178.11  6191.1 6212.75
 6449.34 6453.67 6488.31 6506.49 6571.44 6584.43 6610.41 6649.38 6662.37 6707.67
    23.5   22.41   22.26   22.15   21.89    21.8   21.81   21.81   21.83   22.06
   22.12    22.2    22.2   22.23   24.83   24.83   24.83   24.77   24.02   21.42
   21.42   21.42    21.5    21.5    21.5   21.51   21.51   20.78   20.65   19.45
    18.6   24.82   25.74   28.44   30.71    32.5   31.36   25.65   25.36   27.34
   26.88   25.42   21.04   15.73    14.5   15.51   14.93   16.17   17.05   16.37
   19.65   20.61   33.94   33.59   32.33   32.08   31.58   30.82   31.11   32.25
    23.5   22.41   21.48    21.5   19.08   18.97   18.14   16.31   19.66   16.39
   18.06   17.83   20.78   14.48   14.44   14.37   19.73   19.67   18.92   18.92
   18.92   14.83   16.49   20.24   15.62   15.62   19.79   19.18   18.11   18.43
   17.78   15.27   14.53   15.61   13.47   13.09    13.1   13.13   13.21   13.81
   14.07   14.19    14.3   14.41   14.49    15.5   14.64   16.16   17.04   16.36
   19.64   19.71   19.85   19.57    21.1   20.65   21.56   29.56   31.11   32.25
 4349.72 4358.38 4380.03 4397.35 4436.32 4470.96 4492.61 4509.93  4766.2    4833
  4857.3  4886.4  4886.9 4907.17 4907.28 4907.51  4907.6  5045.3 5092.97 5093.08
 5093.19  5093.3  5103.2  5110.6  5125.3  5129.4  5142.9  5239.4 5255.56 5356.88
  5430.9 5544.37 5575.89 5668.64 5746.58 5812.83 5821.49 5847.47  5851.8 5899.43
 5929.74 5942.73 5955.72 5968.71 5977.37 6087.18 6113.16 6178.11  6191.1 6212.75
 6449.34 6453.67 6488.31 6506.49 6571.44 6584.43 6610.41 6649.38 6662.37 6707.67
    23.5   22.41   22.26   22.15   21.89    21.8   21.81   21.81   21.83   22.06
   22.12    22.2    22.2   22.23   24.83   24.83   24.83   24.77   24.02   21.42
   21.42   21.42    21.5    21.5    21.5   21.51   21.51   20.78   20.65   19.45
    18.6   24.82   25.74   28.44   30.71    32.5   31.36   25.65   25.36   27.34
   26.88   25.42   21.04   15.73    14.5   15.51   14.93   16.17   17.05   16.37
   19.65   20.61   33.94   33.59   32.33   32.08   31.58   30.82   31.11   32.25
   22.82   21.73    20.8   20.82    18.4   18.29   17.46   15.63   18.98   15.71
   17.38   17.15    20.1    13.8   13.76   13.69   19.05   18.99   18.24   18.24
   18.24   14.15   15.81   19.56   14.94   14.94   19.11    18.5   17.43   17.75
    17.1   14.59   13.85   14.93   12.79   12.41   12.42   12.45   12.53   13.13
   13.39   13.51   13.62   13.73   13.81   14.82   13.96   15.48   16.36   15.68
   18.96   19.03   19.17   18.89   20.42   19.97   20.88   28.88   30.43   31.57
Pier Skew, UpSta & Num, DnSta & Num=  ,4969.3, 2 ,4969.3, 2 , 0 , 0 , 0 ,,
     1.4     1.4
     2.4   20.83
     1.4     1.4
    1.72   20.15
Pier Skew, UpSta & Num, DnSta & Num=  ,5031.1, 2 ,5031.1, 2 , 0 , 0 , 0 ,,
     1.4     1.4
    2.07    20.7
     1.4     1.4
    1.39   20.02
BR Coef= 1 , 1 , 0 ,1.25, 0 ,,,.8,0,2,0,
WSPro=,,,, 1 ,,,, 0 ,,,, 0 ,,,,-1 ,-1 ,-1 , 0 , 0 , 0 , 0 , 0
BR U #Sta/Elev= 153
 4349.72    23.5 4358.38   22.41 4358.99   22.38 4380.03   21.48 4397.35    21.5
  4399.9   21.35 4427.66   19.76 4436.32   19.08  4449.8   18.78 4453.64    18.7
 4470.96   18.97 4483.95   18.25 4492.61   18.14 4501.27   17.32  4505.6   16.65
 4509.93   16.31 4518.59    16.7 4527.25   16.48 4597.22   17.37  4719.8   19.04
  4756.8   19.55  4760.9   19.55  4766.2   19.66  4773.8   19.26    4816   17.06
  4828.9   16.39  4830.4   16.93  4832.2   16.56    4833   16.39  4857.3   18.06
  4886.4   17.83  4886.9   20.78  4892.2   19.13 4907.17   14.48 4907.28   14.44
 4907.39   14.41 4907.51   14.37  4907.6   14.34  4907.7   14.31  4914.1   12.32
    4927     7.1  4931.1     7.1  4937.1    7.44  4952.3    5.58  4969.3    3.51
  4981.1    1.73  4990.1     1.3  4999.9     .26  5010.4      .3  5018.9    1.73
  5028.3    3.27  5031.1       3  5036.7    9.13  5040.8    9.13  5045.3    6.66
  5045.9    6.33  5062.4    9.65  5092.8   14.75 5092.86   14.76 5092.97   14.77
 5093.08   14.79 5093.19   14.81  5093.3   14.83  5098.5    15.7  5103.2   16.49
  5110.6   20.24  5125.3   15.62  5129.4   15.62  5142.9   19.79    5155   19.72
  5191.8    19.5  5199.1   19.45  5239.4   19.18  5251.4   18.39 5255.56   18.11
 5272.88   18.02 5278.94   18.19 5296.26   18.52  5322.6   18.39 5348.22   18.26
 5356.88   18.43  5371.7    18.3  5412.5   17.94  5430.9   17.78 5441.66   17.69
 5544.37   15.27 5575.89   14.53 5593.21   14.87 5601.87   14.67 5619.19   14.97
 5632.18   14.81 5655.65   15.17 5664.31   15.59 5668.64   15.61  5677.3   15.03
 5707.61   14.67 5746.58   13.47 5759.57   13.48  5784.6   13.14 5788.93   13.29
 5797.59   13.08  5808.5   13.09 5812.83   13.09 5821.49    13.1 5825.82   13.11
 5834.48   13.12 5847.47   13.13 5849.55   13.13  5851.8   13.21 5856.13   13.37
 5858.21   13.45 5860.46   13.47 5899.43   13.81 5925.41   14.04 5929.74   14.07
 5942.73   14.19 5955.72    14.3 5968.71   14.41 5973.04   14.45 5977.37   14.49
 5986.03   14.56 6000.58   14.69 6009.24   14.79    6025   14.86 6074.19   15.09
 6087.18    15.5 6095.84   15.22 6100.17   15.23 6113.16   14.64 6146.24   15.41
 6178.11   16.16  6191.1   17.04  6191.9   17.01 6199.76   16.76 6204.09   16.45
 6212.75   16.36 6238.73   16.67 6273.37   17.32 6289.99   17.29 6449.34   19.64
 6453.67   19.71 6476.18   20.04 6488.31   19.85 6506.49   19.57 6571.44    21.1
 6584.43   20.65 6610.41   21.56 6614.74   22.16 6649.38   29.56 6660.81   30.92
 6662.37   31.11 6688.35    32.1 6707.67   32.25
BR U #Mann= 6
 4349.72      .2  4399.9      .1    4816     .07  4886.9     .04  5110.6      .2
  6191.9      .2
BR U Banks=4886.9,5110.6
BR D #Sta/Elev= 153
 4349.72   22.82 4358.38   21.73 4358.99    21.7 4380.03    20.8 4397.35   20.82
  4399.9   20.67 4427.66   19.08 4436.32    18.4  4449.8    18.1 4453.64   18.02
 4470.96   18.29 4483.95   17.57 4492.61   17.46 4501.27   16.64  4505.6   15.97
 4509.93   15.63 4518.59   16.02 4527.25    15.8 4597.22   16.69  4719.8   18.36
  4756.8   18.87  4760.9   18.87  4766.2   18.98  4773.8   18.58    4816   16.38
  4828.9   15.71  4830.4   16.25  4832.2   15.88    4833   15.71  4857.3   17.38
  4886.4   17.15  4886.9    20.1  4892.2   18.45 4907.17    13.8 4907.28   13.76
 4907.39   13.73 4907.51   13.69  4907.6   13.66  4907.7   13.63  4914.1   11.64
    4927    6.42  4931.1    6.42  4937.1    6.76  4952.3     4.9  4969.3    2.83
  4981.1    1.05  4990.1     .62  4999.9    -.42  5010.4    -.38  5018.9    1.05
  5028.3    2.59  5031.1    2.32  5036.7    8.45  5040.8    8.45  5045.3    5.98
  5045.9    5.65  5062.4    8.97  5092.8   14.07 5092.86   14.08 5092.97   14.09
 5093.08   14.11 5093.19   14.13  5093.3   14.15  5098.5   15.02  5103.2   15.81
  5110.6   19.56  5125.3   14.94  5129.4   14.94  5142.9   19.11    5155   19.04
  5191.8   18.82  5199.1   18.77  5239.4    18.5  5251.4   17.71 5255.56   17.43
 5272.88   17.34 5278.94   17.51 5296.26   17.84  5322.6   17.71 5348.22   17.58
 5356.88   17.75  5371.7   17.62  5412.5   17.26  5430.9    17.1 5441.66   17.01
 5544.37   14.59 5575.89   13.85 5593.21   14.19 5601.87   13.99 5619.19   14.29
 5632.18   14.13 5655.65   14.49 5664.31   14.91 5668.64   14.93  5677.3   14.35
 5707.61   13.99 5746.58   12.79 5759.57    12.8  5784.6   12.46 5788.93   12.61
 5797.59    12.4  5808.5   12.41 5812.83   12.41 5821.49   12.42 5825.82   12.43
 5834.48   12.44 5847.47   12.45 5849.55   12.45  5851.8   12.53 5856.13   12.69
 5858.21   12.77 5860.46   12.79 5899.43   13.13 5925.41   13.36 5929.74   13.39
 5942.73   13.51 5955.72   13.62 5968.71   13.73 5973.04   13.77 5977.37   13.81
 5986.03   13.88 6000.58   14.01 6009.24   14.11    6025   14.18 6074.19   14.41
 6087.18   14.82 6095.84   14.54 6100.17   14.55 6113.16   13.96 6146.24   14.73
 6178.11   15.48  6191.1   16.36  6191.9   16.33 6199.76   16.08 6204.09   15.77
 6212.75   15.68 6238.73   15.99 6273.37   16.64 6289.99   16.61 6449.34   18.96
 6453.67   19.03 6476.18   19.36 6488.31   19.17 6506.49   18.89 6571.44   20.42
 6584.43   19.97 6610.41   20.88 6614.74   21.48 6649.38   28.88 6660.81   30.24
 6662.37   30.43 6688.35   31.42 6707.67   31.57
BR D #Mann= 6
 4349.72      .2  4399.9      .1    4816     .07  4886.9     .04  5110.6      .2
  6191.9      .2
BR D Banks=4886.9,5110.6
BC Design=,, 0 ,, 0 ,,,,,,
BC HTab HWMax=34.81

Type RM Length L Ch R = 1 ,23736.0 ,7.7,7.7,7.7
BEGIN DESCRIPTION:
Downstream Section of Bridge/Culvert/Weir
END DESCRIPTION:
XS GIS Cut Line= 6
      3190577.44     13848556.93      3190108.54     13848357.87
      3189887.25     13848296.73       3189663.6     13848216.14
       3189554.8     13848141.59      3188341.87     13847841.38
#Sta/Elev= 30
 4349.72   22.42  4399.9   20.27 4436.32      18 4492.61   17.06 4509.93   15.23
  4766.2   18.58    4816   15.98  4886.4   16.75  4886.9    19.7    4927    6.02
  4937.1    6.36  4999.9    -.82  5031.1    1.92  5036.7    8.05  5040.8    8.05
  5045.9    5.25  5103.2   15.41  5110.6   19.16  5125.3   14.54  5142.9   18.71
 5441.66   16.61 5575.89   13.45 5668.64   14.53 5797.59      12 6113.16   13.56
  6191.9   15.93 6584.43   19.57 6610.41   20.48 6662.37   30.03 6707.67   31.17
#Mann= 6 , 1 , 0
 4349.72      .2       0  4399.9      .1       0    4816     .07       0
  4886.9     .04       0  5110.6      .2       0  6191.9      .2       0
#XS Ineff= 3 ,-1
    4358    4897    21.8    5103    5956    19.8    5957    6419    18.5
Permanent Ineff=
       F       F       F
Bank Sta=4886.9,5110.6
XS Rating Curve= 0
Exp/Cntr=.5,.3

Type RM Length L Ch R = 1 ,23728.3 ,74.6,74.6,74.6
BEGIN DESCRIPTION:
Upstream Section of Bridge/Culvert/Weir
END DESCRIPTION:
XS GIS Cut Line= 6
      3190739.82     13849338.02      3190568.51     13848534.18
      3190247.31     13848415.37      3190207.44      13848349.5
      3189908.97     13848217.67      3188956.61     13847273.29
#Sta/Elev= 30
  3557.1   25.66 4362.83   22.82 4496.13   18.55 4513.33   16.72  4746.7   17.23
  4766.1   17.16    4767   19.24  4772.3   17.84  4778.7   16.16  4914.5   13.71
  4933.9    9.32  4934.2    9.31  4962.6    1.05  5004.4   -1.13  5027.9    -.05
    5070   10.25  5082.4    7.51  5093.3   18.93    5168   18.68  5185.8   16.55
  5215.1   19.02  5251.9   19.42 5664.01   16.02 5792.06   13.49 6105.44   15.05
 6182.84   17.45 6195.74   21.51 6264.54   22.57 6281.06   29.97 6465.96   31.52
#Mann= 5 , 1 , 0
  3557.1      .1       0  4746.7     .07       0  4772.3      .1       0
  4934.2     .04       0    5070      .2       0
#XS Ineff= 2 , 0
       0    4790    19.2    5093       0    19.2
Permanent Ineff=
       F       F
Bank Sta=4933.9,5093.3
XS Rating Curve= 0
Exp/Cntr=.5,.3

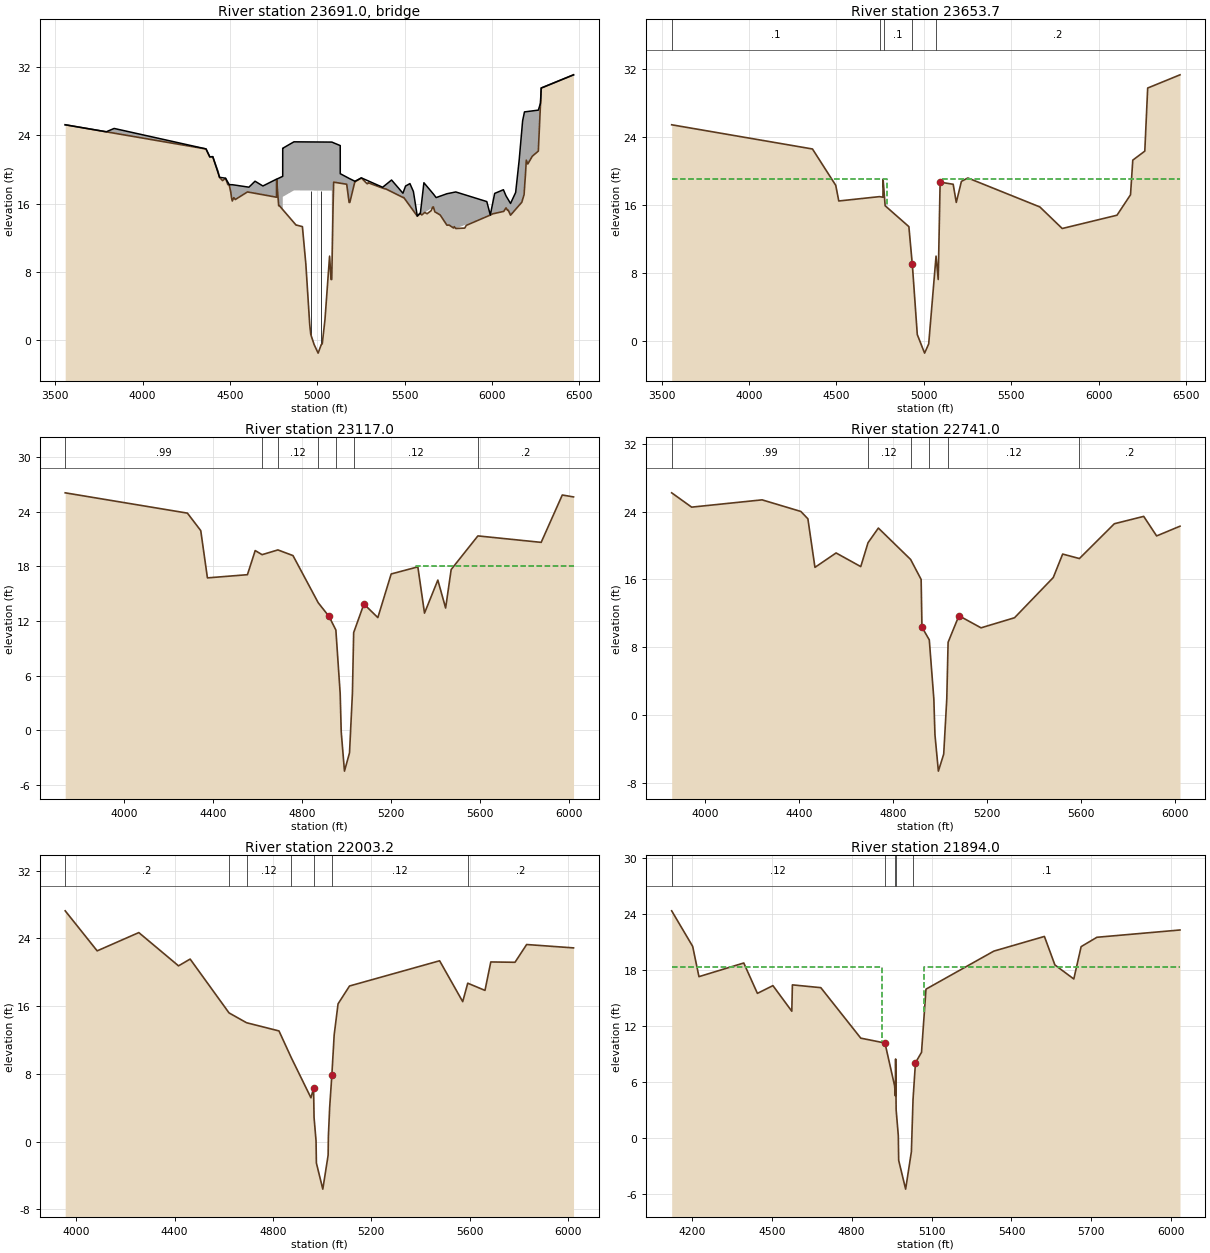
Type RM Length L Ch R = 3 ,23691.0 ,,,
BEGIN DESCRIPTION:
SOUTH ACCESS ROAD INTERSTATE 10
Structure ID: N00-5
END DESCRIPTION:
Bridge Culvert--1,0,-1,-1, 0
Deck Dist Width WeirC Skew NumUp NumDn MinLoCord MaxHiCord MaxSubmerge Is_Ogee
10,54.6,2.6,0, 60, 60, , , .95, 0, 1,1,,
  3557.1  3792.1  3837.1 4362.83 4384.33 4401.53 4440.23 4474.63 4496.13 4513.33
  4608.3  4643.3  4688.3  4766.1    4767  4778.7 4801.69  4801.8 4802.21  4802.3
    4866 5082.69  5082.8  5089.9  5093.3    5131 5131.11    5168  5181.7  5215.1
  5251.9  5373.5  5424.7  5489.7  5504.7  5529.7  5549.7  5571.9  5589.7  5609.7
 5664.01  5679.7 5741.41 5792.06  5969.7  5989.7  6014.7  6064.7 6079.64 6105.44
  6134.7  6154.7  6174.7  6185.2 6195.74 6204.34 6264.54  6277.1 6281.06 6465.96
   25.25   24.43   24.82   22.42   21.49   21.51   19.09   18.98   18.22   18.22
   17.93   18.63   18.07   18.87   18.87   18.98    19.2    22.5    22.5    22.5
   23.25   23.22   23.22   23.16   23.13   22.81   19.51   19.11   18.96   18.62
   19.02   17.92   18.77   17.22   18.06   18.35   17.42   14.54   14.91   18.45
   17.13   16.71   17.16   17.37   16.24   14.67    17.2   17.63   16.91   16.02
   17.31   21.07   25.73   26.76   26.79   26.81   26.97    27.8   29.56   31.11
   25.25   24.42   24.26   22.41   21.48    21.5   19.08   18.97   18.14   16.31
   17.34   17.21   17.04   16.75   18.83   15.75    15.3    15.3   15.29    16.8
   17.55   17.52    7.55   15.56   18.52   18.39   18.39   18.27   16.14   18.61
   19.01   17.83   17.39   16.73   16.43   15.72   15.16   14.53   14.86   14.88
   15.61   14.95   13.47   13.08   14.48   14.66   14.85   15.08    15.5   14.64
   15.33    15.8   16.48   17.73    21.1   20.65   22.16   27.79   29.56   31.11
  3557.1 4362.83 4384.33 4401.53 4440.23 4474.63 4496.13 4513.33  4608.3  4643.3
  4688.3  4766.1    4767  4778.7 4801.69  4801.8 4802.21  4802.3    4866 5082.69
  5082.8  5089.9  5093.3    5131 5131.11    5168  5181.7  5215.1  5251.9  5373.5
  5424.7  5489.7  5504.7  5529.7  5549.7  5571.9  5589.7  5609.7 5664.01  5679.7
 5741.41 5792.06  5969.7  5979.7  5989.7  5994.7  6014.7  6064.7 6079.64 6105.44
  6134.7  6154.7  6174.7  6185.2 6195.74 6204.34 6264.54  6277.1 6281.06 6465.96
   25.47   22.63    21.7   21.72    19.3   19.19   18.36   18.22   17.93   18.63
   18.07   18.87   19.05   18.98    19.2    22.5    22.5    22.5   23.25   23.22
   23.22   23.16   23.13   22.81   19.51   19.11   18.96   18.83   19.23   18.05
   18.77   17.22   18.06   18.35   17.42   14.75   15.08   18.45   17.13   16.71
   17.16   17.37   16.24   15.09   14.88   14.92    17.2   17.63   16.91   16.02
   17.31   21.07   25.73   26.76   26.79   26.81   26.97   28.01   29.78   31.33
   25.47   22.63    21.7   21.72    19.3   19.19   18.36   16.53   17.56   17.43
   17.26   16.97   19.05   15.97   15.52   15.52   15.51   17.02   17.77   17.74
    7.77   15.78   18.74   18.61   18.61   18.49   16.36   18.83   19.23   18.05
   17.61   16.95   16.65   15.94   15.38   14.75   15.08    15.1   15.83   15.17
   13.69    13.3    14.7   14.79   14.88   14.92   15.07    15.3   15.72   14.86
   15.55   16.02    16.7   17.95   21.32   20.87   22.38   28.01   29.78   31.33
Pier Skew, UpSta & Num, DnSta & Num=  ,4962.6, 2 ,4962.6, 2 , 0 , 0 , 0 ,,
     1.4     1.4
     -.4    18.6
     1.4     1.4
    -.18   18.82
Pier Skew, UpSta & Num, DnSta & Num=  ,5022.6, 2 ,5022.6, 2 , 0 , 0 , 0 ,,
     1.4     1.4
   -1.57   18.64
     1.4     1.4
   -1.35   18.86
Abutment Skew #Up #Dn= , 2 , 2
  4802.1  4956.4
    16.8    1.78
  4802.1  4956.4
   17.02       2
Abutment Skew #Up #Dn= , 2 , 2
  5043.6 5082.89
    2.39   17.52
  5043.6 5082.89
    2.61   17.74
BR Coef= 1 , 1 , 0 ,1.25, 0 ,,,.8,0,2,0,
WSPro=,,,, 1 ,,,, 0 ,,,, 0 ,,,,-1 ,-1 ,-1 , 0 , 0 , 0 , 0 , 0
BR U #Sta/Elev= 166
  3557.1   25.25  3727.1   24.65  3762.1   24.53  3792.1   24.42  3837.1   24.26
  3972.1   23.79  4002.1   23.68  4157.1   23.14  4177.1   23.06  4187.1   23.03
  4192.1   23.01  4197.1   22.99  4202.1   22.98  4212.1   22.94  4222.1   22.91
  4357.1   22.43 4362.83   22.41 4384.33   21.48 4401.53    21.5 4431.63   19.76
 4440.23   19.08  4442.1   19.04 4457.43    18.7 4474.63   18.97  4478.3   18.77
 4487.53   18.25 4496.13   18.14 4504.73   17.32 4509.03   16.65 4513.33   16.31
 4521.93    16.7 4530.53   16.48  4573.3   17.03  4598.3   17.35 4600.01   17.37
  4608.3   17.34  4643.3   17.21  4668.3   17.12  4688.3   17.04  4691.3   17.03
  4713.5   16.95  4746.7   16.82  4766.1   16.75    4767   18.83  4772.3   17.43
  4778.7   15.75  4782.9   15.75 4801.69    15.3  4801.8    15.3 4801.91    15.3
 4802.21   15.29  4802.3   15.29    4866   13.77  4878.7   13.47  4882.8   13.47
  4914.5    13.3  4933.9    8.91  4934.2     8.9  4956.3    1.81  4956.4    1.78
  4962.6     .64  4981.3    -.52  5004.4   -1.54  5022.6    -.53  5027.9    -.46
  5043.5    2.36  5043.6    2.39  5054.7    5.59  5065.6    8.62    5070    9.84
  5078.3     7.1  5082.4     7.1 5082.69    7.43  5082.8    7.55  5089.9   15.56
  5093.3   18.52 5130.89   18.39    5131   18.39 5131.11   18.39  5159.3    18.3
    5168   18.27  5181.7   16.14  5185.8   16.14  5215.1   18.61  5218.7    18.6
  5251.9   19.01  5284.1   18.34  5288.2   18.34  5291.3   18.45    5298    18.4
  5298.7   18.39  5358.6   17.93  5373.5   17.83  5387.1   17.73  5391.2   17.73
  5424.7   17.39  5439.7   17.24  5454.7   17.08  5489.7   16.73  5490.3   16.72
  5494.4   16.72  5504.7   16.43  5529.7   15.72  5544.7    15.3  5549.7   15.16
  5571.9   14.53  5574.7   14.59  5579.7   14.68  5589.1   14.87  5589.7   14.86
  5597.7   14.67  5604.7   14.79  5609.7   14.88  5614.9   14.97  5627.8   14.81
  5644.7   15.07 5651.11   15.17 5659.71   15.59 5664.01   15.61 5672.61   15.03
  5679.7   14.95 5702.71   14.67 5741.41   13.47 5754.31   13.48 5779.16   13.14
  5779.7   13.16 5783.46   13.29 5792.06   13.08 5843.66   13.13 5852.26   13.45
  5854.7   13.47  5864.7   13.56  5969.7   14.48  5979.7   14.57  5989.7   14.66
 5993.64   14.69  5994.7    14.7 6002.24   14.79  6004.7    14.8  6014.7   14.85
  6064.7   15.08 6066.74   15.09  6074.7   15.34 6079.64    15.5 6088.24   15.22
  6089.7   15.22 6092.54   15.23  6099.7    14.9 6105.44   14.64  6129.7   15.21
  6134.7   15.33  6139.7   15.45  6154.7    15.8  6169.7   16.15 6169.94   16.16
  6174.7   16.48 6182.84   17.04  6185.2   17.73 6191.44   19.57 6195.74    21.1
 6204.34   20.65 6230.14   21.56 6264.54   22.16  6277.1   27.79 6281.06   29.56
 6465.96   31.11
BR U #Mann= 5
  3557.1      .1  4746.7     .07  4772.3      .1  4934.2     .04    5070      .2
BR U Banks=4933.9,5093.3
BR D #Sta/Elev= 166
  3557.1   25.47  3727.1   24.87  3762.1   24.75  3792.1   24.64  3837.1   24.48
  3972.1   24.01  4002.1    23.9  4157.1   23.36  4177.1   23.28  4187.1   23.25
  4192.1   23.23  4197.1   23.21  4202.1    23.2  4212.1   23.16  4222.1   23.13
  4357.1   22.65 4362.83   22.63 4384.33    21.7 4401.53   21.72 4431.63   19.98
 4440.23    19.3  4442.1   19.26 4457.43   18.92 4474.63   19.19  4478.3   18.99
 4487.53   18.47 4496.13   18.36 4504.73   17.54 4509.03   16.87 4513.33   16.53
 4521.93   16.92 4530.53    16.7  4573.3   17.25  4598.3   17.57 4600.01   17.59
  4608.3   17.56  4643.3   17.43  4668.3   17.34  4688.3   17.26  4691.3   17.25
  4713.5   17.17  4746.7   17.04  4766.1   16.97    4767   19.05  4772.3   17.65
  4778.7   15.97  4782.9   15.97 4801.69   15.52  4801.8   15.52 4801.91   15.52
 4802.21   15.51  4802.3   15.51    4866   13.99  4878.7   13.69  4882.8   13.69
  4914.5   13.52  4933.9    9.13  4934.2    9.12  4956.3    2.03  4956.4       2
  4962.6     .86  4981.3     -.3  5004.4   -1.32  5022.6    -.31  5027.9    -.24
  5043.5    2.58  5043.6    2.61  5054.7    5.81  5065.6    8.84    5070   10.06
  5078.3    7.32  5082.4    7.32 5082.69    7.65  5082.8    7.77  5089.9   15.78
  5093.3   18.74 5130.89   18.61    5131   18.61 5131.11   18.61  5159.3   18.52
    5168   18.49  5181.7   16.36  5185.8   16.36  5215.1   18.83  5218.7   18.82
  5251.9   19.23  5284.1   18.56  5288.2   18.56  5291.3   18.67    5298   18.62
  5298.7   18.61  5358.6   18.15  5373.5   18.05  5387.1   17.95  5391.2   17.95
  5424.7   17.61  5439.7   17.46  5454.7    17.3  5489.7   16.95  5490.3   16.94
  5494.4   16.94  5504.7   16.65  5529.7   15.94  5544.7   15.52  5549.7   15.38
  5571.9   14.75  5574.7   14.81  5579.7    14.9  5589.1   15.09  5589.7   15.08
  5597.7   14.89  5604.7   15.01  5609.7    15.1  5614.9   15.19  5627.8   15.03
  5644.7   15.29 5651.11   15.39 5659.71   15.81 5664.01   15.83 5672.61   15.25
  5679.7   15.17 5702.71   14.89 5741.41   13.69 5754.31    13.7 5779.16   13.36
  5779.7   13.38 5783.46   13.51 5792.06    13.3 5843.66   13.35 5852.26   13.67
  5854.7   13.69  5864.7   13.78  5969.7    14.7  5979.7   14.79  5989.7   14.88
 5993.64   14.91  5994.7   14.92 6002.24   15.01  6004.7   15.02  6014.7   15.07
  6064.7    15.3 6066.74   15.31  6074.7   15.56 6079.64   15.72 6088.24   15.44
  6089.7   15.44 6092.54   15.45  6099.7   15.12 6105.44   14.86  6129.7   15.43
  6134.7   15.55  6139.7   15.67  6154.7   16.02  6169.7   16.37 6169.94   16.38
  6174.7    16.7 6182.84   17.26  6185.2   17.95 6191.44   19.79 6195.74   21.32
 6204.34   20.87 6230.14   21.78 6264.54   22.38  6277.1   28.01 6281.06   29.78
 6465.96   31.33
BR D #Mann= 5
  3557.1      .1  4746.7     .07  4772.3      .1  4934.2     .04    5070      .2
BR D Banks=4933.9,5093.3
BC Design=,, 0 ,, 0 ,,,,,,
BC HTab HWMax=31.52

Type RM Length L Ch R = 1 ,23653.7 ,536.7,536.7,536.7
BEGIN DESCRIPTION:
Downstream Section of Bridge/Culvert/Weir
END DESCRIPTION:
XS GIS Cut Line= 6
      3190786.48     13849279.81      3190615.17     13848475.96
      3190293.97     13848357.15       3190254.1     13848291.28
      3189955.63     13848159.45      3189003.27     13847215.08
#Sta/Elev= 30
  3557.1   25.41 4362.83   22.57 4496.13    18.3 4513.33   16.47  4746.7   16.98
  4766.1   16.91    4767   18.99  4772.3   17.59  4778.7   15.91  4914.5   13.46
  4933.9    9.07  4934.2    9.06  4962.6      .8  5004.4   -1.38  5027.9     -.3
    5070      10  5082.4    7.26  5093.3   18.68    5168   18.43  5185.8    16.3
  5215.1   18.77  5251.9   19.17 5664.01   15.77 5792.06   13.24 6105.44    14.8
 6182.84    17.2 6195.74   21.26 6264.54   22.32 6281.06   29.72 6465.96   31.27
#Mann= 5 , 1 , 0
  3557.1      .1       0  4746.7     .07       0  4772.3      .1       0
  4934.2     .04       0    5070      .2       0
#XS Ineff= 2 , 0
       0    4790      19    5093       0      19
Permanent Ineff=
       F       F
Bank Sta=4933.9,5093.3
XS Rating Curve= 0
Exp/Cntr=.5,.3

Type RM Length L Ch R = 1 ,23117.0 ,324.4,376,324.6
BEGIN DESCRIPTION:
Cross Section 23117.0 - Interpolated
END DESCRIPTION:
XS GIS Cut Line= 4
      3190861.41     13849369.62      3190627.93     13848328.27
      3190585.74     13848001.27       3190675.4     13847115.18
#Sta/Elev= 30
  3735.1   26.08  4285.1   23.85  4345.1   21.93  4375.1   16.74  4555.1   17.09
  4590.1   19.74  4621.2   19.29  4692.3   19.81  4760.1   19.19  4873.7   14.01
  4921.9   12.52  4953.1   11.02  4972.5    4.04  4977.2    -.17  4991.8   -4.48
  5014.5   -2.47  5027.6    4.08  5033.2   10.73  5079.3   13.87    5142   12.38
    5202   17.17    5322   17.95    5352   12.87    5412    16.5    5447   13.43
    5472   17.66  5592.2   21.35    5877   20.64    5972   25.84  6022.6   25.63
#Mann= 7 , 1 , 0
  3735.1     .99       0  4621.2     .12       0  4692.3     .12       0
  4873.7      .1       0  4953.1     .04       0  5033.2     .12       0
  5592.2      .2       0
#XS Ineff= 2 , 0
       0                    5315       0      18
Permanent Ineff=
       F       F
Bank Sta=4921.9,5079.3
XS Rating Curve= 0
Exp/Cntr=.3,.1

Type RM Length L Ch R = 1 ,22741.0 ,745.5,737.8,619.7
BEGIN DESCRIPTION:
Cross Section 22741
Located At: 1ST XS DS IH-10
END DESCRIPTION:
XS GIS Cut Line= 4
      3190883.08     13849412.96      3190963.74     13848494.42
      3190922.29     13848023.66      3190849.46     13847257.58
#Sta/Elev= 30
  3856.3   26.21  3941.3   24.52  4241.3   25.38  4406.3   24.01  4436.3   23.14
  4466.3   17.41  4556.3   19.11  4661.3    17.5  4692.3   20.32  4736.3   22.05
  4873.7   18.34  4918.4   15.98  4921.9   10.35  4953.1    8.85  4972.5    1.87
  4977.2   -2.34  4991.8   -6.65  5014.5   -4.64  5027.6    1.91  5033.2    8.56
  5079.3    11.7  5173.4   10.27    5316   11.46    5481   16.21    5521   18.98
  5592.2   18.45    5741   22.56    5866   23.43    5921   21.12  6020.5   22.27
#Mann= 6 , 1 , 0
  3856.3     .99       0  4692.3     .12       0  4873.7      .1       0
  4953.1     .04       0  5033.2     .12       0  5592.2      .2       0
Bank Sta=4921.9,5079.3
XS Rating Curve= 0
Exp/Cntr=.3,.1

Type RM Length L Ch R = 1 ,22003.2 ,122.6,109.2,40.9
BEGIN DESCRIPTION:
Cross Section 22003.2 - Interpolated Skewed 38 Degrees
END DESCRIPTION:
XS GIS Cut Line= 6
      3192333.08     13848966.84      3191735.78     13848401.58
      3191666.83     13848198.03      3191594.61     13848115.96
      3191076.25     13847906.33      3190965.36     13847561.68
#Sta/Elev= 30
 3954.72   27.26 4084.74   22.53 4254.16   24.69  4415.7   20.76 4462.98   21.56
  4621.2    15.2  4692.3   14.04 4824.35   13.07  4873.7    9.95 4954.37    5.17
    4965     6.3    4967    2.85  4975.1      .1  4976.5   -2.54  5002.6   -5.62
  5024.2   -1.62  5025.3     .63  5030.4    3.98  5039.5     7.9 5048.86   12.61
 5064.62   16.27 5111.34   18.38 5477.76   21.36 5571.69   16.53  5592.2   18.71
 5662.31   17.86 5685.95   21.22 5784.45   21.18 5831.73   23.28 6022.51   22.88
#Mann= 7 , 1 , 0
 3954.72      .2       0  4621.2     .12       0  4692.3     .12       0
  4873.7      .1       0    4965     .04       0  5039.5     .12       0
  5592.2      .2       0
Bank Sta=4965,5039.5
XS Rating Curve= 0
Exp/Cntr=.5,.3

Type RM Length L Ch R = 1 ,21894.0 ,56,56,56
BEGIN DESCRIPTION:
Upstream Section of Bridge/Culvert/Weir
END DESCRIPTION:
XS GIS Cut Line= 6
      3192598.69     13848323.09      3192198.38     13848304.07
       3192086.2     13848273.75      3191793.87     13848155.31
      3191118.99     13847857.04      3191022.06     13847533.31
#Sta/Elev= 30
 4124.22   24.31 4203.02   20.51 4226.66   17.27 4394.89   18.73 4446.11   15.48
 4504.35   16.31 4575.27   13.57  4577.4   16.39  4684.2   16.09  4834.2   10.69
    4925   10.17  4961.2     5.6  4964.2     4.5    4965    8.46    4967    3.01
  4975.1     .26  4976.5   -2.38  5002.6   -5.46  5024.2   -1.46  5030.4    4.14
  5039.5    8.06  5062.2    9.17    5079   15.93  5333.8      20 5523.63   21.57
 5563.03   18.52 5633.95   17.02 5661.53   20.48 5720.63   21.48 6032.67   22.26
#Mann= 5 , 1 , 0
 4124.22     .12       0    4925     .12       0  4961.2      .1       0
    4965    .055       0  5030.4      .1       0
#XS Ineff= 2 , 0
       0    4915    18.3    5073       0    18.3
Permanent Ineff=
       F       F
Bank Sta=4925,5039.5
XS Rating Curve= 0
Exp/Cntr=.5,.3