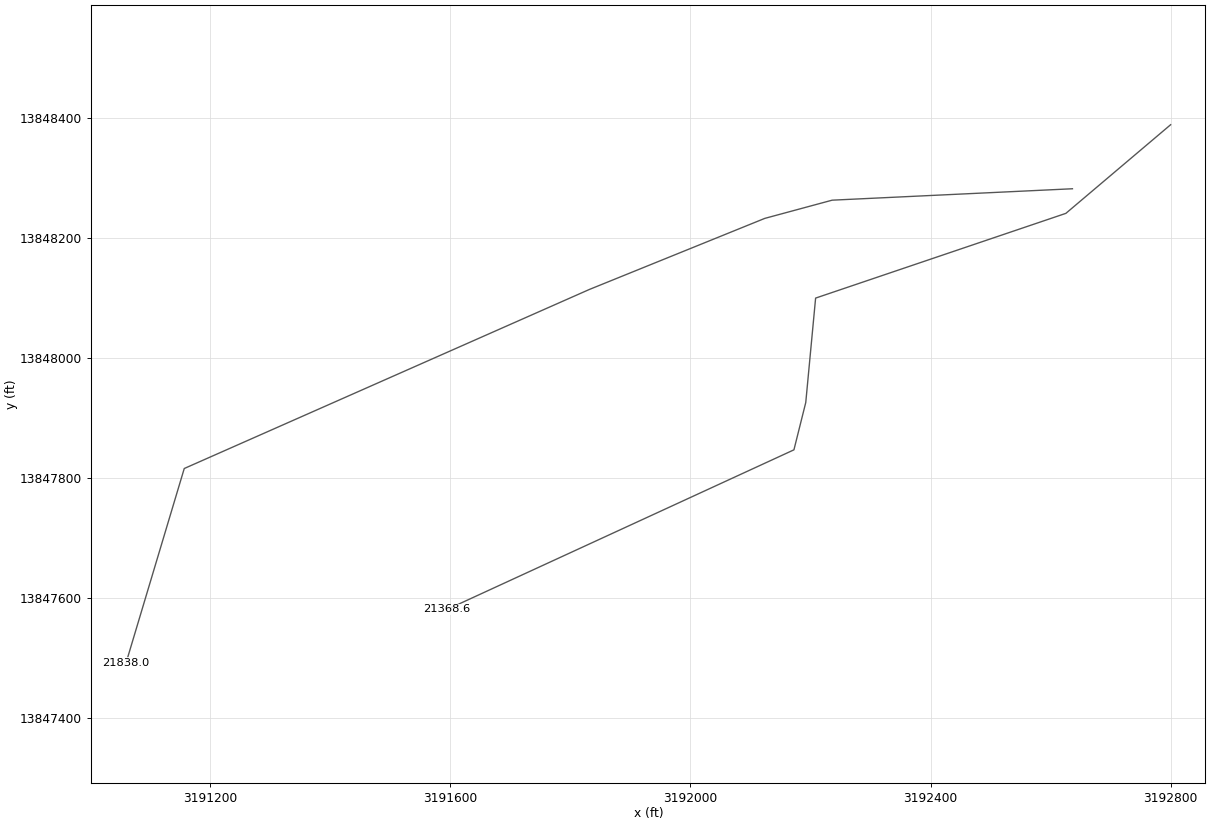
HEC-RAS study N100-00-00.prj: N100-00-00

--- N100-00-00.g01 (geometry) --- (continued)

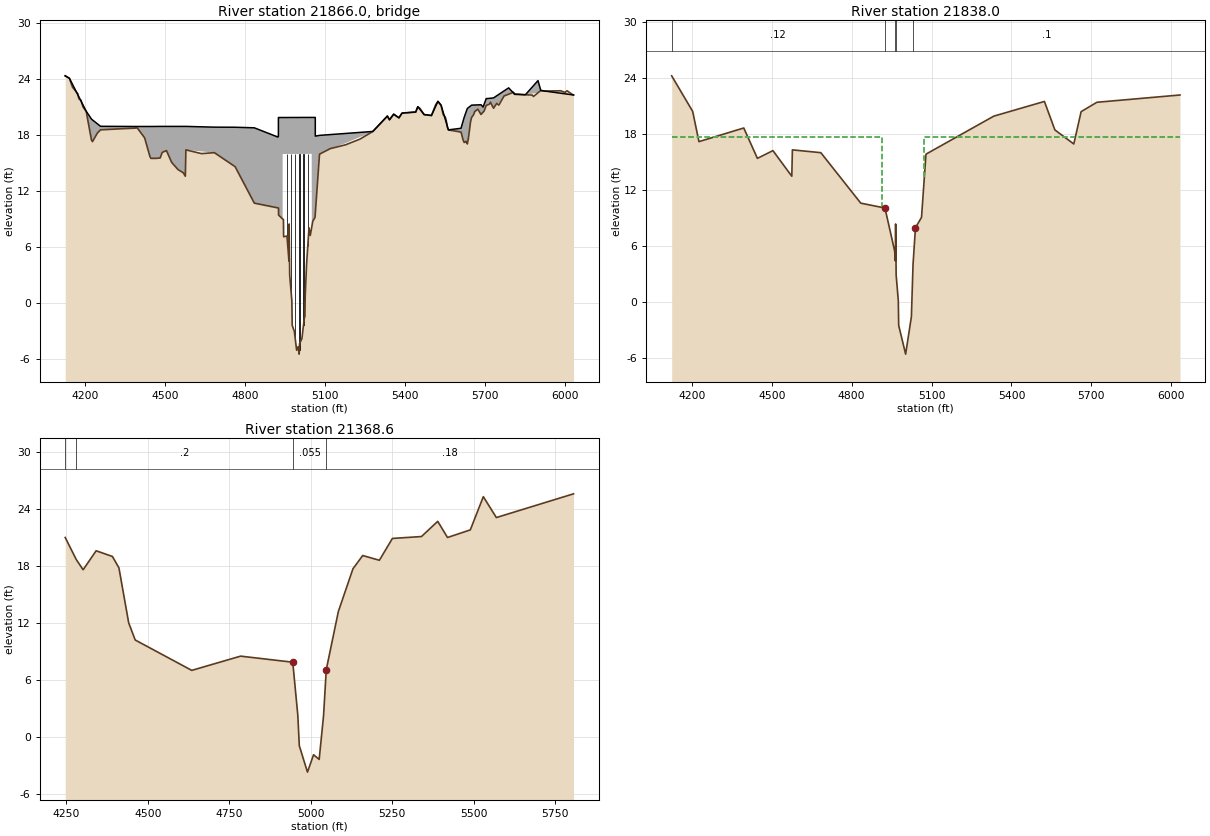
Type RM Length L Ch R = 3 ,21866.0 ,,,
BEGIN DESCRIPTION:
MARKET STREET, SKEW ANGLE OF 38 DEGREES
Structure ID: N00-4
END DESCRIPTION:
Bridge Culvert--1,0,-1,-1, 0
Deck Dist Width WeirC Skew NumUp NumDn MinLoCord MaxHiCord MaxSubmerge Is_Ogee
10,36,2.6,0, 60, 60, , , .95, 0, 1,1,,
 4124.22 4139.98 4203.02 4222.72 4226.66 4256.99 4394.89 4422.47 4446.11 4480.71
 4504.35 4524.05 4575.27  4577.4  4684.2  4762.2  4834.2  4922.7 4924.59  4924.7
    4925  4925.3 4940.65 4940.74 5049.77 5049.88  5062.2  5063.1 5063.21    5079
    5279  5333.8 5341.68 5357.44 5377.14 5388.96 5440.18 5448.06  5471.7 5499.28
 5523.63 5535.45 5563.03 5610.21 5622.13 5633.95 5649.71 5661.53 5673.35 5685.17
 5693.05 5704.87 5720.63 5732.45 5788.95 5811.25 5851.99 5899.27 5909.75 6032.67
   24.32   24.06   20.53    19.7    19.6   18.92    18.9    18.9    18.9   18.91
   18.91   18.91   18.91   18.91   18.83   18.82   18.76   17.77   17.86   19.86
   19.86   19.86   19.86   19.86   19.87   19.87   19.87   19.87   17.87   17.95
   18.37   20.02   19.62   20.22   19.83   20.34   20.45   21.02   20.18   20.08
   21.59   21.17   18.54   18.71   19.88   20.83   21.18    21.2   21.21   21.23
   20.98   21.88   21.92   21.96   23.03   22.37    22.3   23.81   22.75   22.27
   24.32   24.05   20.52   17.46   17.28   18.54   18.74   17.68   15.49   15.53
   16.32   15.05   13.58    16.4    16.1    14.6    10.7   10.19   10.18   10.18
   10.18    9.42    9.01   15.96   15.97    8.15    9.18    9.54    9.58   15.94
   18.36   20.01   19.61   20.21   19.82   20.33   20.44   21.01   20.17   20.07
   21.58   21.16   18.53   18.31   17.19   17.03   19.85   20.49   20.75   20.19
   20.43   21.15   21.49   20.85   22.35   22.34   22.29   22.51   22.75   22.27
 4124.22 4139.98 4203.02 4222.72 4226.66 4256.99 4394.89 4422.47 4446.11 4480.71
 4504.35 4524.05 4575.27  4577.4  4684.2  4762.2  4834.2  4922.7 4924.59  4924.7
    4925  4925.3 4940.65 4940.74 5049.77 5049.88  5062.2  5063.1 5063.21    5079
    5279  5333.8 5341.68 5357.44 5377.14 5388.96 5440.18 5448.06  5471.7 5499.28
 5523.63 5535.45 5563.03 5610.21 5622.13 5633.95 5649.71 5661.53 5673.35 5685.17
 5693.05 5704.87 5720.63 5732.45 5788.95 5811.25 5851.99 5899.27 5909.75 6032.67
   24.32   24.06   20.53    19.7    19.6   18.92    18.9    18.9    18.9   18.91
   18.91   18.91   18.91   18.91   18.83   18.82   18.76   17.77   17.86   19.86
   19.86   19.86   19.86   19.86   19.87   19.87   19.87   19.87   17.87   17.95
   18.37   20.02   19.62   20.22   19.83   20.34   20.45   21.02   20.18   20.08
   21.59   21.17   18.54   18.71   19.88   20.83   21.18    21.2   21.21   21.23
   20.98   21.88   21.92   21.96   23.03   22.37    22.3   23.81   22.75   22.27
   24.17    23.9   20.37   17.31   17.13   18.39   18.59   17.53   15.34   15.38
   16.17    14.9   13.43   16.25   15.95   14.45   10.55   10.04   10.03   10.03
   10.03    9.27    8.86   15.81   15.82       8    9.03    9.39    9.43   15.79
   18.21   19.86   19.46   20.06   19.67   20.18   20.29   20.86   20.02   19.92
   21.43   21.01   18.38   18.16   17.04   16.88    19.7   20.34    20.6   20.04
   20.28      21   21.34    20.7    22.2   22.19   22.14   22.36    22.6   22.12
Pier Skew, UpSta & Num, DnSta & Num=  ,4956, 2 ,4956, 2 , 0 , 0 , 0 ,,
     1.3     1.3
    6.17   16.96
     1.3     1.3
    6.02   16.81
Pier Skew, UpSta & Num, DnSta & Num=  ,4971.9, 2 ,4971.9, 2 , 0 , 0 , 0 ,,
     1.3     1.3
      .1   16.96
     1.3     1.3
    -.05   16.81
Pier Skew, UpSta & Num, DnSta & Num=  ,4987.8, 2 ,4987.8, 2 , 0 , 0 , 0 ,,
     1.3     1.3
   -4.94   16.96
     1.3     1.3
   -5.09   16.81
Pier Skew, UpSta & Num, DnSta & Num=  ,5003.2, 2 ,5003.2, 2 , 0 , 0 , 0 ,,
     1.3     1.3
   -6.43   16.97
     1.3     1.3
   -6.58   16.82
Pier Skew, UpSta & Num, DnSta & Num=  ,5019.1, 2 ,5019.1, 2 , 0 , 0 , 0 ,,
     1.3     1.3
   -3.45   16.97
     1.3     1.3
    -3.6   16.82
Pier Skew, UpSta & Num, DnSta & Num=  ,5034.9, 2 ,5034.9, 2 , 0 , 0 , 0 ,,
     1.3     1.3
    4.81   16.97
     1.3     1.3
    4.66   16.82
BR Coef= 1 , 1 , 0 ,1.25, 0 ,,,.8,0,2,0,
WSPro=,,,, 1 ,,,, 0 ,,,, 0 ,,,,-1 ,-1 ,-1 , 0 , 0 , 0 , 0 , 0
BR U #Sta/Elev= 162
 4124.22   24.32 4127.53   24.26 4139.98   24.05  4151.8    23.1 4166.93   22.56
  4171.5    22.4 4175.44   21.86 4183.32   21.71  4191.2   20.99 4194.51   20.86
 4202.39   20.55 4203.02   20.52 4210.27   19.39 4222.72   17.46 4226.66   17.28
 4245.17    18.2 4253.61   18.44 4256.99   18.54 4288.44   18.59  4310.4   18.62
 4394.89   18.74 4422.47   17.68 4442.17    15.7 4446.11   15.49 4464.95   15.49
 4480.71   15.53 4488.59   16.13 4504.35   16.32 4524.05   15.05 4547.69   14.29
 4567.39   13.95 4575.27   13.58  4577.4    16.4  4635.8      16  4653.6   16.04
  4684.2    16.1  4724.9   15.32  4762.2    14.6  4816.1   11.68  4834.2    10.7
  4922.7   10.19 4924.59   10.18  4924.7   10.18 4924.81   10.18    4925   10.18
  4925.3    9.42 4940.65    9.01 4940.74    9.01 4941.14       9  4943.6    8.93
  4944.2    7.11  4956.9    7.18  4961.2    5.61  4964.2    4.51    4965    8.47
    4967    3.02  4974.6     .37  4975.1     .27  4976.5   -2.37  4984.5   -3.02
  4993.1   -5.03  4998.4   -4.67  5002.6   -5.45    5004   -4.34  5012.9   -3.79
    5022   -1.58  5024.2   -1.45  5025.3      .8  5030.4    4.15  5039.5    8.07
  5044.3    7.25 5049.49    8.08 5049.77    8.13 5049.88    8.15  5053.7    8.76
  5062.2    9.18  5062.9    9.46 5062.99     9.5  5063.1    9.54 5063.21    9.58
    5079   15.94  5118.9   16.52  5120.1   16.54  5174.2   16.92  5176.7   16.94
  5228.6   17.52  5230.7   17.55    5279   18.36  5292.1   18.75  5333.8   20.01
 5341.68   19.61 5357.44   20.21 5377.14   19.82 5388.96   20.33 5440.18   20.44
 5448.06   21.01 5455.94   20.84  5471.7   20.17 5499.28   20.07 5515.04   21.23
 5523.63   21.58 5535.45   21.16 5543.33   20.17 5547.27   20.04 5551.21   19.91
 5555.15   19.48 5559.09    18.8 5563.03   18.53 5566.97   18.51 5578.79   18.46
 5582.73   18.44 5590.61    18.4 5594.55   18.38 5598.49   18.36 5610.21   18.31
 5610.31    18.3 5618.19   17.45 5622.13   17.19 5629.91   17.31 5630.01    17.3
 5633.95   17.03 5637.89    17.6 5641.83   18.48 5645.77   19.35 5649.71   19.85
 5657.59   20.16 5661.53   20.49 5673.35   20.75 5685.07   20.19 5685.17   20.19
 5689.11   20.31 5693.05   20.43 5696.99   20.55 5704.77   21.15 5704.87   21.15
 5716.69   21.29 5720.63   21.49 5732.45   20.85 5744.27   21.37 5752.05   21.19
 5752.15   21.19 5771.75   22.16 5771.85   22.16 5777.13   22.22 5788.95   22.35
 5800.77   22.49 5807.31   22.56 5811.25   22.34 5840.17   22.31 5851.99   22.29
 5875.63   22.26 5878.23   22.26 5882.17   22.11 5891.39   22.32 5899.27   22.51
 5909.75   22.75 5925.51   22.69 5984.61   22.72 6000.37   22.55 6008.25   22.72
 6031.89   22.26 6032.67   22.27
BR U #Mann= 5
 4124.22     .12    4925     .12  4961.2      .1    4965    .055  5030.4      .1
BR U Banks=4925,5039.5
BR D #Sta/Elev= 162
 4124.22   24.17 4127.53   24.11 4139.98    23.9  4151.8   22.95 4166.93   22.41
  4171.5   22.25 4175.44   21.71 4183.32   21.56  4191.2   20.84 4194.51   20.71
 4202.39    20.4 4203.02   20.37 4210.27   19.24 4222.72   17.31 4226.66   17.13
 4245.17   18.05 4253.61   18.29 4256.99   18.39 4288.44   18.44  4310.4   18.47
 4394.89   18.59 4422.47   17.53 4442.17   15.55 4446.11   15.34 4464.95   15.34
 4480.71   15.38 4488.59   15.98 4504.35   16.17 4524.05    14.9 4547.69   14.14
 4567.39    13.8 4575.27   13.43  4577.4   16.25  4635.8   15.85  4653.6   15.89
  4684.2   15.95  4724.9   15.17  4762.2   14.45  4816.1   11.53  4834.2   10.55
  4922.7   10.04 4924.59   10.03  4924.7   10.03 4924.81   10.03    4925   10.03
  4925.3    9.27 4940.65    8.86 4940.74    8.86 4941.14    8.85  4943.6    8.78
  4944.2    6.96  4956.9    7.03  4961.2    5.46  4964.2    4.36    4965    8.32
    4967    2.87  4974.6     .22  4975.1     .12  4976.5   -2.52  4984.5   -3.17
  4993.1   -5.18  4998.4   -4.82  5002.6    -5.6    5004   -4.49  5012.9   -3.94
    5022   -1.73  5024.2    -1.6  5025.3     .65  5030.4       4  5039.5    7.92
  5044.3     7.1 5049.49    7.93 5049.77    7.98 5049.88       8  5053.7    8.61
  5062.2    9.03  5062.9    9.31 5062.99    9.35  5063.1    9.39 5063.21    9.43
    5079   15.79  5118.9   16.37  5120.1   16.39  5174.2   16.77  5176.7   16.79
  5228.6   17.37  5230.7    17.4    5279   18.21  5292.1    18.6  5333.8   19.86
 5341.68   19.46 5357.44   20.06 5377.14   19.67 5388.96   20.18 5440.18   20.29
 5448.06   20.86 5455.94   20.69  5471.7   20.02 5499.28   19.92 5515.04   21.08
 5523.63   21.43 5535.45   21.01 5543.33   20.02 5547.27   19.89 5551.21   19.76
 5555.15   19.33 5559.09   18.65 5563.03   18.38 5566.97   18.36 5578.79   18.31
 5582.73   18.29 5590.61   18.25 5594.55   18.23 5598.49   18.21 5610.21   18.16
 5610.31   18.15 5618.19    17.3 5622.13   17.04 5629.91   17.16 5630.01   17.15
 5633.95   16.88 5637.89   17.45 5641.83   18.33 5645.77    19.2 5649.71    19.7
 5657.59   20.01 5661.53   20.34 5673.35    20.6 5685.07   20.04 5685.17   20.04
 5689.11   20.16 5693.05   20.28 5696.99    20.4 5704.77      21 5704.87      21
 5716.69   21.14 5720.63   21.34 5732.45    20.7 5744.27   21.22 5752.05   21.04
 5752.15   21.04 5771.75   22.01 5771.85   22.01 5777.13   22.07 5788.95    22.2
 5800.77   22.34 5807.31   22.41 5811.25   22.19 5840.17   22.16 5851.99   22.14
 5875.63   22.11 5878.23   22.11 5882.17   21.96 5891.39   22.17 5899.27   22.36
 5909.75    22.6 5925.51   22.54 5984.61   22.57 6000.37    22.4 6008.25   22.57
 6031.89   22.11 6032.67   22.12
BR D #Mann= 5
 4124.22     .12    4925     .12  4961.2      .1    4965    .055  5030.4      .1
BR D Banks=4925,5039.5
BC Design=,, 0 ,, 0 ,,,,,,
BC HTab HWMax=24.31

Type RM Length L Ch R = 1 ,21838.0 ,469.4,469.4,469.4
BEGIN DESCRIPTION:
Downstream Section of Bridge/Culvert/Weir
END DESCRIPTION:
XS GIS Cut Line= 6
       3192636.4     13848281.69       3192236.1     13848262.67
      3192123.92     13848232.35      3191831.59     13848113.91
      3191156.71     13847815.64      3191059.78     13847491.91
#Sta/Elev= 30
 4124.22   24.21 4203.02   20.41 4226.66   17.17 4394.89   18.63 4446.11   15.38
 4504.35   16.21 4575.27   13.47  4577.4   16.29  4684.2   15.99  4834.2   10.59
    4925   10.07  4961.2     5.5  4964.2     4.4    4965    8.36    4967    2.91
  4975.1     .16  4976.5   -2.48  5002.6   -5.56  5024.2   -1.56  5030.4    4.04
  5039.5    7.96  5062.2    9.07    5079   15.83  5333.8    19.9 5523.63   21.47
 5563.03   18.42 5633.95   16.92 5661.53   20.38 5720.63   21.38 6032.67   22.16
#Mann= 5 , 1 , 0
 4124.22     .12       0    4925     .12       0  4961.2      .1       0
    4965    .055       0  5030.4      .1       0
#XS Ineff= 2 , 0
       0    4915    17.7    5073       0    17.7
Permanent Ineff=
       F       F
Bank Sta=4925,5039.5
XS Rating Curve= 0
Exp/Cntr=.5,.3

Type RM Length L Ch R = 1 ,21368.6 ,257.4,240.6,194.8
BEGIN DESCRIPTION:
Cross Section 21368.6 - Interpolated
END DESCRIPTION:
XS GIS Cut Line= 6
      3192799.99     13848388.38      3192625.47     13848240.71
      3192208.53     13848099.54      3192192.11     13847925.54
      3192172.42     13847846.75      3191594.61     13847580.83
#Sta/Elev= 30
  4246.1      21  4279.7    18.7  4301.1    17.6  4341.1    19.6  4391.1      19
  4411.1    17.8  4441.1      12  4461.1    10.2  4634.7       7  4784.7     8.5
  4944.9    7.86  4960.4    2.27    4965    -.94  4990.1   -3.72  5008.7   -1.89
    5026   -2.38  5039.5    2.25  5047.8    7.08  5084.9    13.2  5129.7    17.7
  5159.7    19.1  5210.9    18.6  5250.9    20.9  5340.1    21.1  5390.1    22.7
  5420.1      21  5490.1    21.8  5530.1    25.3  5570.1    23.1  5807.1    25.6
#Mann= 4 , 1 , 0
  4246.1      .2       0  4279.7      .2       0  4944.9    .055       0
  5047.8     .18       0
Bank Sta=4944.9,5047.8
XS Rating Curve= 0
Exp/Cntr=.3,.1