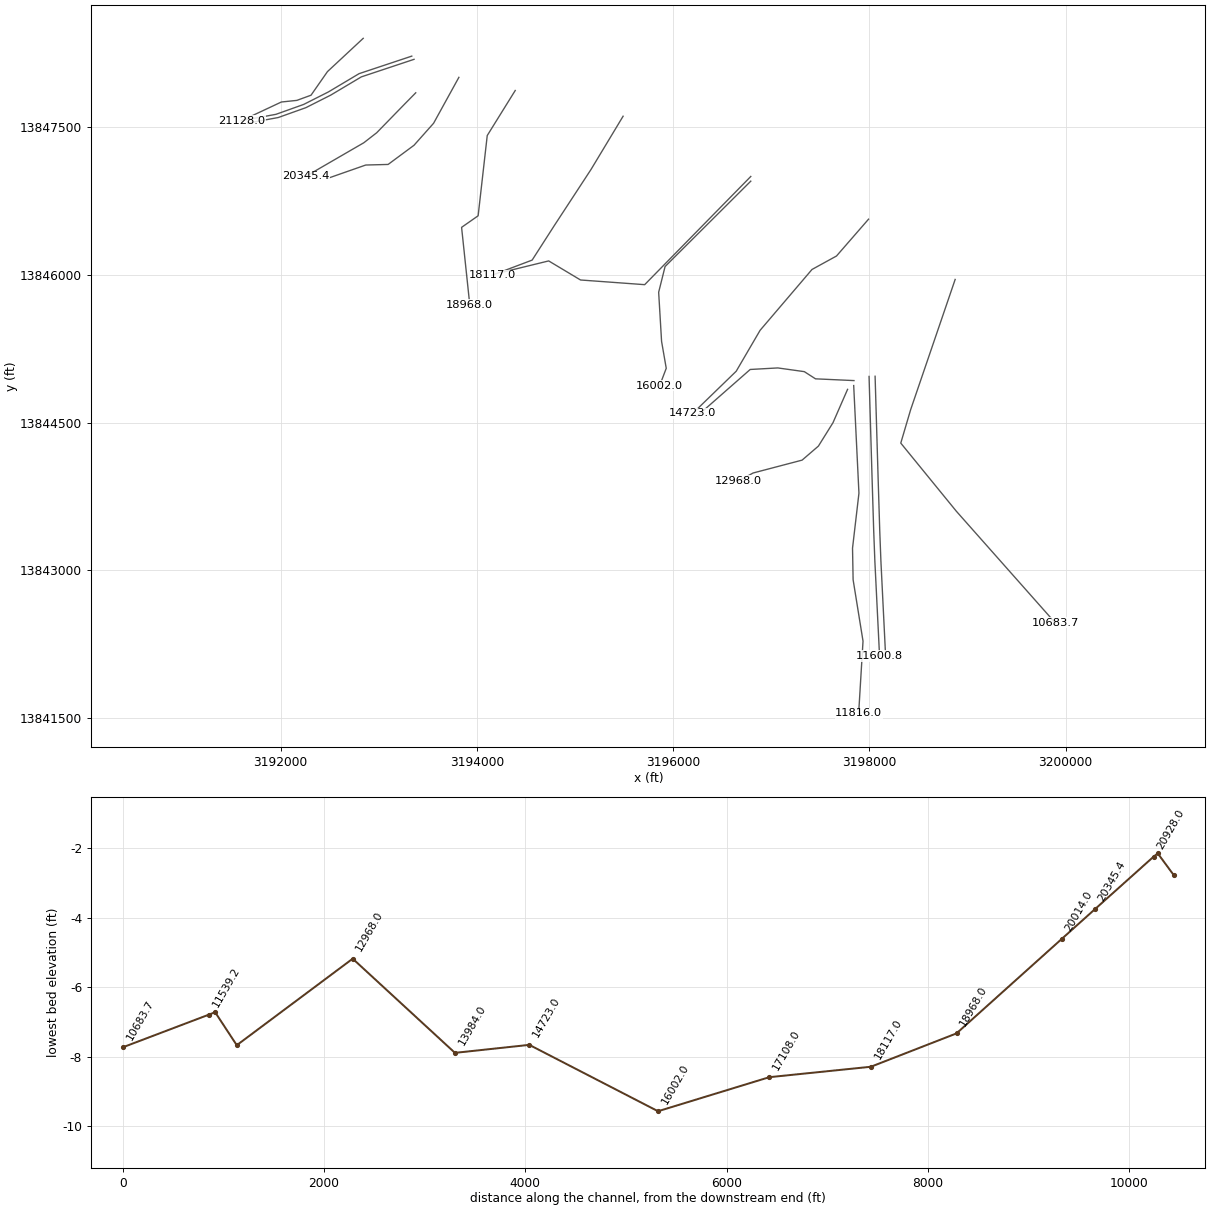
HEC-RAS study N100-00-00.prj: N100-00-00

--- N100-00-00.g01 (geometry) --- (continued)

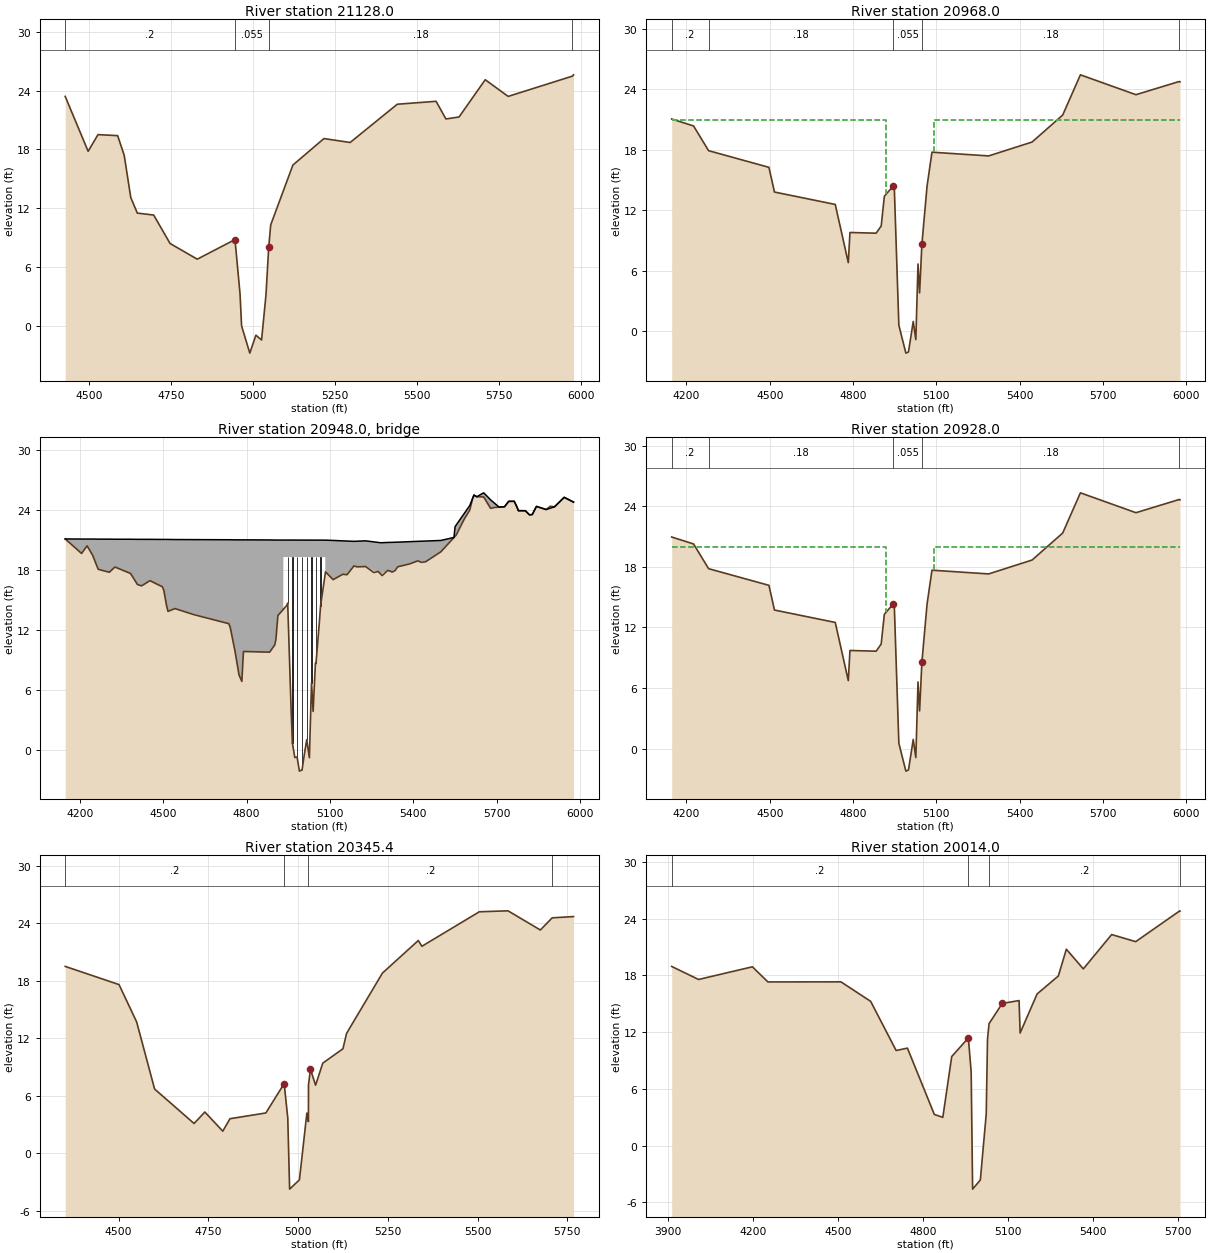
Type RM Length L Ch R = 1 ,21128.0 ,178.2,160,136.5
BEGIN DESCRIPTION:
Cross Section 21128.0 - Interpolated
END DESCRIPTION:
XS GIS Cut Line= 6
      3192842.15     13848404.86      3192477.74     13848066.71
       3192310.3     13847827.05      3192165.85     13847774.52
      3192008.27     13847758.11      3191601.17     13847567.69
#Sta/Elev= 30
  4426.8    23.4  4496.8    17.8  4526.8    19.5  4586.8    19.4  4606.8    17.4
  4626.8    13.1  4646.8    11.5  4696.8    11.3  4746.8     8.4  4829.7     6.8
  4944.9     8.8  4960.4    3.21    4965       0  4990.1   -2.78  5008.7    -.95
    5026   -1.44  5039.5    3.19  5047.8    8.02  5053.9    10.3  5121.6    16.4
  5216.3    19.1  5296.3    18.7    5440    22.6  5558.5    22.9  5588.5    21.1
  5628.5    21.3  5708.5    25.1  5778.5    23.4  5974.7   25.47  5977.9    25.6
#Mann= 4 , 1 , 0
  4426.8      .2       0  4944.9    .055       0  5047.8     .18       0
  5974.7      .2       0
Bank Sta=4944.9,5047.8
XS Rating Curve= 0
Exp/Cntr=.5,.3

Type RM Length L Ch R = 1 ,20968.0 ,40,40,40
BEGIN DESCRIPTION:
Upstream Section of Bridge/Culvert/Weir
END DESCRIPTION:
XS GIS Cut Line= 6
      3193336.95     13848224.16      3192799.92     13848045.97
      3192487.28     13847860.28      3192235.27     13847733.33
      3191952.94     13847632.91      3191639.57     13847575.58
#Sta/Elev= 30
  4146.7   21.06  4225.6   20.37  4279.7   17.92  4496.9   16.27  4516.9   13.82
  4735.8   12.59  4782.8    6.82  4788.7    9.81    4883    9.74  4901.2   10.45
  4912.6    13.4  4944.9   14.43    4948   14.65  4964.8     .62  4990.1   -2.15
  4999.6   -2.03  5016.6     .99    5026    -.81  5033.8    6.69  5039.5    3.82
  5047.8    8.65  5066.4    14.4  5084.1   17.77  5288.3    17.4  5444.8   18.78
  5554.8   21.45  5618.7   25.44  5818.7   23.47  5974.7   24.78  5977.3   24.74
#Mann= 5 , 1 , 0
  4146.7      .2       0  4279.7     .18       0  4944.9    .055       0
  5047.8     .18       0  5974.7      .2       0
#XS Ineff= 2 , 0
       0    4920      21    5093       0      21
Permanent Ineff=
       F       F
Bank Sta=4944.9,5047.8
XS Rating Curve= 0
Exp/Cntr=.5,.3

Type RM Length L Ch R = 3 ,20948.0 ,,,
BEGIN DESCRIPTION:
Old Railroad Bed
Structure ID: N00-3
END DESCRIPTION:
Bridge Culvert--1,0,-1,-1, 0
Deck Dist Width WeirC Skew NumUp NumDn MinLoCord MaxHiCord MaxSubmerge Is_Ogee
10,20,2.6,0, 60, 60, , , .95, 0, 1,1,,
  4146.7  4205.6  4225.6  4245.6  4265.6  4305.6  4325.6  4381.9  4406.9  4421.9
  4451.9  4496.9  4501.9  4516.9  4541.9  4735.8  4740.8  4757.8  4772.8  4782.8
  4788.7    4883  4901.2  4905.5  4912.6 4932.21  4932.3 5083.39  5083.5  5111.6
  5161.6  5186.6  5228.3  5283.3  5308.3  5324.4  5344.4  5416.6  5444.8  5499.8
  5546.7  5550.7  5603.7  5618.7  5628.7  5653.7  5678.7  5708.7  5728.7  5743.7
  5763.7  5778.7  5803.7  5818.7  5828.7  5843.7  5878.7  5908.7  5943.7  5977.3
    21.1   21.09   21.09   21.09   21.08   21.08   21.07   21.07   21.06   21.06
   21.06   21.05   21.05   21.05   21.04   21.02   21.02   21.01   21.01   21.01
   21.01      21   20.99   20.99   20.99   20.99   20.99   20.98   20.98   20.95
   20.89   20.86   20.91   20.72   20.75   20.76   20.78   20.86   20.89   20.95
   21.25   22.33   24.44   25.49   25.32   25.71   25.01   24.29   24.32   24.86
   24.87   23.93   23.92   23.51   23.54   24.35   24.04   24.31   25.26   24.78
    21.1   19.65   20.41   19.46   18.06   17.77   18.29   17.65   16.54   16.41
   16.93   16.31   15.95   13.86   14.14   12.63   12.27    9.94    7.49    6.86
    9.85    9.78   10.49   11.03   13.44   14.07   19.29   19.28    17.7   17.03
   17.52    18.4   18.34   17.58   17.96   17.79   18.32   18.91   18.82   19.82
   21.24   21.37   23.98   25.48   25.31    25.3   24.16   24.28   24.31   24.85
   24.86   23.92   23.92   23.51   23.54   24.35   24.04   24.31   25.26   24.78
  4146.7  4205.6  4225.6  4245.6  4265.6  4305.6  4325.6  4381.9  4406.9  4421.9
  4451.9  4496.9  4501.9  4516.9  4541.9  4735.8  4740.8  4757.8  4772.8  4782.8
  4788.7    4883  4901.2  4905.5  4912.6 4932.21  4932.3 5083.39  5083.5  5111.6
  5161.6  5186.6  5228.3  5283.3  5308.3  5324.4  5344.4  5416.6  5444.8  5499.8
  5546.7  5550.7  5603.7  5618.7  5628.7  5653.7  5678.7  5708.7  5728.7  5743.7
  5763.7  5778.7  5803.7  5818.7  5828.7  5843.7  5878.7  5908.7  5943.7  5977.3
    21.1   21.09   21.09   21.09   21.08   21.08   21.07   21.07   21.06   21.06
   21.06   21.05   21.05   21.05   21.04   21.02   21.02   21.01   21.01   21.01
   21.01      21   20.99   20.99   20.99   20.99   20.99   20.98   20.98   20.95
   20.89   20.86   20.91   20.72   20.75   20.76   20.78   20.86   20.89   20.95
   21.25   22.33   24.44   25.49   25.32   25.71   25.01   24.29   24.32   24.86
   24.87   23.93   23.92   23.51   23.54   24.35   24.04   24.31   25.26   24.78
      21   19.55   20.31   19.36   17.96   17.67   18.19   17.55   16.44   16.31
   16.83   16.21   15.85   13.76   14.04   12.53   12.17    9.84    7.39    6.76
    9.75    9.68   10.39   10.93   13.34   13.97   19.19   19.18    17.6   16.93
   17.42    18.3   18.24   17.48   17.86   17.69   18.22   18.81   18.72   19.72
   21.14   21.27   23.88   25.38   25.21    25.2   24.06   24.18   24.21   24.75
   24.76   23.82   23.82   23.41   23.44   24.25   23.94   24.21   25.16   24.68
Pier Skew, UpSta & Num, DnSta & Num=  ,4948, 2 ,4948, 2 , 0 , 0 , 0 ,,
       1       1
   13.25   20.29
       1       1
   13.15   20.19
Pier Skew, UpSta & Num, DnSta & Num=  ,4964.8, 2 ,4964.8, 2 , 0 , 0 , 0 ,,
       1       1
    -.38   20.29
       1       1
    -.48   20.19
Pier Skew, UpSta & Num, DnSta & Num=  ,4982.3, 2 ,4982.3, 2 , 0 , 0 , 0 ,,
       1       1
   -1.87   20.29
       1       1
   -1.97   20.19
Pier Skew, UpSta & Num, DnSta & Num=  ,4999.6, 2 ,4999.6, 2 , 0 , 0 , 0 ,,
       1       1
      -3   20.29
       1       1
    -3.1   20.19
Pier Skew, UpSta & Num, DnSta & Num=  ,5016.6, 2 ,5016.6, 2 , 0 , 0 , 0 ,,
       1       1
    -.07   20.28
       1       1
    -.17   20.18
Pier Skew, UpSta & Num, DnSta & Num=  ,5033.8, 2 ,5033.8, 2 , 0 , 0 , 0 ,,
       1       1
    5.25   20.28
       1       1
    5.15   20.18
Pier Skew, UpSta & Num, DnSta & Num=  ,5049.8, 2 ,5049.8, 2 , 0 , 0 , 0 ,,
       1       1
    7.66   20.28
       1       1
    7.56   20.18
Pier Skew, UpSta & Num, DnSta & Num=  ,5066.4, 2 ,5066.4, 2 , 0 , 0 , 0 ,,
       1       1
   13.25   20.28
       1       1
   13.15   20.18
BR Coef= 1 , 1 , 0 ,1.25, 0 ,,,.8,0,2,0,
WSPro=,,,, 1 ,,,, 0 ,,,, 0 ,,,,-1 ,-1 ,-1 , 0 , 0 , 0 , 0 , 0
BR U #Sta/Elev= 119
  4146.7    21.1  4205.6   19.65  4225.6   20.41  4245.6   19.46  4265.6   18.06
  4279.7   17.96  4305.6   17.77  4325.6   18.29  4326.9   18.28  4381.9   17.65
  4406.9   16.54  4421.9   16.41  4451.9   16.93  4496.9   16.31  4501.9   15.95
  4511.9   14.41  4516.9   13.86  4541.9   14.14  4610.8   13.53  4735.8   12.63
  4740.8   12.27  4742.8   12.01  4757.8    9.94  4772.8    7.49  4782.8    6.86
  4788.7    9.85    4883    9.78    4894   10.22  4901.2   10.49  4905.5   11.03
  4912.6   13.44 4931.87   14.05 4931.98   14.06 4932.09   14.06 4932.21   14.07
  4932.3   14.07  4932.4   14.07  4944.9   14.47    4948   14.69  4960.4    3.88
  4964.8     .66    4965     .67  4973.6    -.75    4982    -.69  4982.3    -.78
  4990.1   -2.11  4999.6   -1.99  5008.7    -.28  5016.6    1.03    5026    -.77
  5033.8    6.73  5039.5    3.86  5047.8    8.69  5049.8    8.65  5062.1   12.81
  5066.4   14.44 5082.99    17.6  5083.1   17.62  5083.2   17.64 5083.31   17.66
 5083.39   17.67  5083.5    17.7  5084.1   17.81  5111.6   17.03  5146.6   17.57
  5161.6   17.52  5186.6    18.4  5198.3   18.31  5200.3   18.31  5228.3   18.34
  5233.8   18.23  5258.3   17.74  5273.3   17.85  5283.3   17.58  5288.3   17.44
  5308.3   17.96  5324.4   17.79  5334.4   17.93  5344.4   18.32  5386.6    18.6
  5416.6   18.91  5429.8   18.76  5444.8   18.82  5499.8   19.82  5546.7   21.24
  5550.7   21.37  5554.8   21.49  5583.7   23.08  5600.7   23.85  5603.7   23.98
  5613.7   25.13  5615.7   25.27  5618.7   25.48  5628.7   25.31  5640.7   25.31
  5653.7    25.3  5658.7   25.07  5678.7   24.16  5693.7   24.25  5708.7   24.28
  5723.7    24.3  5728.7   24.31  5743.7   24.85  5748.7   24.85  5763.7   24.86
  5768.7    24.6  5773.7   24.34  5778.7   23.92  5783.7   23.92  5803.7   23.92
  5818.7   23.51  5828.7   23.54  5843.7   24.35  5878.7   24.04  5893.7   24.37
  5908.7   24.31  5943.7   25.26  5974.7   24.82  5977.3   24.78
BR U #Mann= 5
  4146.7      .2  4279.7     .18  4944.9    .055  5047.8     .18  5974.7      .2
BR U Banks=4944.9,5047.8
BR D #Sta/Elev= 119
  4146.7      21  4205.6   19.55  4225.6   20.31  4245.6   19.36  4265.6   17.96
  4279.7   17.86  4305.6   17.67  4325.6   18.19  4326.9   18.18  4381.9   17.55
  4406.9   16.44  4421.9   16.31  4451.9   16.83  4496.9   16.21  4501.9   15.85
  4511.9   14.31  4516.9   13.76  4541.9   14.04  4610.8   13.43  4735.8   12.53
  4740.8   12.17  4742.8   11.91  4757.8    9.84  4772.8    7.39  4782.8    6.76
  4788.7    9.75    4883    9.68    4894   10.12  4901.2   10.39  4905.5   10.93
  4912.6   13.34 4931.87   13.95 4931.98   13.96 4932.09   13.96 4932.21   13.97
  4932.3   13.97  4932.4   13.97  4944.9   14.37    4948   14.59  4960.4    3.78
  4964.8     .56    4965     .57  4973.6    -.85    4982    -.79  4982.3    -.88
  4990.1   -2.21  4999.6   -2.09  5008.7    -.38  5016.6     .93    5026    -.87
  5033.8    6.63  5039.5    3.76  5047.8    8.59  5049.8    8.55  5062.1   12.71
  5066.4   14.34 5082.99    17.5  5083.1   17.52  5083.2   17.54 5083.31   17.56
 5083.39   17.57  5083.5    17.6  5084.1   17.71  5111.6   16.93  5146.6   17.47
  5161.6   17.42  5186.6    18.3  5198.3   18.21  5200.3   18.21  5228.3   18.24
  5233.8   18.13  5258.3   17.64  5273.3   17.75  5283.3   17.48  5288.3   17.34
  5308.3   17.86  5324.4   17.69  5334.4   17.83  5344.4   18.22  5386.6    18.5
  5416.6   18.81  5429.8   18.66  5444.8   18.72  5499.8   19.72  5546.7   21.14
  5550.7   21.27  5554.8   21.39  5583.7   22.98  5600.7   23.75  5603.7   23.88
  5613.7   25.03  5615.7   25.17  5618.7   25.38  5628.7   25.21  5640.7   25.21
  5653.7    25.2  5658.7   24.97  5678.7   24.06  5693.7   24.15  5708.7   24.18
  5723.7    24.2  5728.7   24.21  5743.7   24.75  5748.7   24.75  5763.7   24.76
  5768.7    24.5  5773.7   24.24  5778.7   23.82  5783.7   23.82  5803.7   23.82
  5818.7   23.41  5828.7   23.44  5843.7   24.25  5878.7   23.94  5893.7   24.27
  5908.7   24.21  5943.7   25.16  5974.7   24.72  5977.3   24.68
BR D #Mann= 5
  4146.7      .2  4279.7     .18  4944.9    .055  5047.8     .18  5974.7      .2
BR D Banks=4944.9,5047.8
BC Design=,, 0 ,, 0 ,,,,,,
BC HTab HWMax=25.44

Type RM Length L Ch R = 1 ,20928.0 ,582.6,582.6,582.6
BEGIN DESCRIPTION:
Downstream Section of Bridge/Culvert/Weir
END DESCRIPTION:
XS GIS Cut Line= 6
      3193360.16     13848191.58      3192823.14     13848013.39
       3192510.5      13847827.7      3192258.49     13847700.75
      3191976.16     13847600.33      3191662.79       13847543.
#Sta/Elev= 30
  4146.7   20.97  4225.6   20.28  4279.7   17.83  4496.9   16.18  4516.9   13.73
  4735.8    12.5  4782.8    6.73  4788.7    9.72    4883    9.65  4901.2   10.36
  4912.6   13.31  4944.9   14.34    4948   14.56  4964.8     .53  4990.1   -2.24
  4999.6   -2.12  5016.6      .9    5026     -.9  5033.8     6.6  5039.5    3.73
  5047.8    8.56  5066.4   14.31  5084.1   17.68  5288.3   17.31  5444.8   18.69
  5554.8   21.36  5618.7   25.35  5818.7   23.38  5974.7   24.69  5977.3   24.65
#Mann= 5 , 1 , 0
  4146.7      .2       0  4279.7     .18       0  4944.9    .055       0
  5047.8     .18       0  5974.7      .2       0
#XS Ineff= 2 , 0
       0    4920      20    5093       0      20
Permanent Ineff=
       F       F
Bank Sta=4944.9,5047.8
XS Rating Curve= 0
Exp/Cntr=.5,.3

Type RM Length L Ch R = 1 ,20345.4 ,345.4,331.4,311.3
BEGIN DESCRIPTION:
Cross Section 20345.4 - Interpolated
END DESCRIPTION:
XS GIS Cut Line= 5
      3193377.47     13847851.63      3193265.66     13847738.41
      3192980.04     13847446.22      3192848.72     13847344.45
      3192257.77     13847003.02
#Sta/Elev= 30
    4351    19.5    4501    17.6  4550.1    13.7  4600.1     6.7  4710.1     3.1
  4740.1     4.3  4790.1     2.3  4810.1     3.6  4910.1     4.2  4959.8    7.19
  4961.5    7.16  4971.2    3.65  4976.3   -3.75  5003.6   -2.78  5024.4    4.19
  5028.7     3.3  5028.9    7.12  5034.4    8.75  5048.7     7.1  5068.7     9.4
  5124.9    10.9  5134.9    12.5  5234.9    18.8  5334.9    22.2  5344.9    21.6
  5504.9    25.2  5584.9    25.3  5674.9    23.3    5708   24.57  5767.4    24.7
#Mann= 4 , 1 , 0
    4351      .2       0  4961.5    .055       0  5028.9      .2       0
    5708      .2       0
Bank Sta=4959.8,5034.4
XS Rating Curve= 0
Exp/Cntr=.3,.1

Type RM Length L Ch R = 1 ,20014.0 ,944.9,1046,1261.3
BEGIN DESCRIPTION:
Cross Section 20014
Located At: 2ND XS DS IH-10
END DESCRIPTION:
XS GIS Cut Line= 6
      3193816.97     13848008.57      3193559.43     13847542.33
      3193359.77     13847318.56      3193095.89     13847123.79
      3192867.68     13847117.89      3192484.05     13846983.85
#Sta/Elev= 30
  3913.5   18.94  4008.5   17.56  4198.5    18.9  4253.5    17.3  4511.2   17.31
  4616.2   15.25  4706.2   10.05  4746.1    10.3  4841.1    3.29  4871.1    2.98
  4902.5    9.41  4959.8   11.33  4961.5    11.3  4971.2    7.79  4976.3   -4.61
  5003.6   -3.64  5024.4    3.33  5028.9   11.26  5034.4   12.89    5081   15.03
  5140.4   15.33  5144.1    11.9  5204.1   16.03  5279.1   17.93  5307.3   20.76
  5367.3   18.68  5467.3   22.31  5552.3   21.56    5708   24.82  5708.7   24.79
#Mann= 4 , 1 , 0
  3913.5      .2       0  4961.5    .055       0  5034.4      .2       0
    5708      .2       0
Bank Sta=4959.8,5081
XS Rating Curve= 0
Exp/Cntr=.3,.1

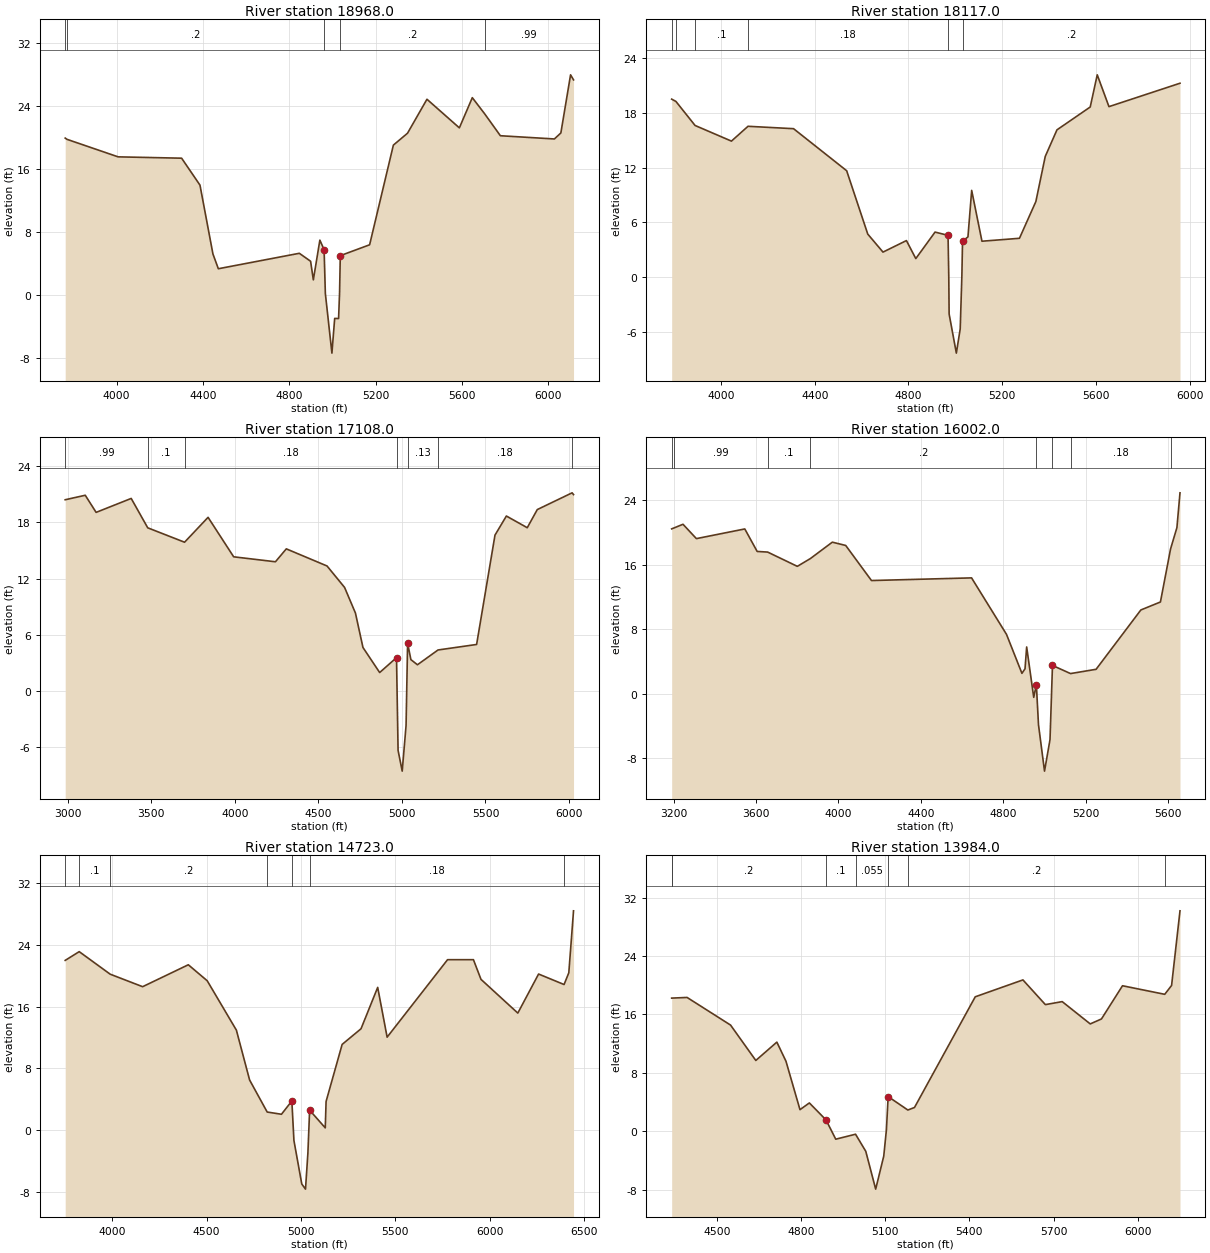
Type RM Length L Ch R = 1 ,18968.0 ,968.7,851,764.4
BEGIN DESCRIPTION:
Cross Section 18968
Located At: 3RD XS DS IH-10
END DESCRIPTION:
XS GIS Cut Line= 5
      3194391.21     13847875.05      3194106.03     13847417.57
       3194013.2     13846602.31      3193844.61     13846484.78
      3193927.79     13845700.53
#Sta/Elev= 30
  3762.4   19.96    3771    19.8  4007.4   17.58  4301.5   17.41  4386.5   13.99
  4446.5    5.25  4471.5    3.38  4846.5    5.34  4898.7    4.33  4911.4    1.97
  4941.6    7.01  4961.2     5.8    4967     .24  4997.4   -7.33  5010.2   -2.93
  5028.3   -2.94  5032.9     .38  5036.2    5.04    5172    6.42    5282   19.07
  5347.5   20.58  5437.5   24.89  5587.5   21.26  5647.5   25.09  5704.5   23.05
  5777.5   20.26  6027.5   19.85  6057.5   20.61  6102.5   27.99  6116.2   27.35
#Mann= 5 , 1 , 0
  3762.4      .2       0    3771      .2       0  4961.2    .055       0
  5036.2      .2       0  5704.5     .99       0
Bank Sta=4961.2,5036.2
XS Rating Curve= 0
Exp/Cntr=.3,.1

Type RM Length L Ch R = 1 ,18117.0 ,1211.7,1009,669.9
BEGIN DESCRIPTION:
Cross Section 18117
Located At: 4TH XS DS IH-10
END DESCRIPTION:
XS GIS Cut Line= 5
      3195490.35     13847613.63      3195163.58     13847072.97
      3194789.28      13846502.6      3194563.51     13846152.07
      3194153.56     13845997.59
#Sta/Elev= 30
  3789.7   19.49  3807.8   19.24  3889.6   16.61  4044.7    14.9  4115.5   16.52
  4309.7   16.26  4536.4   11.66  4626.4    4.73  4691.4    2.76  4791.4    4.02
  4831.4    2.05  4913.6    4.95    4969    4.59  4972.1     .02  4973.6   -4.01
  5004.4   -8.29  5020.9   -5.64    5028     .19  5030.8    3.96  5053.9    4.42
  5069.8    9.51  5113.7    3.95  5273.7    4.27  5343.7    8.29  5383.7   13.22
  5433.7   16.13  5575.6   18.63  5605.6   22.15  5655.6   18.67  5958.7   21.23
#Mann= 6 , 1 , 0
  3789.7      .2       0  3807.8     .18       0  3889.6      .1       0
  4115.5     .18       0    4969    .055       0  5030.8      .2       0
Bank Sta=4969,5030.8
XS Rating Curve= 0
Exp/Cntr=.3,.1

Type RM Length L Ch R = 1 ,17108.0 ,478.4,1106,1498.7
BEGIN DESCRIPTION:
Cross Section 17108
Located At: 6TH XS US SHELDON
END DESCRIPTION:
XS GIS Cut Line= 6
       3196791.5     13847001.68      3196175.63     13846375.65
      3195710.18     13845902.53      3195056.64     13845950.06
      3194732.02     13846143.79      3194278.33     13846033.24
#Sta/Elev= 30
  2984.9   20.42  3104.9    20.9  3169.9   19.07  3379.9   20.56  3478.8   17.42
  3699.2   15.88  3839.9   18.54  3993.1   14.32  4243.1   13.79  4308.1   15.17
  4551.8   13.34  4656.8   11.05  4721.8    8.31  4766.8    4.63  4866.8    1.95
  4967.6    3.54    4977   -6.37  5001.7   -8.59  5024.8   -3.71    5034    5.09
  5053.7    3.33  5092.9    2.78    5216    4.36    5447    4.95    5557   16.64
  5625.1   18.68  5750.1   17.43  5810.1   19.37  6018.6   21.16    6027   20.97
#Mann= 7 , 1 , 0
  2984.9     .99       0  3478.8      .1       0  3699.2     .18       0
  4967.6    .055       0    5034     .13       0    5216     .18       0
  6018.6      .2       0
Bank Sta=4967.6,5034
XS Rating Curve= 0
Exp/Cntr=.3,.1

Type RM Length L Ch R = 1 ,16002.0 ,1425.3,1279,1249.8
BEGIN DESCRIPTION:
Cross Section 16002
Located At: 5TH XS US SHELDON
END DESCRIPTION:
XS GIS Cut Line= 6
       3196791.5     13846954.14      3195918.13     13846086.71
      3195852.77      13845825.3      3195882.48     13845326.22
      3195930.01     13845052.92      3195862.35     13844875.31
#Sta/Elev= 30
  3190.7   20.48  3202.7    20.6  3245.7   21.05  3310.7   19.27  3545.7   20.47
  3605.7   17.68  3656.7    17.6  3800.7   15.83  3863.8   16.79  3970.7   18.83
  4035.7   18.42  4160.7   14.07  4646.6    14.4  4816.1     7.4  4891.1    2.56
  4906.1    3.12  4914.1    5.83  4948.4    -.42  4961.2    1.17  4971.5   -3.81
  5000.8   -9.57  5027.5   -5.65  5039.4    3.54  5127.1    2.53  5251.1    3.06
  5468.5   10.42  5563.5   11.41  5612.7   17.99  5643.5   20.63  5658.5   24.95
#Mann= 8 , 1 , 0
  3190.7      .2       0  3202.7     .99       0  3656.7      .1       0
  3863.8      .2       0  4961.2    .055       0  5039.4     .15       0
  5127.1     .18       0  5612.7     .99       0
Bank Sta=4961.2,5039.4
XS Rating Curve= 0
Exp/Cntr=.3,.1

Type RM Length L Ch R = 1 ,14723.0 ,918.6,739,612.7
BEGIN DESCRIPTION:
Cross Section 14723
Located At: 4TH XS US SHELDON
END DESCRIPTION:
XS GIS Cut Line= 6
      3197991.65     13846567.96      3197664.87     13846193.66
      3197415.34     13846057.01      3196886.56     13845439.11
      3196642.97     13845023.22      3196200.83     13844595.82
#Sta/Elev= 30
  3751.8   21.98    3826   23.11    3990   20.19  4161.8   18.57  4403.7   21.41
  4503.7   19.34  4658.2   12.94  4728.2    6.48  4821.3    2.33  4896.9    2.04
  4951.9    3.76  4962.9   -1.36  5004.4   -6.99  5024.2   -7.66  5036.8   -3.01
    5046    2.57  5128.8     .28  5133.2     3.7  5218.2   11.09  5318.2   13.12
  5406.4   18.48  5456.4   12.03  5776.4   22.07  5913.4   22.07  5953.4   19.52
  6148.4   15.15  6258.4   20.21  6393.3   18.85  6418.4   20.37  6443.4    28.4
#Mann= 7 , 1 , 0
  3751.8     .99       0    3826      .1       0    3990      .2       0
  4821.3     .13       0  4951.9    .055       0    5046     .18       0
  6393.3     .99       0
Bank Sta=4951.9,5046
XS Rating Curve= 0
Exp/Cntr=.3,.1

Type RM Length L Ch R = 1 ,13984.0 ,885.1,1016,1079.3
BEGIN DESCRIPTION:
Cross Section 13984
Located At: 3RD XS US SHELDON
END DESCRIPTION:
XS GIS Cut Line= 6
      3197843.11     13844928.16      3197450.99     13844945.98
      3197336.87     13845019.01      3197066.71      13845056.7
      3196785.56     13845041.04       3196236.2     13844560.35
#Sta/Elev= 30
  4338.5   18.24  4393.5   18.33  4548.5   14.55  4638.5    9.71  4713.5   12.22
    4746    9.61    4796    2.98  4829.4     3.9  4888.5    1.59  4888.6    1.59
  4923.5   -1.06  4994.1    -.38  5030.6   -2.72  5065.9   -7.89  5094.6   -3.38
  5104.2     .25  5110.3    4.74  5110.7    4.76  5180.6    2.93  5204.3    3.28
  5420.9   18.42  5590.9   20.73  5670.9   17.35  5730.9   17.76  5830.9   14.71
  5870.9   15.39  5945.9   19.93  6096.5   18.76  6120.9   19.97  6150.9   30.18
#Mann= 7 , 1 , 0
  4338.5      .2       0  4338.5      .2       0  4888.5      .1       0
  4994.1    .055       0  5110.3     .13       0  5180.6      .2       0
  6096.5     .99       0
Bank Sta=4888.6,5110.7
XS Rating Curve= 0
Exp/Cntr=.3,.1

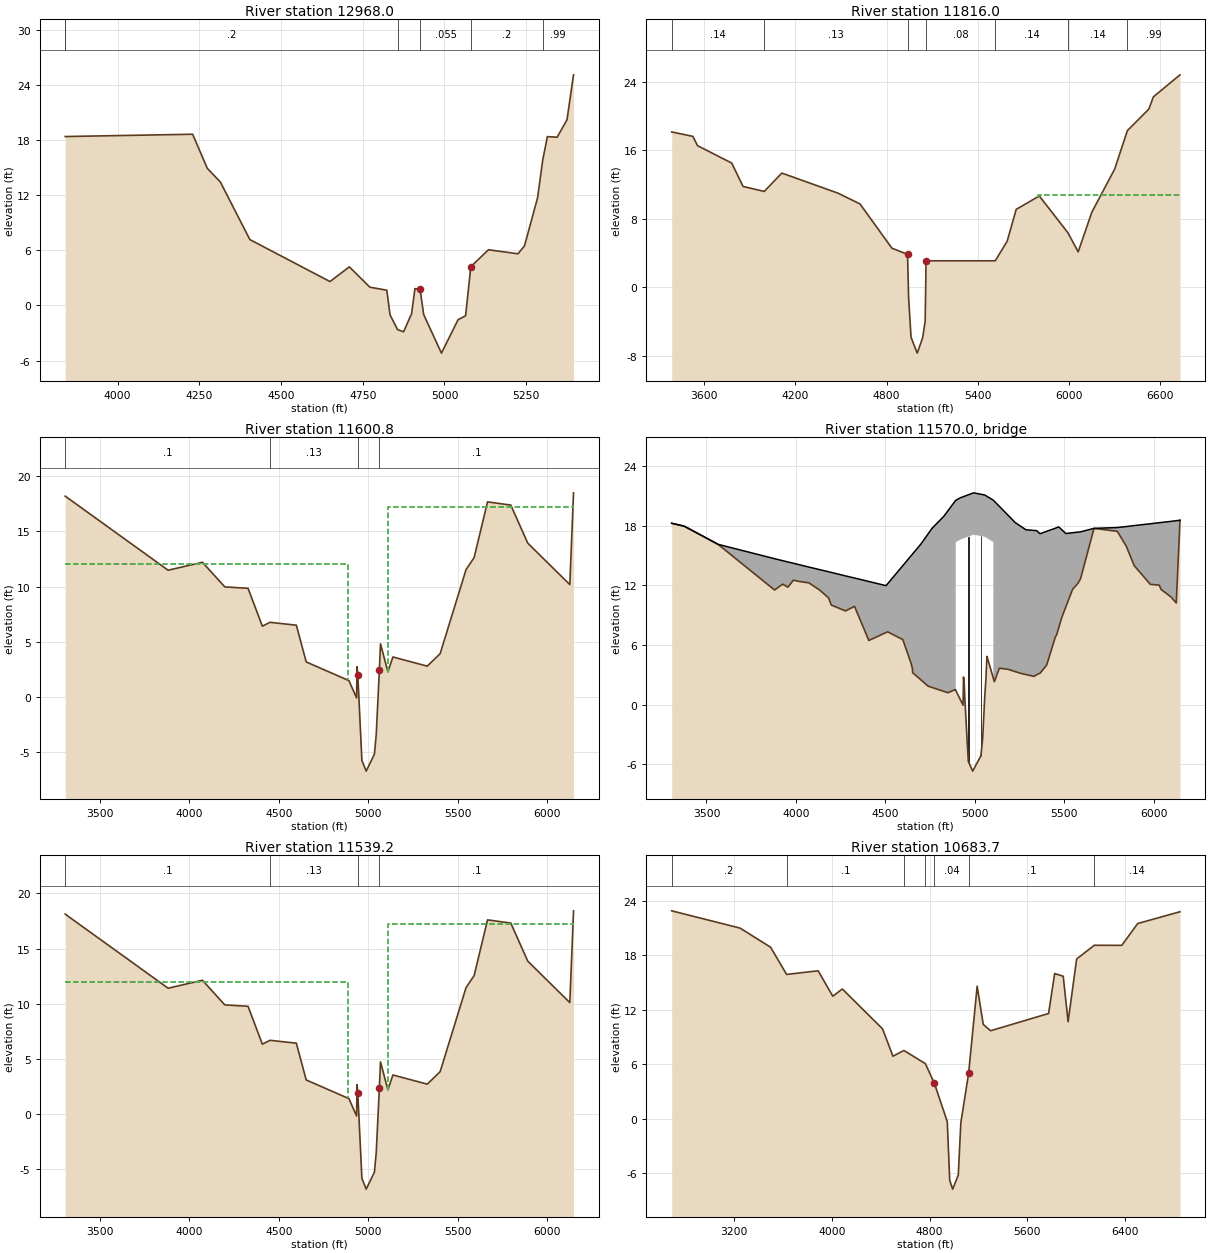
Type RM Length L Ch R = 1 ,12968.0 ,920.4,1152,1431.5
BEGIN DESCRIPTION:
Cross Section 12968
Located At: 2ND XS US SHELDON
END DESCRIPTION:
XS GIS Cut Line= 6
      3197777.76     13844839.04      3197629.23     13844500.38
      3197480.69     13844262.73      3197314.34     13844120.14
      3196815.27     13843989.43      3196665.97       13843908.
#Sta/Elev= 30
  3839.8   18.37  3839.9   18.37  4229.6   18.62  4274.6   14.91  4314.6   13.42
  4404.6    7.17  4649.8     2.6    4709     4.2  4771.9    1.99  4823.7    1.66
  4833.6   -1.02  4856.6   -2.62    4875   -2.86  4899.5    -.89  4909.7    1.83
  4925.5    1.77  4936.5    -.99  4990.8   -5.18  5041.6   -1.55  5064.7   -1.12
  5080.7    4.22  5134.7    6.06  5224.9    5.62  5244.9    6.48  5284.9   11.71
  5300.7   15.82  5314.9   18.36  5344.9    18.3  5374.9   20.19  5394.9   25.08
#Mann= 6 , 1 , 0
  3839.8      .2       0  3839.9      .2       0  4856.6     .08       0
  4925.5    .055       0  5080.7      .2       0  5300.7     .99       0
Bank Sta=4925.5,5080.7
XS Rating Curve= 0
Exp/Cntr=.3,.1

Type RM Length L Ch R = 1 ,11816.0 ,155.9,215.2,206.4
BEGIN DESCRIPTION:
Cross Section 11816
Located At: 1ST XS US SHELDON
END DESCRIPTION:
XS GIS Cut Line= 6
      3197840.14     13844877.66      3197893.62     13843784.45
      3197828.26     13843225.97       3197834.2     13842905.14
       3197935.2      13842281.3      3197890.64     13841547.55
#Sta/Elev= 30
  3385.1   18.13  3525.1   17.61  3555.1   16.53  3780.1    14.5  3855.1   11.77
  3994.4   11.19  4110.1   13.33  4479.6   10.99  4624.6    9.73  4834.6    4.57
  4937.5    3.85  4944.5   -1.23  4960.5   -5.82  5001.4   -7.67  5037.1   -5.86
  5053.5   -3.94  5057.9     1.1  5058.8     3.1  5514.8     3.1  5592.8    5.37
  5652.8     9.1  5804.7   10.66  5993.2    6.36  6060.5    4.14  6150.5    8.77
  6300.5   13.79  6384.6   18.29  6525.5   20.79  6555.5   22.22  6730.6   24.79
#Mann= 7 , 1 , 0
  3385.1     .14       0  3994.4     .13       0  4937.5     .04       0
  5058.8     .08       0  5514.8     .14       0  5993.2     .14       0
  6384.6     .99       0
#XS Ineff= 2 , 0
       0                    5798       0    10.8
Permanent Ineff=
       F       F
Bank Sta=4937.5,5058.8
XS Rating Curve= 0
Exp/Cntr=.5,.3

Type RM Length L Ch R = 1 ,11600.8 ,61.6,61.6,61.6
BEGIN DESCRIPTION:
Upstream Section of Bridge/Culvert/Weir
END DESCRIPTION:
XS GIS Cut Line= 5
      3197996.65     13844970.23      3198026.22     13843976.57
      3198044.05     13843400.26      3198055.93     13843091.31
      3198103.68     13842130.26
#Sta/Elev= 30
  3305.6   18.19  3880.9   11.48  4072.9    12.2  4197.9    9.97  4327.9    9.84
  4407.9    6.41  4450.7    6.76  4597.9     6.5  4653.1    3.17  4891.7    1.48
  4934.8    -.09  4937.3    2.74  4941.4    2.02  4964.4   -5.75  4988.5   -6.72
  5034.5   -5.18  5044.5   -3.43  5062.2    2.44  5068.4    4.81  5109.9    2.27
  5137.8    3.62  5329.9    2.79  5401.9    3.92  5546.9   11.54  5591.9   12.62
  5666.9   17.67  5796.9   17.38  5891.9   13.93  6126.9   10.18  6147.7   18.49
#Mann= 4 , 1 , 0
  3305.6      .1       0  4450.7     .13       0  4941.4     .04       0
  5062.2      .1       0
#XS Ineff= 2 , 0
       0    4885      12    5110       0    17.2
Permanent Ineff=
       F       F
Bank Sta=4941.4,5062.2
XS Rating Curve= 0
Exp/Cntr=.5,.3

Type RM Length L Ch R = 3 ,11570.0 ,,,
BEGIN DESCRIPTION:
S.SHELDON RD.
Structure ID: N00-1
END DESCRIPTION:
Bridge Culvert--1,0,-1,-1, 0
Deck Dist Width WeirC Skew NumUp NumDn MinLoCord MaxHiCord MaxSubmerge Is_Ogee
10,41.6,2.6,0, 60, 60, , , .95, 0, 1,1,,
  3305.6  3375.9  3565.9  3880.9  3925.9  3955.9  3985.9  4072.9  4132.9  4182.9
  4197.9  4277.9  4327.9  4407.9  4504.2  4512.9  4597.9  4642.9    4651  4653.1
  4699.9  4739.1  4760.9    4828  4850.4  4891.7 4893.91    4894    4921    4994
  5056.1 5103.99  5104.1  5109.9  5137.8  5186.9  5227.1  5286.1  5329.9  5346.2
  5364.9  5401.9  5451.9  5456.9  5469.9  5486.9  5509.9  5546.9  5576.9  5591.9
  5666.9  5796.9  5846.9  5891.9  5981.9  6031.9  6041.9  6096.9  6126.9  6147.7
   18.23   17.94   16.11   14.67   14.47   14.34   14.21   13.83   13.57   13.36
   13.29   12.94   12.73   12.38   11.96   12.15   13.97   14.94   15.11   15.16
   16.16   17.16   17.71   18.95   19.49   20.49   20.54   20.54    20.8   21.29
   21.07   20.55   20.55   20.44   19.93   19.03   18.29   17.58   17.51   17.49
   17.18   17.42   17.74   17.78   17.86   17.58    17.2   17.28   17.34   17.37
   17.72    17.8    17.9      18   18.18   18.29   18.31   18.42   18.49   18.53
   18.23   17.93    16.1   11.52   12.11   11.81   12.51   12.24   11.52   10.73
   10.01    9.42    9.88    6.45    7.25    7.32    6.54    4.22    3.68    3.21
    2.48    1.86    1.73    1.33     1.2    1.52    1.44   16.34    16.6   17.09
   16.87   16.35    2.66    2.31    3.66    3.55    3.32    3.03    2.83       3
    3.17    3.96    6.86    6.96    7.74    8.77    9.85   11.58   12.19   12.66
   17.71   17.42   15.94   13.97   12.09   12.01   11.58   10.83   10.22   18.53
  3305.6  3375.9  3565.9  3880.9  3925.9  3955.9  3985.9  4072.9  4132.9  4182.9
  4197.9  4277.9  4327.9  4407.9  4504.2  4512.9  4597.9  4642.9    4651  4653.1
  4699.9  4739.1  4760.9    4828  4850.4  4891.7 4893.91    4894    4921    4994
  5056.1 5103.99  5104.1  5109.9  5137.8  5186.9  5227.1  5286.1  5329.9  5346.2
  5364.9  5401.9  5451.9  5456.9  5469.9  5486.9  5509.9  5546.9  5576.9  5591.9
  5666.9  5796.9  5846.9  5891.9  5981.9  6031.9  6041.9  6096.9  6126.9  6147.7
   18.23   17.94   16.11   14.67   14.47   14.34   14.21   13.83   13.57   13.36
   13.29   12.94   12.73   12.38   11.96   12.15   13.97   14.94   15.11   15.16
   16.16   17.16   17.71   18.95   19.49   20.49   20.54   20.54    20.8   21.29
   21.07   20.55   20.55   20.44   19.93   19.03   18.29   17.58   17.51   17.49
   17.18   17.42   17.74   17.78   17.86   17.58    17.2   17.28   17.34   17.37
   17.72    17.8    17.9      18   18.18   18.29   18.31   18.42   18.49   18.53
   18.13   17.83      16   11.42   12.01   11.71   12.41   12.14   11.42   10.63
    9.91    9.32    9.78    6.35    7.15    7.22    6.44    4.12    3.58    3.11
    2.38    1.76    1.63    1.23     1.1    1.42    1.34   16.24    16.5   16.99
   16.77   16.25    2.56    2.21    3.56    3.45    3.22    2.93    2.73     2.9
    3.07    3.86    6.76    6.86    7.64    8.67    9.75   11.48   12.09   12.56
   17.61   17.32   15.84   13.87   11.99   11.91   11.48   10.73   10.12   18.43
Pier Skew, UpSta & Num, DnSta & Num=  ,4964.5, 2 ,4964.5, 2 , 0 , 0 , 0 ,,
       3       3
   -6.77    17.9
       3       3
   -6.87    17.8
Pier Skew, UpSta & Num, DnSta & Num=  ,5034.5, 2 ,5034.5, 2 , 0 , 0 , 0 ,,
       3       3
   -6.19   17.96
       3       3
   -6.29   17.86
Abutment Skew #Up #Dn= , 2 , 2
  4893.8  4937.4
   16.34    2.76
  4893.8  4937.4
   16.24    2.66
Abutment Skew #Up #Dn= , 2 , 2
  5068.5 5104.19
    4.84   16.35
  5068.5 5104.19
    4.74   16.25
BR Coef= 1 , 1 , 0 ,1.25, 0 ,,,.8,0,2,0,
WSPro=,,,, 1 ,,,, 0 ,,,, 0 ,,,,-1 ,-1 ,-1 , 0 , 0 , 0 , 0 , 0
BR U #Sta/Elev= 90
  3305.6   18.23  3375.9   17.93  3380.6   17.88  3410.6    17.6  3565.9    16.1
  3880.9   11.52  3925.9   12.11  3955.9   11.81  3985.9   12.51  4022.9   12.37
  4072.9   12.24  4132.9   11.52  4182.9   10.73  4197.9   10.01  4277.9    9.42
  4327.9    9.88  4407.9    6.45  4450.7     6.8  4504.2    7.25  4512.9    7.32
  4597.9    6.54  4642.9    4.22    4651    3.68  4653.1    3.21  4699.9    2.48
  4739.1    1.86  4760.9    1.73    4828    1.33  4850.4     1.2  4891.7    1.52
 4893.57    1.45 4893.68    1.45 4893.79    1.44 4893.91    1.44    4894    1.44
    4921     .45  4934.8    -.05  4937.3    2.78  4937.4    2.76  4941.4    2.06
  4944.4     .75  4958.4    -3.9  4964.4   -5.71  4988.5   -6.68    4994    -6.5
  5034.5   -5.14  5044.5   -3.39  5055.5     .62  5056.1     .79  5062.2    2.48
  5068.4    4.85  5068.5    4.84 5103.66    2.69 5103.77    2.69 5103.88    2.68
 5103.99    2.67  5104.1    2.66  5109.9    2.31  5137.8    3.66  5166.1     3.6
  5186.9    3.55  5227.1    3.32    5258    3.14  5286.1    3.03  5328.9    2.85
  5329.9    2.83  5346.2       3  5352.4    3.06  5364.9    3.17  5366.9    3.19
  5401.9    3.96  5451.9    6.86  5456.9    6.96  5469.9    7.74  5486.9    8.77
  5509.9    9.85  5546.9   11.58  5576.9   12.19  5591.9   12.66  5666.9   17.71
  5796.9   17.42  5826.9   16.54  5846.9   15.94  5891.9   13.97  5981.9   12.09
  6031.9   12.01  6041.9   11.58  6096.9   10.83  6126.9   10.22  6147.7   18.53
BR U #Mann= 4
  3305.6      .1  4450.7     .13  4941.4     .04  5062.2      .1
BR U Banks=4941.4,5062.2
BR D #Sta/Elev= 90
  3305.6   18.13  3375.9   17.83  3380.6   17.78  3410.6    17.5  3565.9      16
  3880.9   11.42  3925.9   12.01  3955.9   11.71  3985.9   12.41  4022.9   12.27
  4072.9   12.14  4132.9   11.42  4182.9   10.63  4197.9    9.91  4277.9    9.32
  4327.9    9.78  4407.9    6.35  4450.7     6.7  4504.2    7.15  4512.9    7.22
  4597.9    6.44  4642.9    4.12    4651    3.58  4653.1    3.11  4699.9    2.38
  4739.1    1.76  4760.9    1.63    4828    1.23  4850.4     1.1  4891.7    1.42
 4893.57    1.35 4893.68    1.35 4893.79    1.34 4893.91    1.34    4894    1.34
    4921     .35  4934.8    -.15  4937.3    2.68  4937.4    2.66  4941.4    1.96
  4944.4     .65  4958.4      -4  4964.4   -5.81  4988.5   -6.78    4994    -6.6
  5034.5   -5.24  5044.5   -3.49  5055.5     .52  5056.1     .69  5062.2    2.38
  5068.4    4.75  5068.5    4.74 5103.66    2.59 5103.77    2.59 5103.88    2.58
 5103.99    2.57  5104.1    2.56  5109.9    2.21  5137.8    3.56  5166.1     3.5
  5186.9    3.45  5227.1    3.22    5258    3.04  5286.1    2.93  5328.9    2.75
  5329.9    2.73  5346.2     2.9  5352.4    2.96  5364.9    3.07  5366.9    3.09
  5401.9    3.86  5451.9    6.76  5456.9    6.86  5469.9    7.64  5486.9    8.67
  5509.9    9.75  5546.9   11.48  5576.9   12.09  5591.9   12.56  5666.9   17.61
  5796.9   17.32  5826.9   16.44  5846.9   15.84  5891.9   13.87  5981.9   11.99
  6031.9   11.91  6041.9   11.48  6096.9   10.73  6126.9   10.12  6147.7   18.43
BR D #Mann= 4
  3305.6      .1  4450.7     .13  4941.4     .04  5062.2      .1
BR D Banks=4941.4,5062.2
BC Design=,, 0 ,, 0 ,,,,,,
BC HTab HWMax=18.49

Type RM Length L Ch R = 1 ,11539.2 ,855.5,855.5,855.5
BEGIN DESCRIPTION:
Downstream Section of Bridge/Culvert/Weir
END DESCRIPTION:
XS GIS Cut Line= 5
      3198058.22     13844972.19      3198087.78     13843978.53
      3198105.61     13843402.22      3198117.49     13843093.27
      3198165.25     13842132.22
#Sta/Elev= 30
  3305.6   18.12  3880.9   11.41  4072.9   12.13  4197.9     9.9  4327.9    9.77
  4407.9    6.34  4450.7    6.69  4597.9    6.43  4653.1     3.1  4891.7    1.41
  4934.8    -.16  4937.3    2.67  4941.4    1.95  4964.4   -5.82  4988.5   -6.79
  5034.5   -5.25  5044.5    -3.5  5062.2    2.37  5068.4    4.74  5109.9     2.2
  5137.8    3.55  5329.9    2.72  5401.9    3.85  5546.9   11.47  5591.9   12.55
  5666.9    17.6  5796.9   17.31  5891.9   13.86  6126.9   10.11  6147.7   18.42
#Mann= 4 , 1 , 0
  3305.6      .1       0  4450.7     .13       0  4941.4     .04       0
  5062.2      .1       0
#XS Ineff= 2 , 0
       0    4885      12    5110       0    17.2
Permanent Ineff=
       F       F
Bank Sta=4941.4,5062.2
XS Rating Curve= 0
Exp/Cntr=.5,.3

Type RM Length L Ch R = 1 ,10683.7 ,639,494.7,410.5
BEGIN DESCRIPTION:
Cross Section 10683.7 - Interpolated
END DESCRIPTION:
XS GIS Cut Line= 5
      3198874.07      13845955.6      3198420.64      13844633.1
      3198319.88     13844293.03      3198886.66      13843600.3
      3199894.28     13842466.73
#Sta/Elev= 30
  2686.5    22.9  3246.5      21  3496.5    18.9  3628.4    15.9  3886.5    16.3
  4006.5    13.5  4084.6    14.3  4414.6     9.9  4499.2     6.9  4589.6    7.53
  4764.9    6.08  4839.2     3.9  4944.4     -.3  4964.4   -6.76  4988.5   -7.73
  5034.5   -6.19  5055.5    -.43  5119.2       5  5189.2    14.6  5239.2    10.4
  5299.2     9.7  5774.3    11.6  5824.3      16  5894.3    15.7  5934.3    10.7
  6004.3    17.6  6149.1   19.11  6374.3    19.1  6504.3    21.5    6851    22.8
#Mann= 7 , 1 , 0
  2686.5      .2       0  3628.4      .1       0  4589.6     .13       0
  4764.9     .07       0  4839.2     .04       0  5119.2      .1       0
  6149.1     .14       0
Bank Sta=4839.2,5119.2
XS Rating Curve= 0
Exp/Cntr=.3,.1