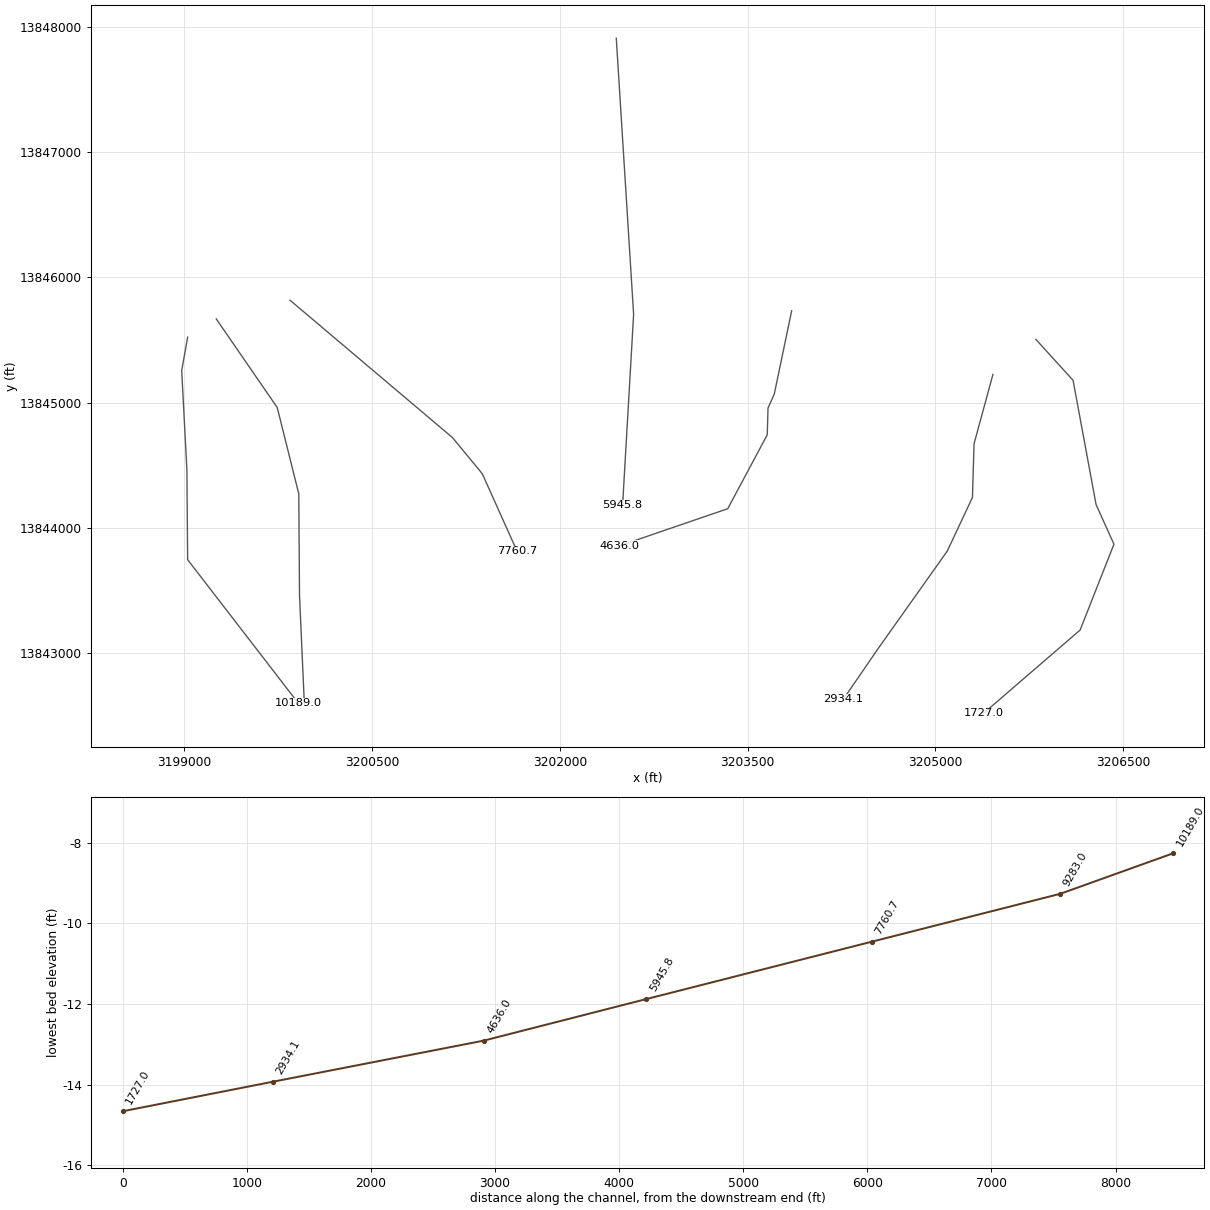
HEC-RAS study N100-00-00.prj: N100-00-00

--- N100-00-00.g01 (geometry) --- (continued)

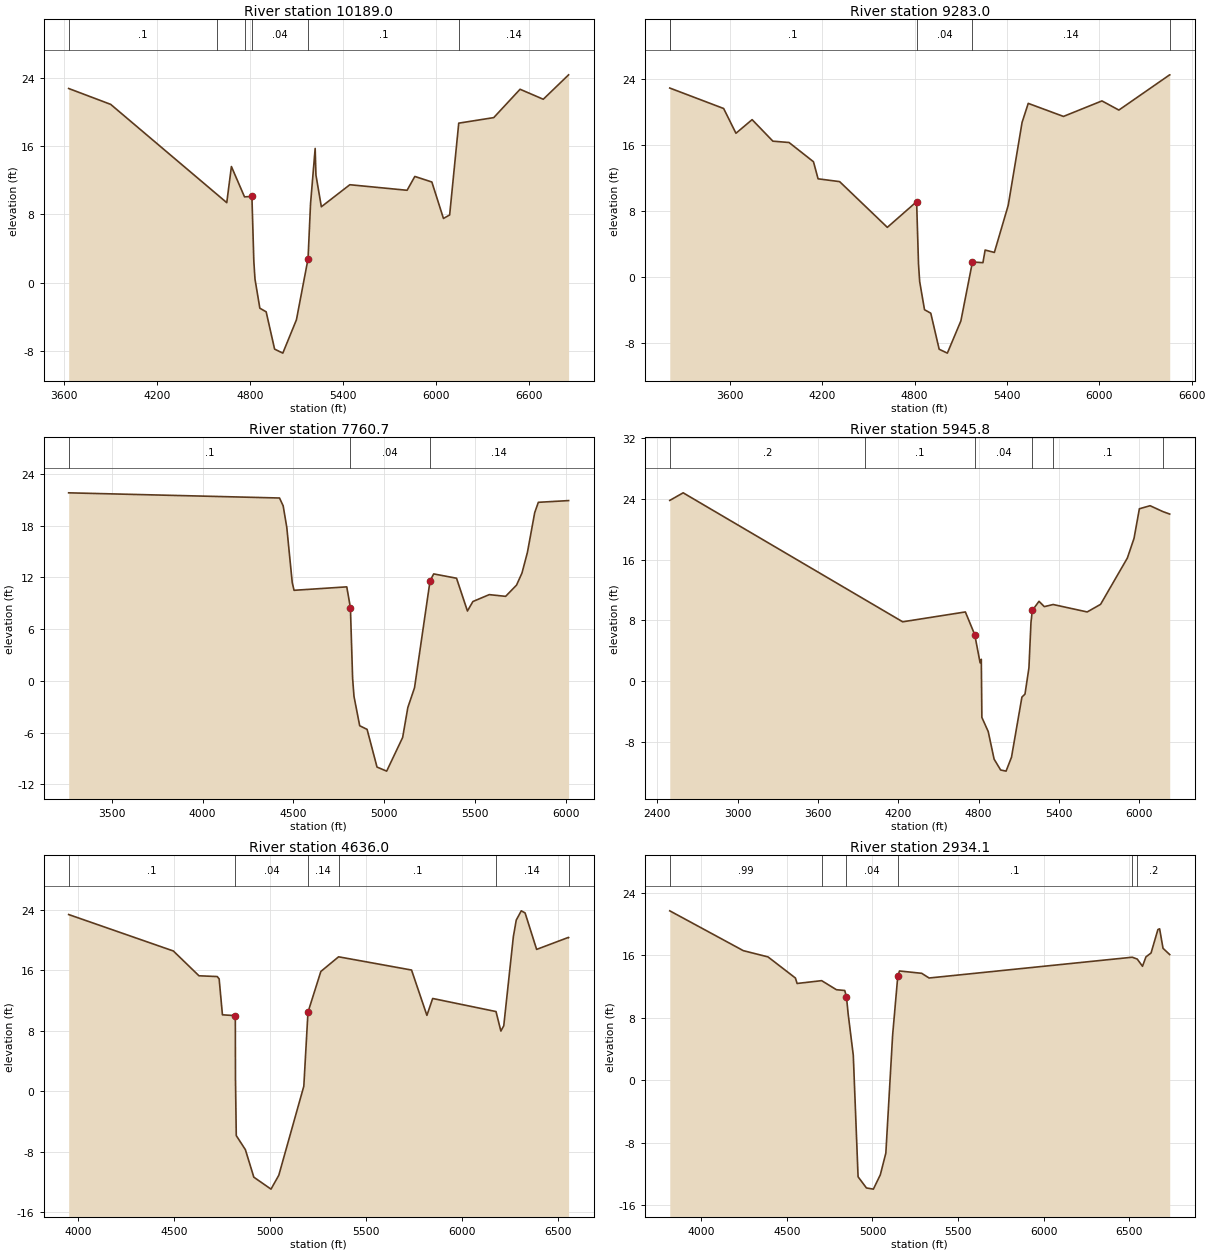
Type RM Length L Ch R = 1 ,10189.0 ,875.3,906,917.8
BEGIN DESCRIPTION:
Cross Section 10189-Interpolated
END DESCRIPTION:
XS GIS Cut Line= 5
      3199025.44     13845522.29      3198977.91     13845254.93
      3199019.49     13844464.73      3199025.44     13843745.84
      3199910.69     13842599.16
#Sta/Elev= 30
  3628.6   22.72  3900.2   20.86  4589.6   10.28  4650.2    9.35  4680.2   13.58
  4764.9   10.03  4812.7   10.08  4825.1    2.48  4832.6      .4    4864   -3.01
  4904.7   -3.43  4959.3    -7.8  5012.4   -8.27  5100.3   -4.37  5175.4    2.77
  5191.4    9.19  5221.4    15.7  5226.4   12.59  5261.4    8.87  5445.4   11.45
  5815.4    10.8  5865.4   12.42  5975.4   11.77  6050.4     7.5  6090.4    7.91
  6149.1   18.66  6375.4   19.31  6545.4   22.63  6695.4   21.46    6859   24.32
#Mann= 6 , 1 , 0
  3628.6      .1       0  4589.6     .13       0  4764.9     .07       0
  4812.7     .04       0  5175.4      .1       0  6149.1     .14       0
Bank Sta=4812.7,5175.4
XS Rating Curve= 0
Exp/Cntr=.3,.1

Type RM Length L Ch R = 1 ,9283.0  ,1383.6,1522.3,1659.3
BEGIN DESCRIPTION:
Cross Section 9283
Located At: 1ST XS DS SHELDON
END DESCRIPTION:
XS GIS Cut Line= 5
      3199254.18     13845667.85      3199741.36     13844960.83
      3199913.66     13844271.64       3199919.6     13843457.68
      3199958.22     13842593.22
#Sta/Elev= 30
  3209.1   22.85  3559.1   20.37  3639.1   17.37  3744.1   19.02  3879.1   16.41
  3984.1   16.25  4142.7   13.92  4172.7   11.85  4312.7   11.51  4622.7    5.97
  4812.9    9.08  4825.3    1.48  4832.8     -.6  4864.2   -4.01  4904.9   -4.43
  4959.5    -8.8  5012.6   -9.27  5100.5   -5.37  5175.6    1.77  5243.8    1.69
  5258.1    3.22  5318.1    2.93  5408.1    8.64  5498.1   18.68  5538.1   20.99
  5767.1   19.41  6017.1   21.29  6127.1   20.18  6457.1   24.45  6457.4   24.45
#Mann= 5 , 1 , 0
  3209.1      .2       0  3209.1      .1       0  4812.9     .04       0
  5175.6     .14       0  6457.1      .2       0
Bank Sta=4812.9,5175.6
XS Rating Curve= 0
Exp/Cntr=.3,.1

Type RM Length L Ch R = 1 ,7760.7  ,2202.3,1814.9,1639.7
BEGIN DESCRIPTION:
Cross Section 7760.7 - Interpolated
END DESCRIPTION:
XS GIS Cut Line= 4
      3199843.89     13845817.05       3201141.2     13844721.27
      3201380.51     13844431.58       3201657.6     13843814.42
#Sta/Elev= 30
  3263.1    21.8  4423.1    21.2  4443.1    20.3  4463.1    17.8  4493.1    11.4
  4503.1    10.5  4793.1    10.9  4813.1     8.5  4825.3     .29  4832.8   -1.79
  4864.2    -5.2  4904.9   -5.62  4959.5   -9.99  5012.6  -10.46  5100.5   -6.56
    5129   -3.09  5165.9    -.79  5251.3    11.6  5271.3    12.4    5397    11.9
    5457     8.1    5487     9.2    5577      10    5667     9.8    5727    11.1
    5757    12.5    5787    14.9    5827    19.5    5847    20.7  6013.5    20.9
#Mann= 3 , 1 , 0
  3263.1      .1       0  4813.1     .04       0  5251.3     .14       0
Bank Sta=4813.1,5251.3
XS Rating Curve= 0
Exp/Cntr=.3,.1

Type RM Length L Ch R = 1 ,5945.8  ,1664.1,1309.8,1225.4
BEGIN DESCRIPTION:
Cross Section 5945.8 - Interpolated
END DESCRIPTION:
XS GIS Cut Line= 3
       3202451.1     13847907.85      3202589.65     13845703.69
      3202501.48     13844179.68
#Sta/Elev= 30
  2492.8    23.8  2592.8    24.8  3951.9   10.71  4232.8     7.8  4701.3     9.1
  4771.3     6.1  4811.3     2.4  4820.3    2.86  4824.5    -4.8  4871.9   -6.66
  4915.9   -10.3  4964.8  -11.73  5005.3  -11.88  5045.8  -10.05  5123.7   -2.12
  5146.6   -1.73  5176.1    1.73  5191.3     7.7  5201.3     9.3  5251.3    10.5
  5291.3     9.8  5357.1   10.08  5611.3     9.1  5711.3    10.1  5911.3    16.2
  5961.3    18.8  6001.3    22.7  6081.3    23.1  6176.5   22.33  6227.9      22
#Mann= 6 , 1 , 0
  2492.8      .2       0  3951.9      .1       0  4771.3     .04       0
  5201.3     .14       0  5357.1      .1       0  6176.5     .14       0
Bank Sta=4771.3,5201.3
XS Rating Curve= 0
Exp/Cntr=.3,.1

Type RM Length L Ch R = 1 ,4636.0  ,1807.7,1701.9,1699.8
BEGIN DESCRIPTION:
Cross Section 4636
Located At: 2ND XS UD SHIP CHANNEL
END DESCRIPTION:
XS GIS Cut Line= 6
      3203852.75      13845733.2      3203714.06     13845069.27
       3203663.8     13844956.18      3203657.51     13844742.56
       3203341.8     13844152.82      3202474.37     13843855.75
#Sta/Elev= 30
  3952.1    23.4  4497.1   18.58  4630.4    15.3  4725.4    15.2  4735.4   14.89
  4752.5   10.14  4819.6   10.03  4820.3    1.83  4824.5   -5.83  4871.9   -7.69
  4915.9  -11.33  5005.3  -12.91  5045.8  -11.08  5176.1      .7  5197.7   10.48
  5264.7   15.87  5357.1   17.81  5736.8   16.06  5816.8   10.07  5846.8    12.3
  6176.5   10.57  6201.8    7.99  6216.8    8.69  6266.8   20.48  6281.8   22.66
  6307.9   23.89  6327.9   23.61  6387.9   18.79  6553.9   20.38  6554.3   20.36
#Mann= 6 , 1 , 0
  3952.1      .1       0  4819.6     .04       0  5197.7     .14       0
  5357.1      .1       0  6176.5     .14       0  6553.9      .2       0
Bank Sta=4819.6,5197.7
XS Rating Curve= 0
Exp/Cntr=.3,.1

Type RM Length L Ch R = 1 ,2934.1  ,1192.6,1207.1,1237.4
BEGIN DESCRIPTION:
Cross Section 2934.1 - Interpolated
END DESCRIPTION:
XS GIS Cut Line= 6
      3205461.35     13845225.08      3205310.21     13844670.89
      3205297.61     13844242.65      3205096.09     13843814.42
       3204541.9     13843033.51      3204264.81     13842630.47
#Sta/Elev= 30
    3815    21.7    4245    16.6  4389.4    15.8  4549.4    13.1  4559.4    12.4
  4702.9   12.76  4789.4    11.6  4837.9    11.5  4847.9    10.7  4857.9     8.5
  4887.9     3.2  4915.9  -12.35  4964.8  -13.78  5005.3  -13.93  5045.8   -12.1
  5078.2   -9.32  5117.9     5.8  5147.9    13.3  5157.9      14  5287.9    13.7
  5331.1    13.1  6518.6   15.76  6548.2   15.52  6578.7    14.6  6598.7    15.8
  6628.7    16.3  6668.7    19.3  6678.7    19.4  6698.7    16.9  6737.8    16.1
#Mann= 6 , 1 , 0
    3815     .99       0  4702.9     .06       0  4847.9     .04       0
  5147.9      .1       0  6518.6     .99       0  6548.2      .2       0
Bank Sta=4847.9,5147.9
XS Rating Curve= 0
Exp/Cntr=.3,.1

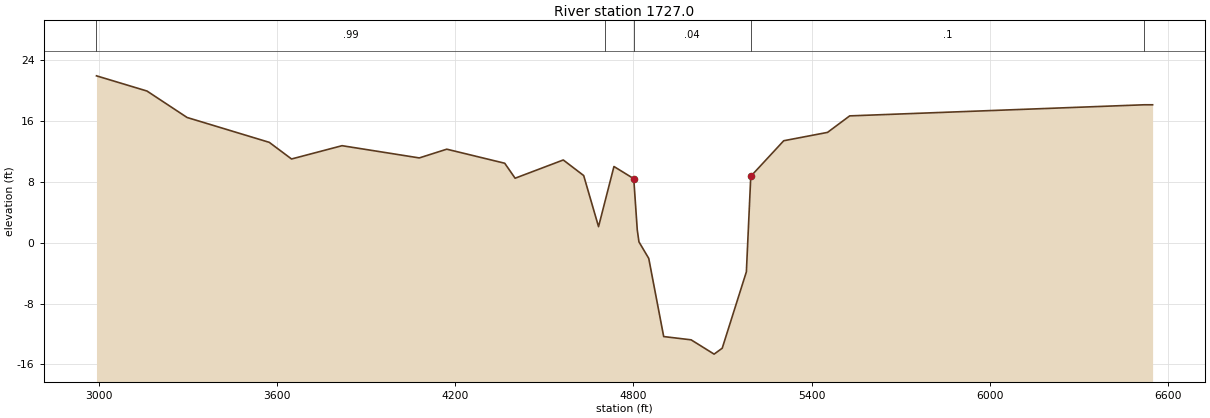
Type RM Length L Ch R = 1 ,1727.0  ,0,0,0
BEGIN DESCRIPTION:
Cross Section 1727
Located At: 1ST XS US SHIP CHANNEL
END DESCRIPTION:
XS GIS Cut Line= 6
      3205804.48     13845504.46      3206101.54     13845177.69
      3206285.72     13844185.49      3206428.29     13843869.23
      3206158.12     13843184.39      3205385.61     13842518.95
#Sta/Elev= 30
  2992.8   21.95  3162.8   19.95  3297.8   16.47  3574.4    13.2  3649.4   11.01
  3819.4   12.76  4079.4   11.15  4171.9    12.3  4366.9   10.45  4401.9    8.48
    4564   10.88  4632.7    8.83  4682.7    2.11  4702.9    5.19  4734.6   10.02
  4801.2    8.42    4813     1.7  4818.7     .11  4851.7   -2.07    4902  -12.35
  4994.3  -12.78  5071.7  -14.66    5099  -13.88  5180.3   -3.83  5195.1    8.73
    5306   13.41  5453.5   14.51    5528   16.68  6518.6   18.14  6547.6   18.14
#Mann= 5 , 1 , 0
  2992.8     .99       0  4702.9     .06       0  4801.2     .04       0
  5195.1      .1       0  6518.6     .99       0
Bank Sta=4801.2,5195.1
XS Rating Curve= 0
Exp/Cntr=.3,.1

Chan Stop Cuts=-1